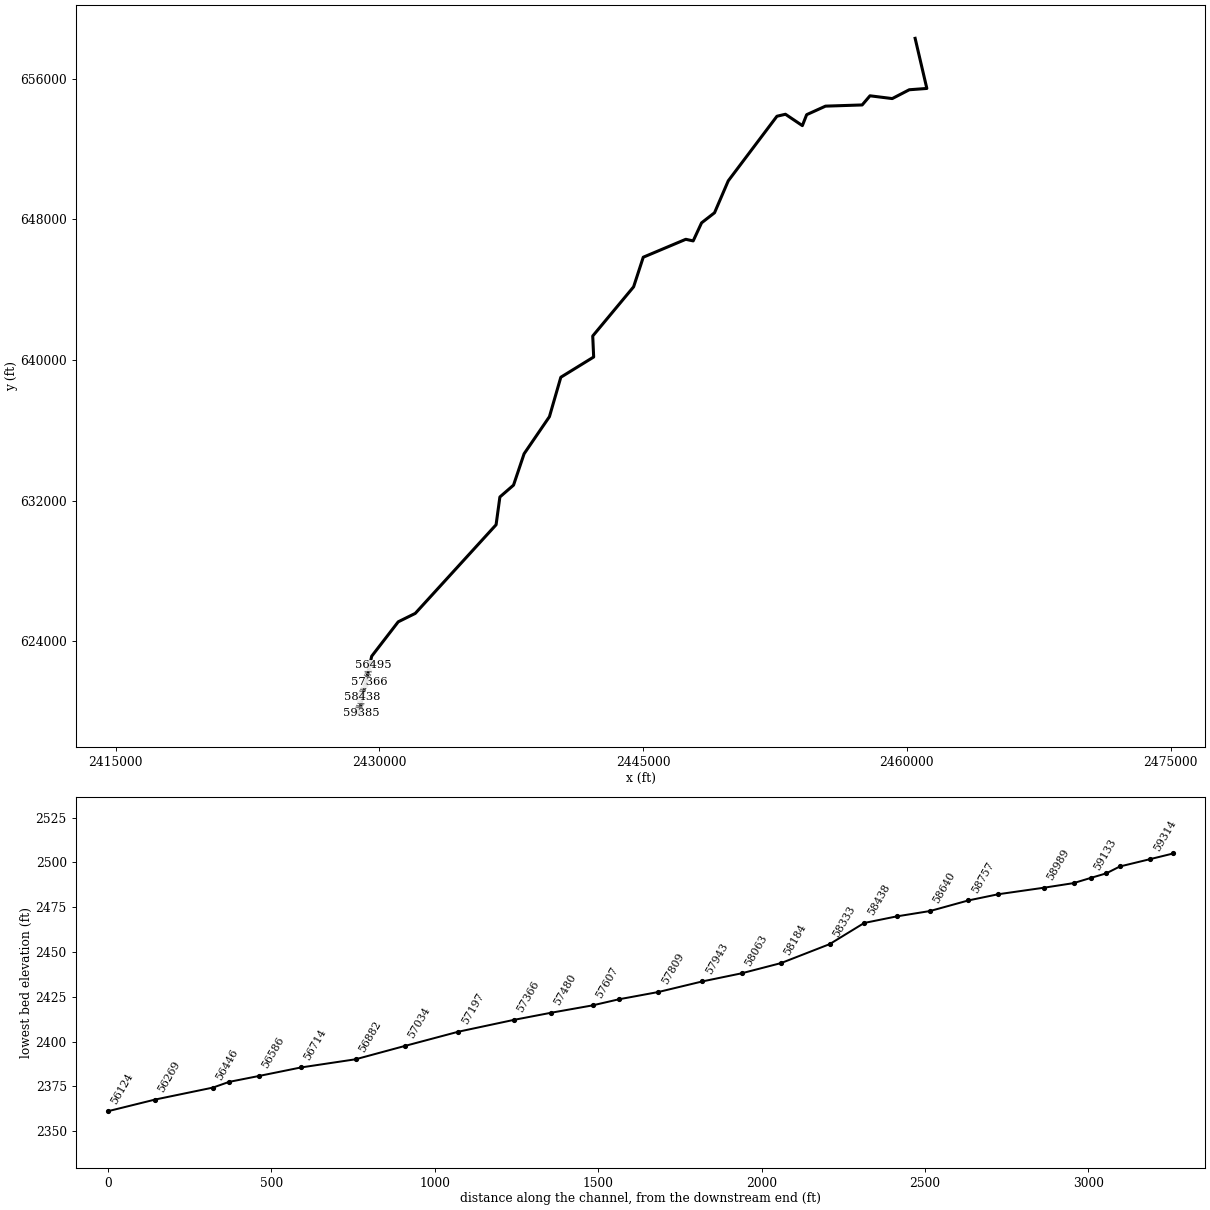
--- REEDSCK.prj (project) ---

Proj Title=REEDSCK
Current Plan=p01
Default Exp/Contr=0,0
English Units
Geom File=g01
Flow File=f01
Plan File=p01
Background Map Layer=QC
BEGIN DESCRIPTION:
Stream Name: Reeds Creek
Flood Zone: Zone A
Pendleton County, WV
WVDHSEM Flood Warning & Analysis Mapping
HEC-RAS Version: 5.0.7
Hydrology Method:
Regression
Model Notes:
Tie in with SBPOTOMC River at the downstream end.
END DESCRIPTION:
DSS File=dss
DSS Export Rating Curves= 0
DSS Export Rating Curve Sorted= 0
DSS Export Volume Flow Curves= 0
DXF OffsetX= 0
DXF OffsetY= 0
DXF ScaleX= 0
DXF ScaleY= 0

--- REEDSCK.p01 (plan) ---

Plan Title=Floodplain
Program Version=5.07
Short Identifier=Floodplain
Geom File=g01
Flow File=f01
Subcritical Flow
K Sum by GR= 0
Std Step Tol= 0.01
Critical Tol= 0.01
Num of Std Step Trials= 20
Max Error Tol= 0.3
Flow Tol Ratio= 0.001
Split Flow NTrial= 30
Split Flow Tol= 0.02
Split Flow Ratio= 0.02
Log Output Level= 0
Friction Slope Method= 1
Unsteady Friction Slope Method= 2
Unsteady Bridges Friction Slope Method= 1
Parabolic Critical Depth
Global Vel Dist= 0 , 0 , 0
Global Log Level= 0
CheckData=True
Encroach Param=-1 ,0,0, 0
Computation Interval=0.1SEC
Output Interval=1MIN
Instantaneous Interval=Max Profile
Mapping Interval=1HOUR
Computation Time Step Use Courant=        0
Computation Time Step Use Time Series=    0
Computation Time Step Count To Double=0
Computation Time Step Max Doubling=0
Computation Time Step Max Halving=0
Computation Time Step Residence Courant=0
Run HTab= 0
Run UNet= 0
Run Sediment= 0
Run PostProcess= 0
Run WQNet= 0
Run RASMapper= 0
UNET Theta= 0
UNET Theta Warmup= 0
UNET ZTol= 0
UNET ZSATol= 0
UNET MxIter= 0
UNET Max Iter WO Improvement= 0
UNET MaxInSteps= 0
UNET DtIC= 0
UNET DtMin= 0
UNET MaxCRTS= 0
UNET WFStab= 0
UNET SFStab= 0
UNET WFX= 1
UNET SFX= 1
UNET 1D Methodology=Finite Difference
UNET DSS MLevel= 1
UNET Pardiso=0
UNET DZMax Abort= 0
UNET Use Existing IB Tables= 0
UNET Froude Reduction=False
UNET Froude Limit= 0
UNET Froude Power= 0
UNET D1 Cores= 0
UNET D2 Coriolis=0
UNET D2 Cores= 0
UNET D2 Theta= 1
UNET D2 Theta Warmup= 1
UNET D2 Z Tol= 0.01
UNET D2 Volume Tol= 0.01
UNET D2 Max Iterations= 20
UNET D2 Equation= 0
UNET D2 RampUpFraction=0.1
UNET D2 TimeSlices= 1
UNET D2 BCVolumeCheck=0
UNET D1D2 MaxIter= 0
UNET D1D2 ZTol=0.01
UNET D1D2 QTol=0.1
UNET D1D2 MinQTol=1
DSS File=dss
Write IC File= 0
Write IC File at Fixed DateTime=0
Write IC File at Sim End=0
Echo Input=False
Echo Parameters=False
Echo Output=False
Write Detailed= 0
HDF Write Warmup=0
HDF Write Time Slices=0
HDF Flush=0
HDF Face Node Velocities=0
HDF Compression= 1
HDF Chunk Size= 1
HDF Spatial Parts= 1
HDF Use Max Rows=0
HDF Fixed Rows= 1
Calibration Method= 0
Calibration Iterations= 20
Calibration Max Change=0.05
Calibration Tolerance=0.2
Calibration Maximum=1.5
Calibration Minimum=0.5
Calibration Optimization Method= 1
WQ AD Non Conservative
WQ ULTIMATE=-1
WQ Max Comp Step=1HOUR
WQ Output Interval=15MIN
WQ Output Selected Increments= 0
WQ Output face flow=0
WQ Output face velocity=0
WQ Output face area=0
WQ Output face dispersion=0
WQ Output cell volume=0
WQ Output cell surface area=0
WQ Output cell continuity=0
WQ Output cumulative cell continuity=0
WQ Output face conc=0
WQ Output face dconc_dx=0
WQ Output face courant=0
WQ Output face peclet=0
WQ Output face adv mass=0
WQ Output face disp mass=0
WQ Output cell mass=0
WQ Output cell source sink temp=0
WQ Output nsm pathways=0
WQ Output nsm derived pathways=0
WQ Output MaxMinRange=-1
WQ Daily Max Min Mean=-1
WQ Daily Range=0
WQ Daily Time=0
WQ Create Restart=0
WQ Fixed Restart=0
WQ System Summary=0
WQ Write To DSS=0
WQ Use Fixed Temperature=0
Sorting and Armoring Iterations= 10
XS Update Threshold= 0.02
Bed Roughness Predictor= 0
Hydraulics Update Threshold= 0.02
Energy Slope Method= 1
Volume Change Method= 1
Sediment Retention Method= 0
XS Weighting Method= 0
Number of US Weighted Cross Sections= 1
Number of DS Weighted Cross Sections= 1
Upstream XS Weight=0
Main XS Weight=1
Downstream XS Weight=0
Number of DS XS's Weighted with US Boundary= 1
Upstream Boundary Weight= 1
Weight of XSs Associated with US Boundary= 0
Number of US XS's Weighted with DS Boundary= 1
Downstream Boundary Weight= 0.5
Weight of XSs Associated with DS Boundary= 0.5
Percentile Method= 0
Sediment Output Level= 3
Mass or Volume Output= 0
Output Increment Type= 1
Profile and TS Output Increment= 1
XS Output Flag= 0
XS Output Increment= 10
Write Gradation File= 0
Read Gradation Hotstart= 0
Write HDF5 File= 1
Write Binary Output= 1
Write DSS Sediment File= 0
SV Curve= 0
Specific Gage Flag= 0

--- REEDSCK.f01 (steady flow) ---

Flow Title=Flows
Program Version=5.07
Number of Profiles= 6
Profile Names=P100yr,P10yr,P25yr,P50yr,P500yr,P101yr
River Rch & RM=REEDSCK,Main            ,59385
     575     269     380     475     843     700
River Rch & RM=REEDSCK,Main            ,58184
     805     375     531     664    1184     980
River Rch & RM=REEDSCK,Main            ,57197
     920     427     606     758    1355    1119
River Rch & RM=REEDSCK,Main            ,54614
    1043     484     686     860    1539    1270
River Rch & RM=REEDSCK,Main            ,53109
    1171     542     769     964    1729    1425
River Rch & RM=REEDSCK,Main            ,51470
    1367     631     897    1125    2022    1663
River Rch & RM=REEDSCK,Main            ,49467
    1636     753    1072    1345    2424    1991
River Rch & RM=REEDSCK,Main            ,43681
    1884     866    1234    1549    2796    2293
River Rch & RM=REEDSCK,Main            ,38695
    2107     967    1378    1732    3131    2564
River Rch & RM=REEDSCK,Main            ,34977
    2373    1087    1551    1950    3531    2888
River Rch & RM=REEDSCK,Main            ,31824
    2645    1209    1727    2172    3940    3219
River Rch & RM=REEDSCK,Main            ,26653
    3053    1393    1991    2506    4555    3716
River Rch & RM=REEDSCK,Main            ,22941
    3597    1637    2343    2951    5375    4378
River Rch & RM=REEDSCK,Main            ,12836
    4007    1820    2607    3286    5994    4877
Boundary for River Rch & Prof#=REEDSCK,Main            , 1
Up Type= 0
Dn Type= 3
Dn Slope=0.00861
Boundary for River Rch & Prof#=REEDSCK,Main            , 2
Up Type= 0
Dn Type= 3
Dn Slope=0.00861
Boundary for River Rch & Prof#=REEDSCK,Main            , 3
Up Type= 0
Dn Type= 3
Dn Slope=0.00861
Boundary for River Rch & Prof#=REEDSCK,Main            , 4
Up Type= 0
Dn Type= 3
Dn Slope=0.00861
Boundary for River Rch & Prof#=REEDSCK,Main            , 5
Up Type= 0
Dn Type= 3
Dn Slope=0.00861
Boundary for River Rch & Prof#=REEDSCK,Main            , 6
Up Type= 0
Dn Type= 3
Dn Slope=0.00861
DSS Import GetInterval= 0
DSS Import GetPeak= 0
DSS Import FillOption= 0

--- REEDSCK.g01 (geometry) ---

Geom Title=Geometry
Program Version=5.07

River Reach=REEDSCK         ,Main
Reach XY= 30
     2428835.652      619913.132     2429566.818      623149.288
     2431074.633      625105.122      2432044.02      625584.232
     2436640.493      630624.601     2436856.245      632203.736
     2437632.628      632879.184     2438233.277      634661.904
     2439673.734      636771.395     2440321.729      639013.447
       2442189.6      640164.695      2442136.29      641359.503
     2444460.905      644155.559     2445009.853      645839.619
     2447428.523      646858.636     2447848.855      646767.004
     2448325.808      647794.281     2449062.836      648368.051
     2449843.367      650183.465     2452612.441      653857.225
     2453096.608      653969.449     2454057.335      653323.186
     2454302.528      653945.666     2455373.351      654431.018
     2457458.653      654498.979     2457903.519      655019.148
     2459169.588      654861.381      2460136.72      655362.837
     2461136.998      655437.379     2460470.524      658287.069

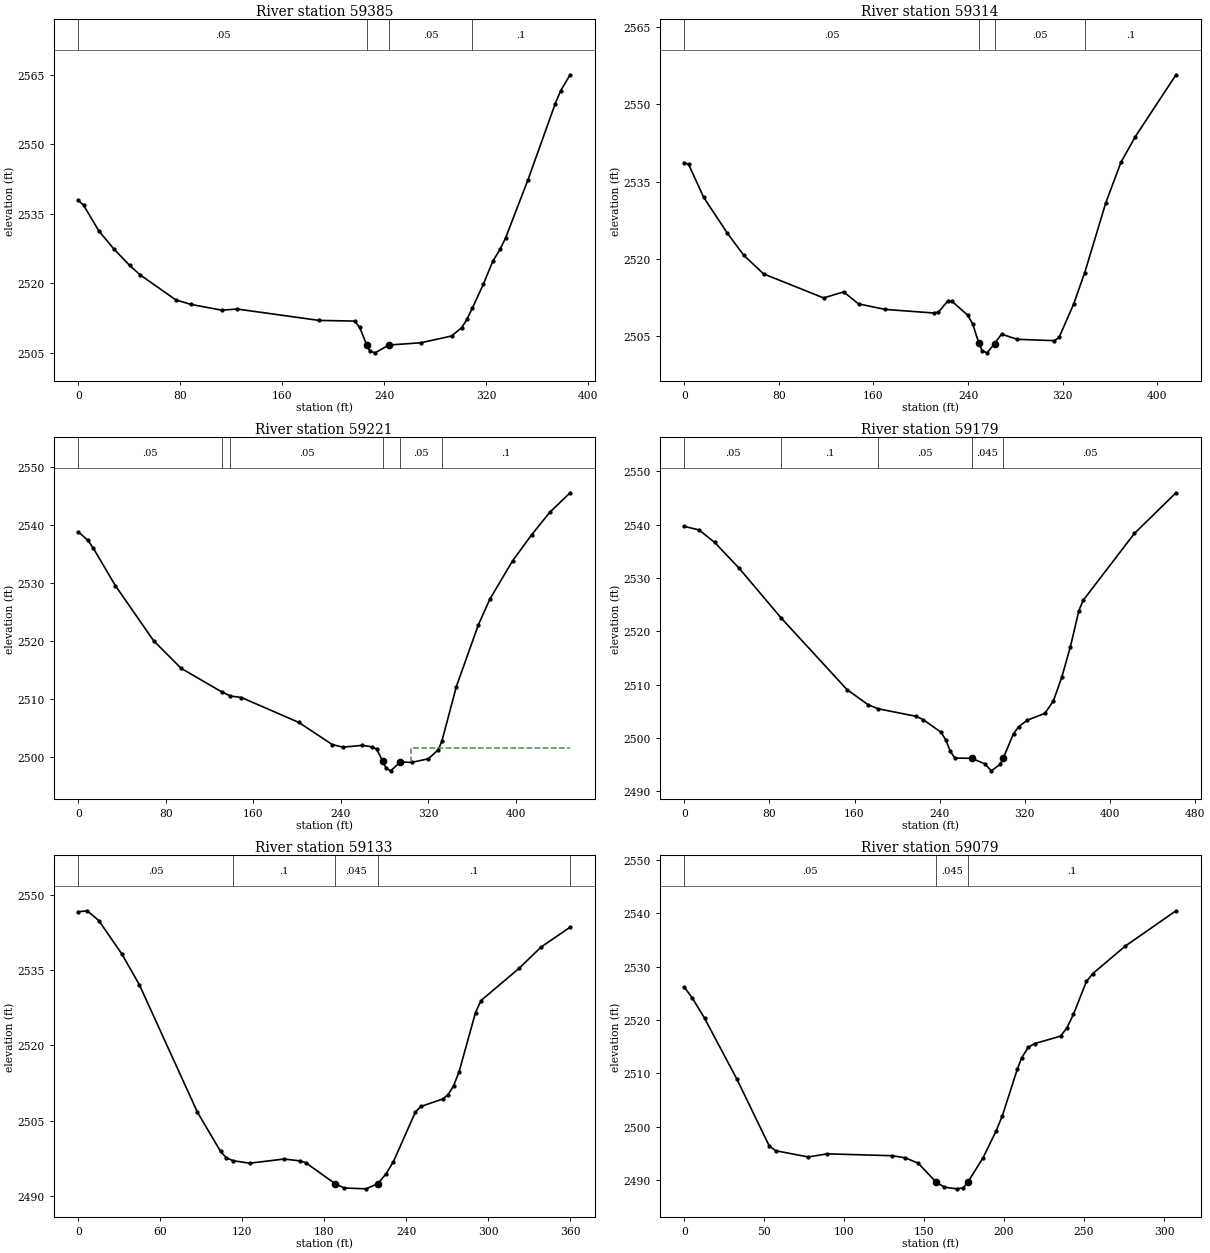
Type RM Length L Ch R = 1 ,59385   ,69.9,70.5,71.2
XS GIS Cut Line= 4
2428602.63963625619908.789259568 2428811.1128359619926.066044069
2428906.71104348 619929.521400972428981.57710965619898.423188867
#Sta/Elev= 30
       0 2537.85     4.1 2536.84    16.2 2531.24    28.2 2527.29    40.2 2523.85
    48.3 2521.84    76.4 2516.41    88.4 2515.42   112.5 2514.18   124.7 2514.42
   188.8 2511.97   216.8 2511.82   220.8 2510.45   226.42506.625   228.8 2505.35
   232.8 2504.97   243.72506.654   268.9 2507.15   292.9  2508.6   300.9 2510.43
   304.9 2512.19   309.2 2514.62   317.9 2519.84   325.2 2524.71   330.9  2527.3
   335.2 2529.71   352.8 2542.28   374.1 2558.64   378.5 2561.54   385.9 2564.97
#Mann= 4 ,-1 , 0
       0     .05       0   226.4    .045       0   243.7     .05       0
   309.2      .1       0
Bank Sta=226.4,243.7
XS Rating Curve= 0 ,0
Exp/Cntr(USF)=0,0
Exp/Cntr=0.3,0.1

Type RM Length L Ch R = 1 ,59314   ,91.7,93.60001,95.3
XS GIS Cut Line= 4
2428599.18427935619919.1553302692428812.26462154619991.717825175
2428914.77354291 620010.146395312429001.15746542620014.753537843
#Sta/Elev= 30
       0 2538.65     3.8  2538.3    16.4 2531.96    36.4 2525.03    50.2 2520.76
    67.1 2517.11   117.9 2512.45   134.8 2513.62   147.4 2511.29   169.7 2510.23
   210.8 2509.53     215  2509.7   223.2 2511.94   226.5 2511.78   239.8 2509.08
   243.9 2507.41   249.22503.634     252 2502.18   256.1 2501.81   262.42503.603
   268.3 2505.43   281.6 2504.43     313 2504.17     317 2504.83   329.2 2511.21
  338.652517.356   356.5 2530.91   369.3 2538.74   381.3 2543.65   415.8 2555.68
#Mann= 4 ,-1 , 0
       0     .05       0   249.2    .045       0   262.4     .05       0
  338.65      .1       0
Bank Sta=249.2,262.4
XS Rating Curve= 0 ,0
Exp/Cntr(USF)=0,0
Exp/Cntr=0.5,0.3

Type RM Length L Ch R = 1 ,59221   ,41,41.6,41.9
XS GIS Cut Line= 5
2428595.72892245619929.5214009782428773.00951359620063.280348622
2428811.25613417620081.606658692 2428876.9574183620109.230648409
2428989.72434159620125.114318428
#Sta/Elev= 30
       0  2538.8     8.8 2537.32    13.8 2535.96    33.8 2529.56    68.8 2520.07
      94 2515.31   130.9 2511.28   139.1 2510.54   149.1 2510.29   201.5 2506.01
   232.1  2502.2   241.7 2501.75   259.5 2502.05   268.3 2501.81   272.6 2501.44
   278.1 2499.41   281.3 2498.13   285.6 2497.67   294.3 2499.19   304.8 2499.12
   320.1 2499.75     329 2501.28   332.3 2502.74   345.6 2512.17   365.8 2522.84
   376.3 2527.24     397 2533.81   414.3 2538.26   430.9 2542.14   449.6 2545.52
#Mann= 6 ,-1 , 0
       0     .05       0   130.9      .1       0   139.1     .05       0
   278.1    .045       0   294.3     .05       0   332.3      .1       0
#XS Ineff= 2 , 0
          267.88 2501.57  303.85         2501.68
Permanent Ineff=
       F       F
Bank Sta=278.1,294.3
XS Rating Curve= 0 ,0
Exp/Cntr(USF)=0,0
Exp/Cntr=0.5,0.3

Type RM Length L Ch R = 1 ,59179   ,48,46.1,44.5
XS GIS Cut Line= 4
2428587.66642302619972.137469406 2428776.5592669620111.503531051
2428857.18426124620142.6017431542428997.70210852620151.816028222
#Sta/Elev= 30
       0 2539.65    13.8    2539    28.7 2536.64    51.8 2531.76   91.122522.476
   152.9 2509.07   172.8 2506.22  182.122505.467   217.6 2504.06   224.4 2503.45
   241.4 2501.05   245.7 2499.62   249.9 2497.55   254.2 2496.22     270 2496.18
   282.4 2495.14   288.5 2493.83   297.1 2495.09   299.7 2496.21   309.4 2500.81
   314.3 2502.12   322.5 2503.34   338.8  2504.6   346.8 2506.92   354.8 2511.45
   362.8 2517.09   370.8 2523.88   374.8 2525.79   422.9 2538.32     462 2545.95
#Mann= 5 ,-1 , 0
       0     .05       0   91.12      .1       0  182.12     .05       0
     270    .045       0   299.7     .05       0
Bank Sta=270,299.7
XS Rating Curve= 0 ,0
Exp/Cntr(USF)=0,0
Exp/Cntr=0.5,0.3

Type RM Length L Ch R = 1 ,59133   ,59.4,54,51
XS GIS Cut Line= 4
2428640.64856215620124.173173019 2428776.5592669620172.548169623
2428877.91640264620177.1553121572428991.94318035620173.699955257
#Sta/Elev= 30
       0 2546.67     6.5 2546.87      15 2544.91    31.9 2538.22    44.7 2532.08
    87.1 2506.68   104.1 2498.82   108.4 2497.53  113.422496.964   125.4 2496.48
   150.5 2497.31   162.5 2496.93   166.5 2496.56   187.92492.377   194.5 2491.53
   210.5 2491.36   219.12492.384   225.2 2494.38   230.5 2496.78   246.6 2506.68
   250.6  2507.8   266.6  2509.3   270.6 2510.19   274.6 2511.95   278.6 2514.78
   290.6 2526.56   294.6 2528.95   322.6 2535.41   338.6 2539.64   359.8 2543.59
#Mann= 5 ,-1 , 0
       0     .05       0  113.42      .1       0   187.9    .045       0
   219.1      .1       0   359.8      .1       0
Bank Sta=187.9,219.1
XS Rating Curve= 0 ,0
Exp/Cntr(USF)=0,0
Exp/Cntr=0.3,0.1

Type RM Length L Ch R = 1 ,59079   ,89.9,90.2,88.9
XS GIS Cut Line= 4
2428690.17534439 620252.021378332428823.78247787620231.289236928
2428891.73783024620220.9231662272428994.24675162620205.949952993
#Sta/Elev= 30
       0 2526.17       5 2524.16    12.7 2520.35      33  2508.9    53.2 2496.41
    57.2 2495.53    77.5 2494.36    89.6 2494.94   130.1 2494.59   138.2  2494.2
   146.3  2493.2   157.4 2489.68   162.7  2488.7   170.6 2488.39   174.6  2488.6
   177.52489.696   186.8 2494.17   194.9 2499.13   198.9 2502.05   208.4 2510.89
     211 2512.91   215.1 2514.87   219.1 2515.58   235.3 2516.98   239.3 2518.52
   243.4 2521.07   251.5 2527.22   255.5 2528.69   275.7 2533.82   307.5 2540.45
#Mann= 3 ,-1 , 0
       0     .05       0   157.4    .045       0   177.5      .1       0
Bank Sta=157.4,177.5
XS Rating Curve= 0 ,0
Exp/Cntr(USF)=0,0
Exp/Cntr=0.3,0.1

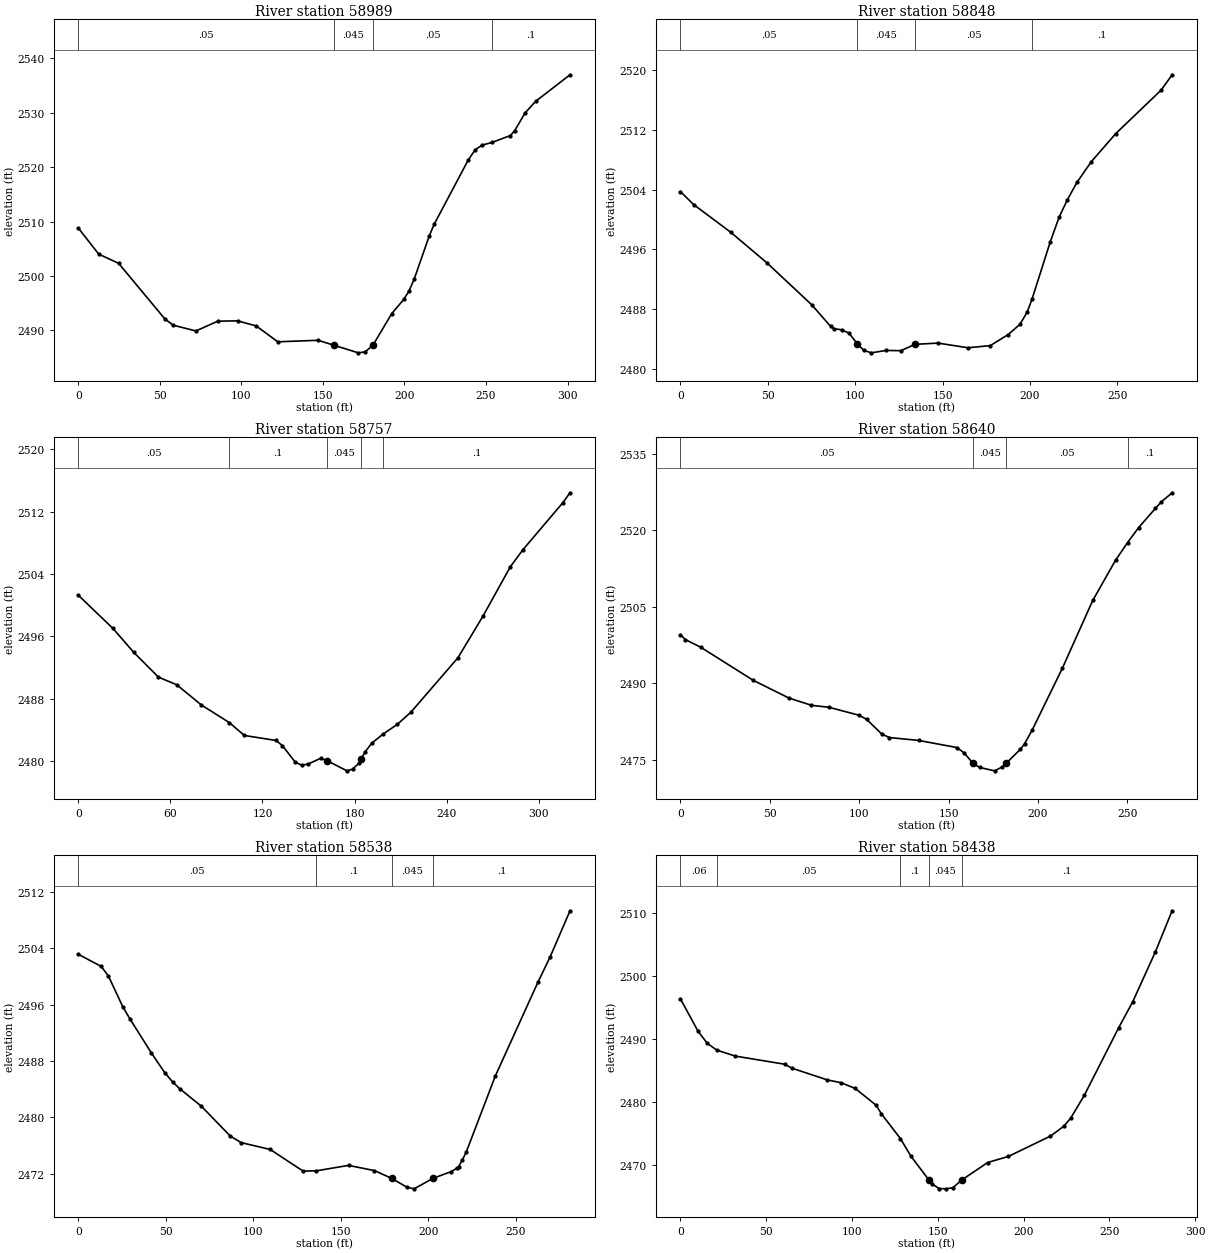
Type RM Length L Ch R = 1 ,58989   ,139.6,140.5,134
XS GIS Cut Line= 4
2428722.42534213620341.8606577372428822.63069224620324.583873236
2428920.53247108620301.5481605672429012.67532175620264.691020298
#Sta/Elev= 30
       0  2508.8    12.5    2504    24.7 2502.31    53.1 2492.07    58.2 2490.92
    72.1 2489.87    85.6 2491.67    97.7 2491.72   109.1 2490.79   122.3 2487.87
     147 2488.15   156.82487.232   171.7 2485.84   175.8 2486.01   180.62487.214
   192.2 2493.06   199.7 2495.72   202.9 2497.29     206 2499.45   215.2 2507.35
   218.3 2509.54   239.1 2521.32   243.4 2523.21   247.7 2524.06  253.632524.537
     265 2525.82   267.6 2526.73     274 2529.99   280.4  2532.1   301.5 2536.99
#Mann= 4 ,-1 , 0
       0     .05       0   156.8    .045       0   180.6     .05       0
  253.63      .1       0
Bank Sta=156.8,180.6
XS Rating Curve= 0 ,0
Exp/Cntr(USF)=0,0
Exp/Cntr=0.3,0.1

Type RM Length L Ch R = 1 ,58848   ,90.4,91.1,85.3
XS GIS Cut Line= 4
2428799.59497957620478.9231481162428873.30926011 620453.58386418
2428988.48782345620412.1195813772429058.74674709620371.807084207
#Sta/Elev= 30
       0 2503.73     7.6 2501.99    28.7 2498.31    49.3 2494.25    75.2 2488.59
    85.9 2485.73      88 2485.39    92.2 2485.27    96.5 2484.81   101.22483.393
     105  2482.5   109.3 2482.18   117.7  2482.5   126.2 2482.47   134.3 2483.32
   147.5 2483.48   164.5 2482.86   177.3 2483.14   187.5 2484.61   194.3 2485.98
   198.5 2487.65  201.172489.316   211.7 2497.04   216.8 2500.35   221.4 2502.61
   226.9 2504.95   235.2 2507.74   249.1 2511.47   275.2 2517.31   281.4 2519.34
#Mann= 4 ,-1 , 0
       0     .05       0   101.2    .045       0   134.3     .05       0
  201.17      .1       0
Bank Sta=101.2,134.3
XS Rating Curve= 0 ,0
Exp/Cntr(USF)=0,0
Exp/Cntr=0.3,0.1

Type RM Length L Ch R = 1 ,58757   ,111.6,117.1,123.8
XS GIS Cut Line= 4
2428806.50569337620513.4767171192428919.38068544620512.324931485
2429009.21996485 620486.985647552429115.18424313620444.369579113
#Sta/Elev= 30
       0 2501.27    22.6    2497    36.2 2493.92    52.2 2490.76    64.2 2489.77
    80.2 2487.18   98.412484.924   108.2 2483.27   128.8 2482.63     133 2481.97
   141.3 2479.86   145.5 2479.46   149.6 2479.59   157.9 2480.34   162.1 2480.03
   175.1 2478.73   178.7 2478.94   182.9 2479.72   184.3 2480.25     187  2481.2
   191.3 2482.29  198.452483.429   207.9  2484.7   216.7 2486.25   247.4 2493.25
   263.9 2498.66   281.5 2504.92   289.8 2507.13   315.7 2513.14   320.4 2514.42
#Mann= 5 ,-1 , 0
       0     .05       0   98.41      .1       0   162.1    .045       0
   184.3      .1       0  198.45      .1       0
Bank Sta=162.1,184.3
XS Rating Curve= 0 ,0
Exp/Cntr(USF)=0,0
Exp/Cntr=0.3,0.1

Type RM Length L Ch R = 1 ,58640   ,101.8,102.1,102.3
XS GIS Cut Line= 4
2428788.07712323620552.6374286552428910.16640038620594.101711459
2428986.18425218620618.2892097612429048.38067639620641.324922429
#Sta/Elev= 30
       0 2499.55     2.8 2498.59    11.3  2497.1    40.8 2490.58    60.6 2487.13
    73.3 2485.69    83.1  2485.3     100 2483.73   104.2 2482.91   112.7 2480.03
   116.9 2479.36   133.2  2478.8   154.7  2477.4   158.7 2476.33   163.6 2474.34
   167.3  2473.5   175.7 2472.83   179.9 2473.58   182.32474.338   190.2 2477.09
   192.5 2478.15   196.7 2480.81   213.6 2492.95   230.6 2506.26   243.4 2514.19
  250.12 2517.64   256.2 2520.54   265.6 2524.32     269 2525.63     275  2527.4
#Mann= 4 ,-1 , 0
       0     .05       0   163.6    .045       0   182.3     .05       0
  250.12      .1       0
Bank Sta=163.6,182.3
XS Rating Curve= 0 ,0
Exp/Cntr(USF)=0,0
Exp/Cntr=0.3,0.1

Type RM Length L Ch R = 1 ,58538   ,100.1,99.5,97.6
XS GIS Cut Line= 4
2428733.94319846620652.8427787642428838.75569111620675.878491432
2428957.38961135620717.3427742362429004.61282232620726.557059303
#Sta/Elev= 30
       0 2503.13    13.1 2501.41    17.2 2500.05    25.4  2495.7    29.5 2493.96
    41.8 2489.11    49.4 2486.33    54.1 2484.95    58.2    2484    70.4 2481.55
    86.8 2477.34      93  2476.4   109.7 2475.42   128.5 2472.35  135.962472.383
   154.5 2473.16   169.3 2472.42   179.22471.312   187.8 2470.07     192 2469.83
   202.62471.305   213.3 2472.29   216.4 2472.75   217.5    2473   219.6 2473.97
   221.7    2475   238.4 2485.85   262.7 2499.13   269.6 2502.68   281.1 2509.31
#Mann= 4 ,-1 , 0
       0     .05       0  135.96      .1       0   179.2    .045       0
   202.6      .1       0
Bank Sta=179.2,202.6
XS Rating Curve= 0 ,0
Exp/Cntr(USF)=0,0
Exp/Cntr=0.3,0.1

Type RM Length L Ch R = 1 ,58438   ,107.6,105.8,103.1
XS GIS Cut Line= 4
2428723.57712776620757.6552714062428826.08604914620781.842769708
2428903.25568658620795.6641973092429005.76460795620804.878482376
#Sta/Elev= 30
       0 2496.33    10.3 2491.18    15.6 2489.28   21.222488.184      32 2487.24
    60.8 2485.95    64.9 2485.33    85.5 2483.47    93.7 2483.01   101.9  2482.1
   114.1 2479.43   117.1 2478.09  128.222474.145   134.4 2471.33   144.92467.551
   146.6 2466.96   150.7 2466.21   154.8 2466.16   158.8 2466.34   164.12467.584
   179.1 2470.34   191.2 2471.31   215.7 2474.54   223.4 2476.08   227.4 2477.35
   235.4    2481   255.5 2491.77   263.6 2495.85   276.7  2503.7   286.6 2510.32
#Mann= 5 ,-1 , 0
       0     .06       0   21.22     .05       0  128.22      .1       0
   144.9    .045       0   164.1      .1       0
Bank Sta=144.9,164.1
XS Rating Curve= 0 ,0
Exp/Cntr(USF)=0,0
Exp/Cntr=0.3,0.1

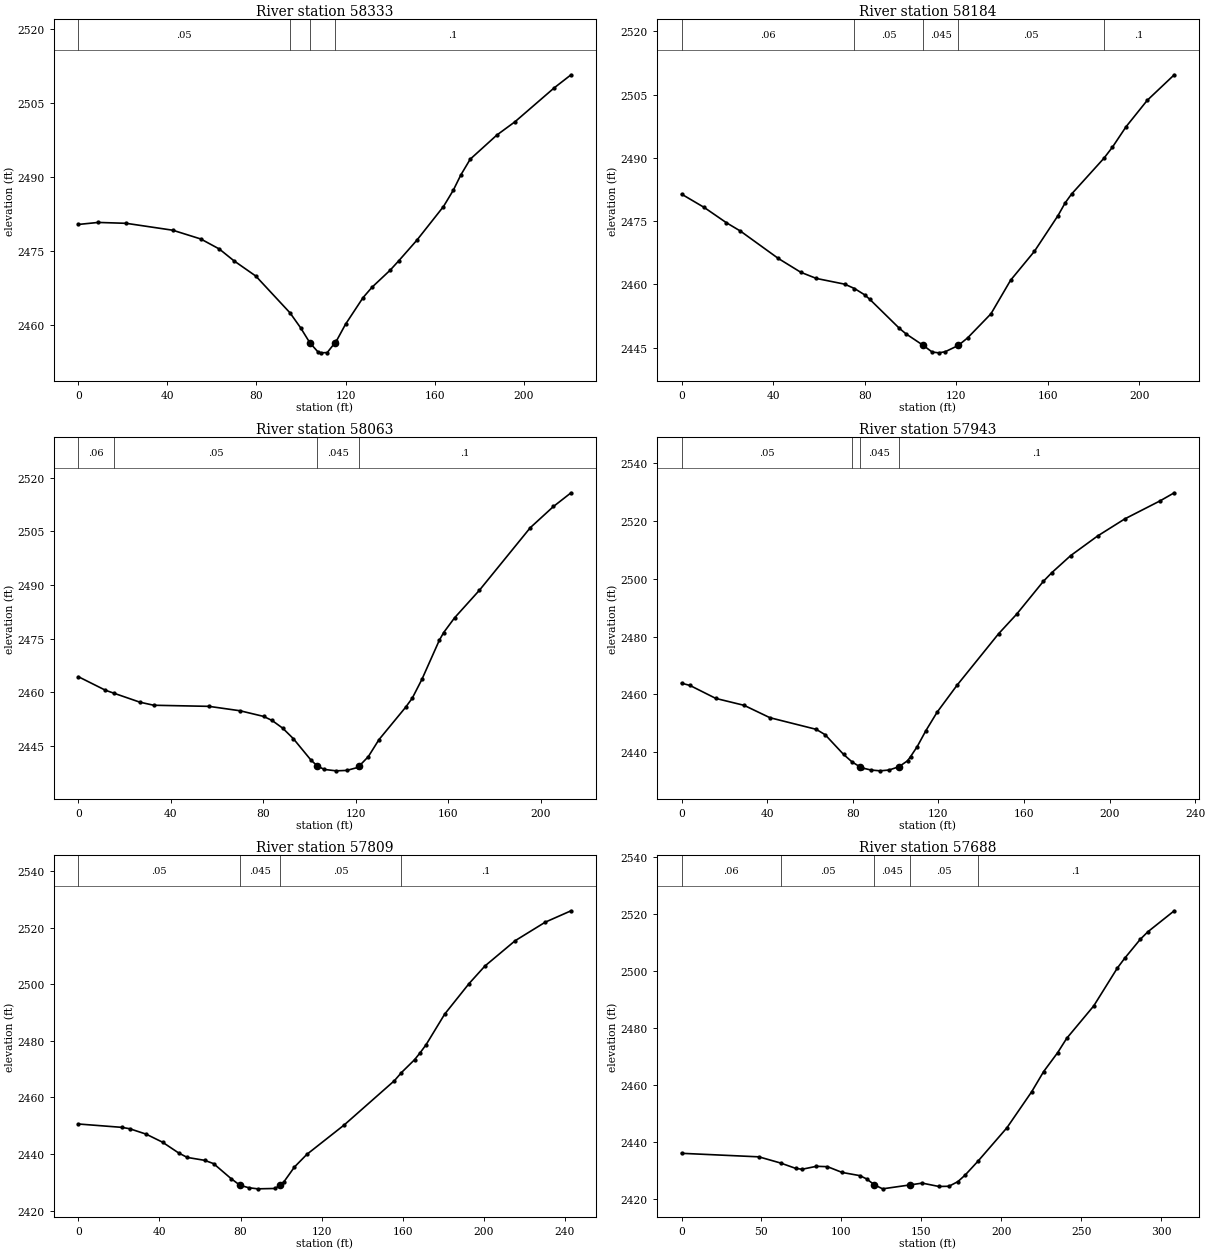
Type RM Length L Ch R = 1 ,58333   ,151.1,148.3,143.1
XS GIS Cut Line= 4
2428774.25569563620875.1374060162428841.05926237620895.869547417
2428912.46997164620888.9588336172428991.94318035 620893.56597615
#Sta/Elev= 30
       0  2480.4     8.9 2480.81    21.5 2480.63    42.4 2479.23      55 2477.45
    63.3 2475.42    69.9 2473.02    79.7 2469.93   95.072462.461    99.8 2459.45
     1042456.376   107.8 2454.45     109 2454.35   111.8 2454.41   115.2 2456.36
   115.8 2456.66     120 2460.15   127.9 2465.57   131.9 2467.66     140  2471.1
     144 2473.07     152 2477.18     164 2484.04   168.4 2487.34   171.8 2490.45
     176 2493.64     188 2498.55   196.1 2501.23   213.8 2508.14   221.3 2510.77
#Mann= 4 ,-1 , 0
       0     .05       0   95.07      .1       0     104    .045       0
   115.2      .1       0
Bank Sta=104,115.2
XS Rating Curve= 0 ,0
Exp/Cntr(USF)=0,0
Exp/Cntr=0.3,0.1

Type RM Length L Ch R = 1 ,58184   ,120,121.2,122.2
XS GIS Cut Line= 4
 2428818.0235497621066.3338211652428892.88961588621045.601679763
2428948.17532628 621004.137396962429009.21996485620973.039184857
#Sta/Elev= 30
       0 2481.41     9.9 2478.25    19.6 2474.63    25.7 2472.66    42.3 2466.16
    52.1 2462.89    58.9 2461.43    71.3 2460.07   75.552459.044      80 2457.55
    82.2 2456.51    95.2  2449.6    98.1 2448.29   105.6 2445.57   109.5 2443.99
   112.4  2443.8   115.2 2444.06   120.9 2445.54     125 2447.34   135.2 2453.05
   143.8 2461.02   154.2 2467.86   164.5 2476.32   167.6 2479.31   170.4 2481.41
  184.582489.919   188.3 2492.55   194.2 2497.35   203.5 2503.64   215.3 2509.69
#Mann= 5 ,-1 , 0
       0     .06       0   75.55     .05       0   105.6    .045       0
   120.9     .05       0  184.58      .1       0
Bank Sta=105.6,120.9
XS Rating Curve= 0 ,0
Exp/Cntr(USF)=0,0
Exp/Cntr=0.3,0.1

Type RM Length L Ch R = 1 ,58063   ,118.9,120.4,121.9
XS GIS Cut Line= 4
2428896.34497278 621172.298099442428961.99675388621138.896316071
2429019.58603555621105.4945327012429081.78245976621067.485606798
#Sta/Elev= 30
       0 2464.39    11.7 2460.61   15.482459.753    26.6 2457.27    32.6 2456.41
    56.5  2456.1      70 2454.86    80.1 2453.29    83.8 2452.15    88.4 2449.99
      93 2447.06   100.6 2441.08   103.42439.404   106.4 2438.46   111.5 2438.07
   116.1 2438.19   120.8 2439.01   121.5 2439.44   125.4 2442.03     130 2446.78
   141.5 2455.81   144.4 2458.37   148.6 2463.66   156.1 2474.55     158 2476.74
   162.7 2480.84   173.5 2488.59   195.5 2506.08   205.5 2511.99   213.1 2515.82
#Mann= 4 ,-1 , 0
       0     .06       0   15.48     .05       0   103.4    .045       0
   121.5      .1       0
Bank Sta=103.4,121.5
XS Rating Curve= 0 ,0
Exp/Cntr(USF)=0,0
Exp/Cntr=0.3,0.1

Type RM Length L Ch R = 1 ,57943   ,134.1,133.7,133.4
XS GIS Cut Line= 4
2428947.02354065621263.2891644812429003.46103668621244.860594346
2429071.41638906621219.5213104112429164.71102536621188.423098308
#Sta/Elev= 30
       0 2463.87     3.9  2463.1      16  2458.6    29.2 2456.21    41.3 2451.92
    62.9  2447.9    67.1 2446.03    75.7 2439.21    79.72436.592    83.22434.989
    84.2 2434.57    88.5 2433.81    92.8 2433.53      97 2433.82   101.62434.968
   105.6 2437.02     107 2438.46   110.1 2441.91   114.1 2447.37   119.4 2453.83
   128.8 2463.25   148.1 2480.97   156.5 2487.71   169.1 2499.18     173 2502.14
   181.8 2508.04   194.4 2514.84   207.1 2520.75   223.6    2527   230.2 2529.79
#Mann= 4 ,-1 , 0
       0     .05       0    79.7      .1       0    83.2    .045       0
   101.6      .1       0
Bank Sta=83.2,101.6
XS Rating Curve= 0 ,0
Exp/Cntr(USF)=0,0
Exp/Cntr=0.3,0.1

Type RM Length L Ch R = 1 ,57809   ,124,121.5,116.2
XS GIS Cut Line= 4
2428989.63960908621365.7980858562429041.46996259621372.708799657
2429118.63960003621340.4588019212429205.02352253621277.110592082
#Sta/Elev= 30
       0 2450.59    21.3 2449.41    25.3 2448.92    33.4 2447.01    41.5 2444.16
    49.5 2440.33    53.7 2438.77    62.3 2437.74    66.7 2436.57    75.3 2431.29
    79.7 2428.93      84 2428.06    88.4 2427.66      97 2427.79    99.5 2428.96
   101.4 2430.16   106.6  2435.4   112.7 2439.85   131.1 2450.24   155.9 2465.92
  159.352468.773   165.8 2473.31   168.6 2475.81   171.5 2478.63   180.7 2489.47
   192.7 2500.25   200.5 2506.44   215.4 2515.39   230.3 2521.97     243 2525.99
#Mann= 4 ,-1 , 0
       0     .05       0    79.7    .045       0    99.5     .05       0
  159.35      .1       0
Bank Sta=79.7,99.5
XS Rating Curve= 0 ,0
Exp/Cntr(USF)=0,0
Exp/Cntr=0.3,0.1

Type RM Length L Ch R = 1 ,57688   ,78.1,80.1,80.6
XS GIS Cut Line= 4
2429010.37175049 621535.110573972429089.84495919621497.101648067
2429164.71102537621424.5391531612429260.30923294621358.887372056
#Sta/Elev= 30
       0 2436.04    48.4  2434.8   62.09 2432.61    71.4 2430.75    75.4 2430.44
    84.4 2431.48    91.3 2431.35   100.5 2429.32   111.6  2428.2   115.8 2427.05
   120.7 2424.97   125.8 2423.57     143 2424.95   150.6 2425.58     161  2424.4
   167.3 2424.47   172.9  2426.1   177.5 2428.43  185.57 2433.33   203.6 2445.01
   219.1 2457.66   226.6 2464.75   235.3 2471.34     241 2476.39   257.9 2487.76
   272.7 2501.07   277.3  2504.5   287.1 2511.19   291.9 2513.84   308.3 2521.16
#Mann= 5 ,-1 , 0
       0     .06       0   62.09     .05       0   120.7    .045       0
     143     .05       0  185.57      .1       0
Bank Sta=120.7,143
XS Rating Curve= 0 ,0
Exp/Cntr(USF)=0,0
Exp/Cntr=0.3,0.1

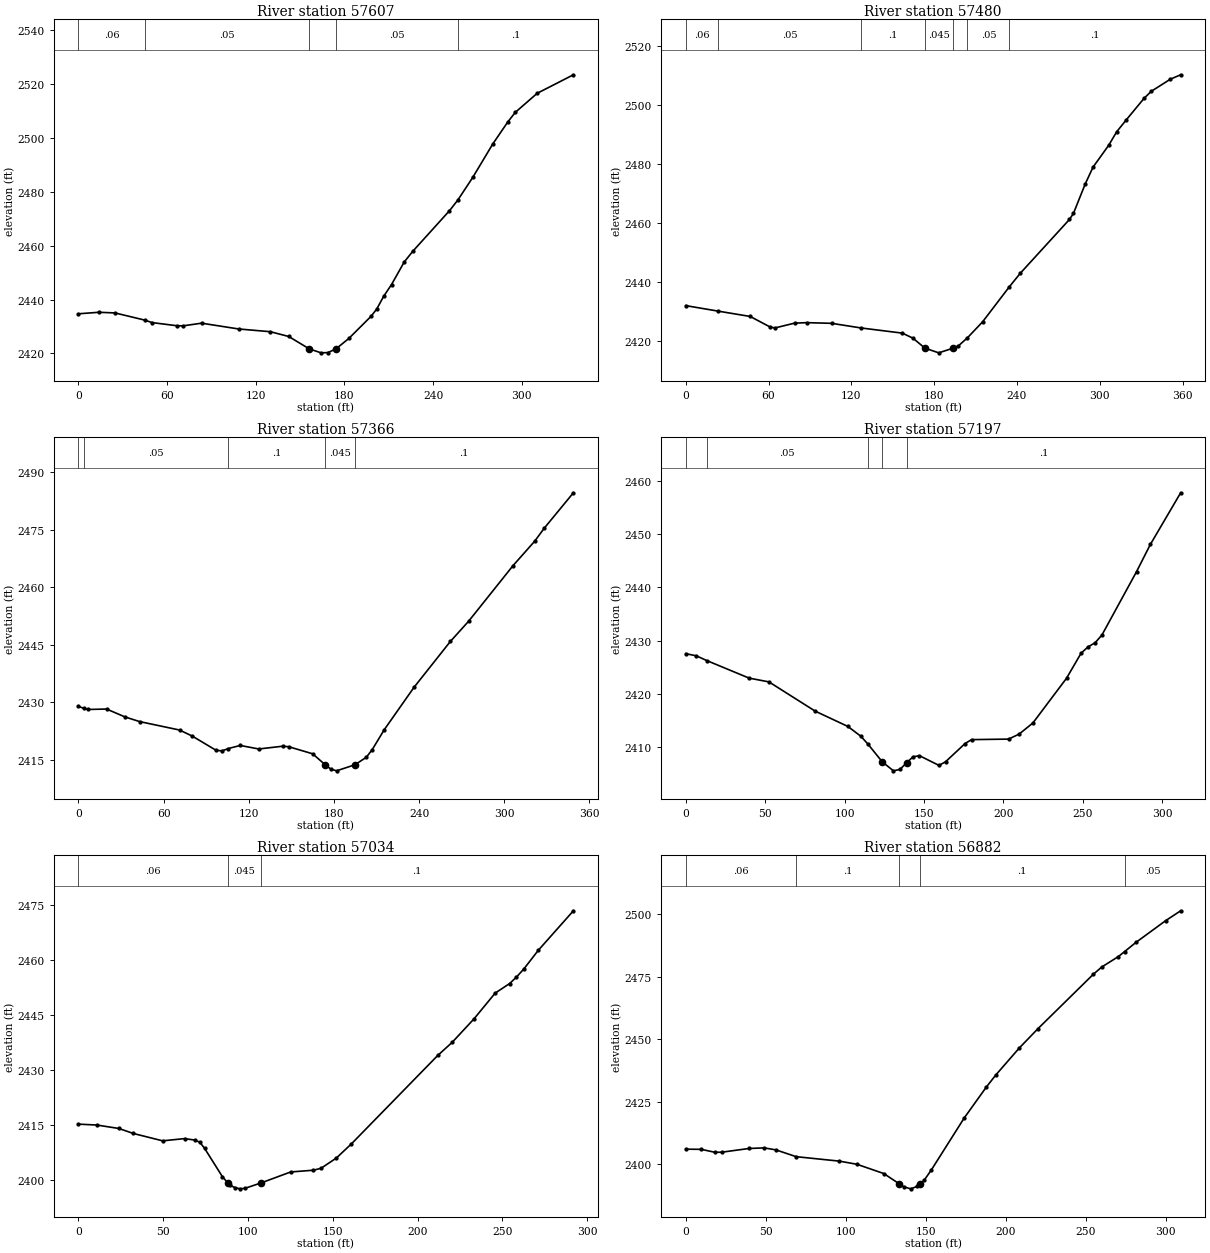
Type RM Length L Ch R = 1 ,57607   ,127.6,127.8,127.6
XS GIS Cut Line= 4
2429031.10389189 621568.512357342429140.52352706 621535.11057397
2429219.99673577621485.5837917332429322.50565715 621410.71772556
#Sta/Elev= 30
       0  2434.7    13.8 2435.26    24.7 2435.02   44.872432.353    49.8 2431.43
    66.5 2430.27    70.7 2430.21    83.3 2431.21   108.4 2429.06   129.9 2428.04
   142.3 2426.27   156.22421.667   164.2 2420.19   168.9 2420.29   174.32421.661
     183 2425.53     198 2433.74   201.9 2436.48   206.6 2441.21   211.9 2445.57
   220.5 2453.95   226.3 2457.93   251.1 2472.98  256.682476.884   266.9 2485.39
   280.4 2497.77   290.7 2506.06   295.7 2509.56   310.5 2516.63     335 2523.51
#Mann= 5 ,-1 , 0
       0     .06       0   44.87     .05       0   156.2    .045       0
   174.3     .05       0  256.68      .1       0
Bank Sta=156.2,174.3
XS Rating Curve= 0 ,0
Exp/Cntr(USF)=0,0
Exp/Cntr=0.3,0.1

Type RM Length L Ch R = 1 ,57480   ,111.5,113.6,116.4
XS GIS Cut Line= 4
2429076.02353159621706.7266333522429208.47887944621641.074852246
2429279.88958871621597.3069981762429359.36279742621498.253433701
#Sta/Elev= 30
       0 2432.07   23.272430.214    46.7 2428.39    61.1 2424.82    64.6 2424.49
    78.9 2426.13    87.9 2426.29   105.7 2426.06  127.212424.476   156.9 2422.74
   164.6 2421.03   173.32417.645   183.3 2416.05   193.72417.634   197.4 2418.35
  204.132421.165   215.1 2426.58  234.452438.452   242.5  2443.1     278 2461.29
   280.9 2463.34   289.4 2473.29   295.1 2479.05   306.5 2486.49   312.2 2491.02
   319.2 2495.09   332.1  2502.4   337.3 2504.77   351.2  2508.9   358.6 2510.38
#Mann= 7 ,-1 , 0
       0     .06       0   23.27     .05       0  127.21      .1       0
   173.3    .045       0   193.7      .1       0  204.13     .05       0
  234.45      .1       0
Bank Sta=173.3,193.7
XS Rating Curve= 0 ,0
Exp/Cntr(USF)=0,0
Exp/Cntr=0.3,0.1

Type RM Length L Ch R = 1 ,57366   ,165.1,169.5,176.6
XS GIS Cut Line= 4
2429108.27352933621791.9587702252429233.81816337621743.583773621
2429319.05030025621715.9409184192429436.53243486621674.476635615
#Sta/Elev= 30
       0  2428.9    4.132428.365     6.9 2428.11    19.8 2428.22    32.7 2426.17
      43 2424.95    71.2 2422.74    80.1 2421.17      97 2417.43   101.2  2417.3
  105.622417.908     114 2418.71     127 2417.79   143.9 2418.51   148.1 2418.38
     165 2416.53   173.82413.674   177.6 2412.58   181.8 2412.08   194.82413.667
   202.8 2415.62     207 2417.64   215.4  2422.8   236.5 2433.94     262 2445.86
   274.9 2451.16   306.2 2465.69   321.4 2472.04   328.2 2475.47   348.7  2484.7
#Mann= 5 ,-1 , 0
       0     .06       0    4.13     .05       0  105.62      .1       0
   173.8    .045       0   194.8      .1       0
Bank Sta=173.8,194.8
XS Rating Curve= 0 ,0
Exp/Cntr(USF)=0,0
Exp/Cntr=0.3,0.1

Type RM Length L Ch R = 1 ,57197   ,167.7,162.8,155.7
XS GIS Cut Line= 4
2429116.33602876621899.0748341342429206.17530817621873.735550199
2429299.46994448621894.4676916012429412.34493655621846.092694997
#Sta/Elev= 30
       0 2427.53     6.7 2427.12   13.322426.219    39.9 2422.93    52.4 2422.22
    81.5 2416.72   102.1 2413.84   110.3 2411.99  114.672410.545   123.72407.205
   130.8 2405.49   134.9 2405.76   139.22407.036   143.1 2408.12   147.2 2408.34
   159.5 2406.51   163.6 2407.19   175.9 2410.62     180 2411.36   203.3 2411.46
   209.9 2412.39   218.6 2414.48   239.8  2422.9     249 2427.62   253.4 2428.81
   257.8 2429.58   262.1 2431.03   283.9 2442.95   292.6 2448.07   311.7 2457.79
#Mann= 5 ,-1 , 0
       0     .06       0   13.32     .05       0  114.67      .1       0
   123.7    .045       0   139.2      .1       0
Bank Sta=123.7,139.2
XS Rating Curve= 0 ,0
Exp/Cntr(USF)=0,0
Exp/Cntr=0.3,0.1

Type RM Length L Ch R = 1 ,57034   ,150,151.4,150.7
XS GIS Cut Line= 4
2429164.71102537622074.146250416 2429224.6038783622049.958752114
2429312.13958644622006.1908980432429434.22886359621963.574829606
#Sta/Elev= 30
       0 2415.23    10.8 2414.99    23.8 2414.05    32.4 2412.68    49.6 2410.68
    62.6 2411.29    68.5 2410.89    71.5 2410.31    74.4  2408.6    84.9 2400.87
    88.12399.198    89.3 2398.59    92.3 2397.92    95.3 2397.59    98.3 2397.75
   107.62399.194   125.1 2402.19   138.5 2402.67     143 2403.19     152 2405.97
   160.9 2409.84   211.8 2433.95   220.3 2437.52   233.2 2443.94   245.7 2450.97
   254.2 2453.57   258.2 2455.31   262.7 2457.61   271.1 2462.63   291.8 2473.41
#Mann= 3 ,-1 , 0
       0     .06       0    88.1    .045       0   107.6      .1       0
Bank Sta=88.1,107.6
XS Rating Curve= 0 ,0
Exp/Cntr(USF)=0,0
Exp/Cntr=0.3,0.1

Type RM Length L Ch R = 1 ,56882   ,165.2,168,170.2
XS GIS Cut Line= 4
2429209.63066507622196.2355275592429305.22887264 622162.83374419
2429378.94315318622139.7980315212429494.12171653622077.601607316
#Sta/Elev= 30
       0    2406     9.7 2405.92    18.1 2404.76    22.4 2404.77    39.6 2406.27
      49  2406.5    56.3 2405.72   69.082402.983    96.1  2401.2     107 2399.95
   123.8 2396.24   133.42392.156   136.4 2390.92   140.6 2390.12   144.8 2391.12
   146.52392.133     149 2393.52   153.5 2397.64   174.1 2418.49   187.9 2430.83
   193.8 2435.65   208.5 2446.46   220.3 2454.27   254.8 2475.97   260.1 2478.88
   270.5 2483.07  274.292485.012   281.4  2488.7     300 2497.41   309.4 2501.37
#Mann= 5 ,-1 , 0
       0     .06       0   69.08      .1       0   133.4    .045       0
   146.5      .1       0  274.29     .05       0
Bank Sta=133.4,146.5
XS Rating Curve= 0 ,0
Exp/Cntr(USF)=0,0
Exp/Cntr=0.3,0.1

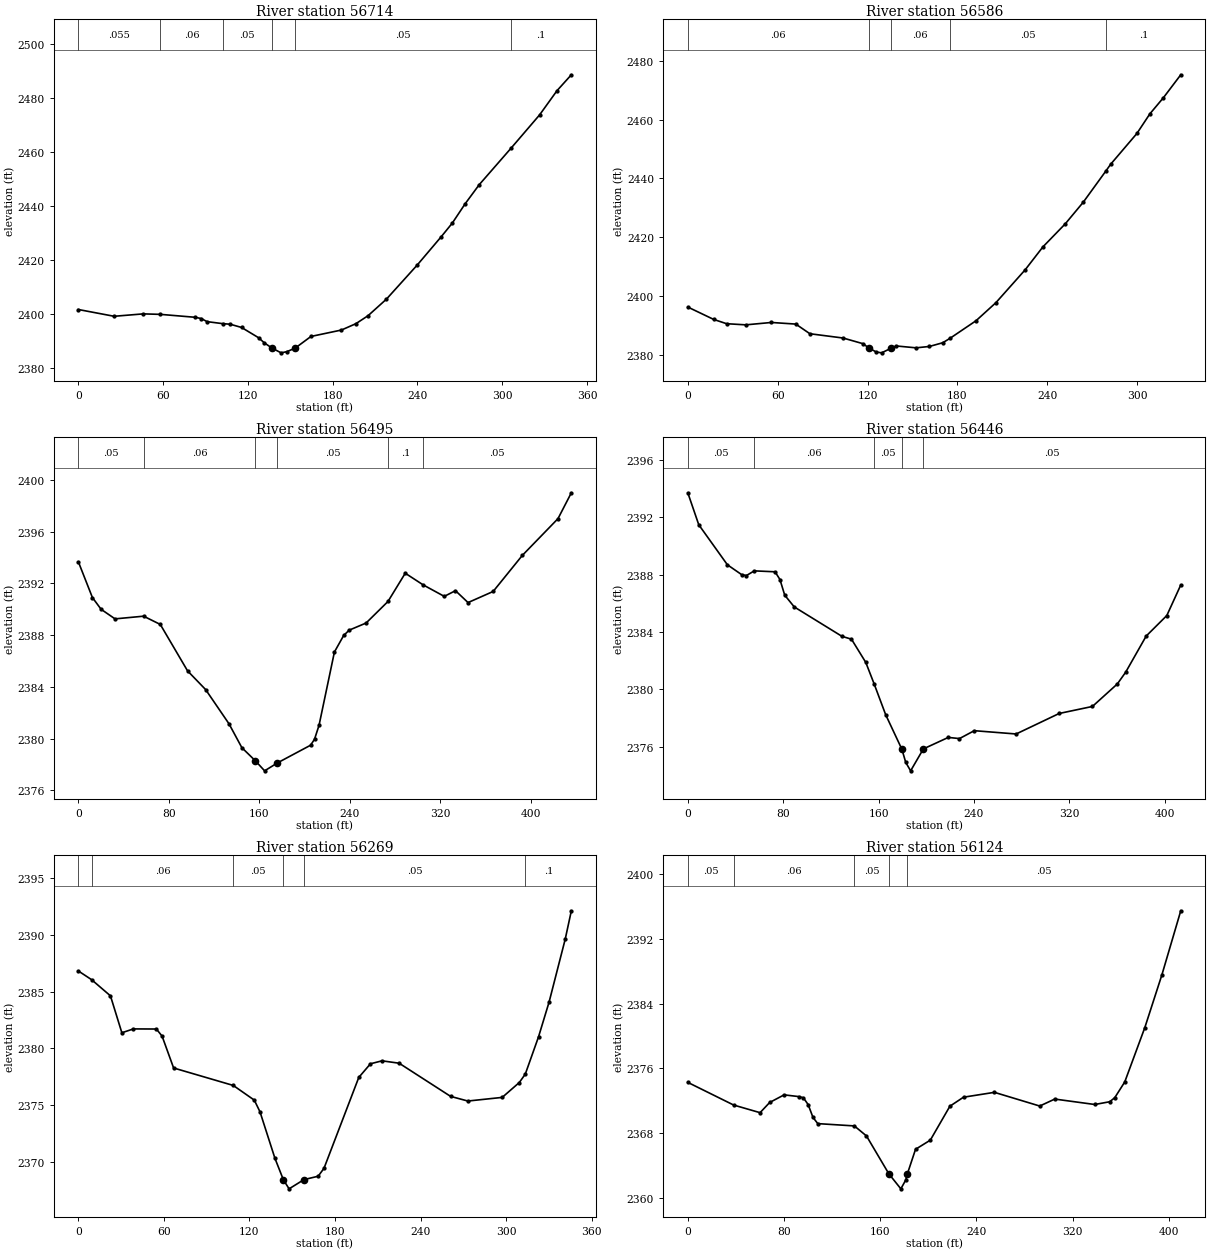
Type RM Length L Ch R = 1 ,56714   ,132.8,128.9,124.6
XS GIS Cut Line= 4
2429198.11280873622289.5301638672429300.62173011622313.717662169
2429381.24672445622319.4765903362429532.13064243622258.431951764
#Sta/Elev= 30
       0 2401.61    25.3  2399.1    45.9 2399.99   58.052399.813    82.8 2398.72
      87 2398.25    91.1 2397.11  102.082396.373   107.5 2396.15   115.5 2394.95
   127.5 2391.15   131.5 2389.28     1372387.301   143.5 2385.53   147.6 2385.97
   153.52387.303   164.6 2391.61   186.2    2394   196.4 2396.35     205 2399.31
     218 2405.45   239.6 2417.99   256.8 2428.63   264.6 2433.66   273.8 2440.91
   283.7 2447.95  306.122461.435   326.4 2473.84   338.8 2482.88   348.9 2488.75
#Mann= 6 ,-1 , 0
       0    .055       0   58.05     .06       0  102.08     .05       0
     137    .045       0   153.5     .05       0  306.12      .1       0
Bank Sta=137,153.5
XS Rating Curve= 0 ,0
Exp/Cntr(USF)=0,0
Exp/Cntr=0.3,0.1

Type RM Length L Ch R = 1 ,56586   ,79.1,90.4,95.9
XS GIS Cut Line= 4
2429254.55030477622487.6372928172429330.56815658622458.842651981
2429436.53243485 622408.164084112429552.86278383622349.423016805
#Sta/Elev= 30
       0 2396.32    17.3 2392.11    25.9 2390.66    38.7 2390.27    55.8 2391.08
    72.1 2390.53    81.5 2387.25   103.7 2385.79     117 2383.86   120.7 2382.47
   125.8 2381.04   129.4 2380.76   135.4 2382.25   139.1  2383.1   152.4 2382.46
   161.3 2382.93   170.2 2384.19  175.07  2385.7   192.4 2391.66   205.7 2397.81
   225.2 2408.96   237.1 2416.78     252  2424.6     264 2431.94   279.12442.543
   282.3 2444.84   299.8 2455.29   308.5 2461.98   317.5 2467.44   329.1 2475.24
#Mann= 5 ,-1 , 0
       0     .06       0   120.7    .045       0   135.4     .06       0
  175.07     .05       0   279.1      .1       0
Bank Sta=120.7,135.4
XS Rating Curve= 0 ,0
Exp/Cntr(USF)=0,0
Exp/Cntr=0.5,0.3

Type RM Length L Ch R = 1 ,56495   ,48.6,49.5,50.3
XS GIS Cut Line= 4
2429270.36803135622503.3521011322429401.61803132622498.143767804
2429495.18205228622504.887778372 2429665.5937258622628.482309446
#Sta/Elev= 30
       0 2393.66    12.4  2390.9    20.1 2389.99    32.4 2389.25   57.642389.458
    72.4 2388.82    96.5 2385.23   112.5 2383.78   133.1 2381.14   144.5 2379.29
   156.5 2378.27   164.6  2377.5   175.92378.112   205.2 2379.48   208.7 2379.94
   212.7 2381.02   226.3 2386.69   234.5 2387.97   239.4 2388.38   254.3 2388.93
  273.642390.596   288.9 2392.78   304.7 2391.88   323.4 2390.99   333.3 2391.43
   344.4 2390.51   366.6 2391.37   392.4 2394.16   423.9    2397   435.7    2399
#Mann= 6 ,-1 , 0
       0     .05       0   57.64     .06       0   156.5    .045       0
   175.9     .05       0  273.64      .1       0   304.7     .05       0
#XS Ineff= 2 , 0
           146.5  2378.5   185.9          2378.5
Permanent Ineff=
       F       F
Bank Sta=156.5,175.9
XS Rating Curve= 0 ,0
Exp/Cntr(USF)=0,0
Exp/Cntr=0.5,0.3

Type RM Length L Ch R = 1 ,56446   ,181.4,176.9,181.2
XS GIS Cut Line= 4
2429277.57289249 622536.468420582429428.61455914622529.523976117
2429492.85067022622549.4892539082429652.57289246622661.468420565
#Sta/Elev= 30
       0 2393.71     9.2 2391.48    33.2 2388.69    45.2    2388    49.2 2387.94
   55.772388.265    73.2  2388.2    77.3 2387.66    81.3 2386.57    89.3 2385.75
   129.3  2383.7   137.3  2383.5   149.3 2381.88  156.252380.394     166 2378.23
   179.6 2375.82   182.8 2374.91   186.9 2374.32   197.6 2375.85   218.5 2376.65
   227.9 2376.57   240.3 2377.12   275.4 2376.89   311.5 2378.32   339.4 2378.81
   360.3 2380.38   367.3  2381.2   384.5 2383.72   401.8 2385.15   413.5 2387.28
#Mann= 5 ,-1 , 0
       0     .05       0   55.77     .06       0  156.25     .05       0
   179.6    .045       0   197.6     .05       0
Bank Sta=179.6,197.6
XS Rating Curve= 0 ,0
Exp/Cntr(USF)=0,0
Exp/Cntr=0.5,0.3

Type RM Length L Ch R = 1 ,56269   ,147.3,144.4,137
XS GIS Cut Line= 4
2429352.45208362622709.9319200662429463.02350447622696.110492468
2429557.46992639622714.5390626192429695.10761467 622702.26703167
#Sta/Elev= 30
       0 2386.82    9.262386.055    22.5 2384.63    30.5 2381.38    38.6 2381.72
    54.7 2381.71    58.7 2381.09    66.8 2378.28  108.642376.743   123.4 2375.45
   127.4 2374.42   137.9 2370.32   143.8 2368.44   147.8 2367.64   158.2 2368.45
   168.2 2368.75   172.3 2369.45   196.7 2377.45   204.9 2378.65     213 2378.91
     225  2378.7   261.1 2375.78   273.2 2375.37   297.3 2375.69   309.3    2377
   313.52377.743   322.8 2381.03   330.2 2384.09   341.5 2389.62   345.8 2392.12
#Mann= 6 ,-1 , 0
       0     .05       0    9.26     .06       0  108.64     .05       0
   143.8    .045       0   158.2     .05       0   313.5      .1       0
Bank Sta=143.8,158.2
XS Rating Curve= 0 ,0
Exp/Cntr(USF)=0,0
Exp/Cntr=0.3,0.1

Type RM Length L Ch R = 1 ,56124   ,238.4,238.7,237.6
XS GIS Cut Line= 4
2429346.69315545622851.6015529812429467.63064696622851.601552981
2429574.74671087622829.7176259452429747.51455588622780.190843708
#Sta/Elev= 30
       0 2374.27   38.112371.474    60.1 2370.53    68.1 2371.79    80.1 2372.73
    92.1 2372.52    96.1 2372.37   100.1 2371.53   104.1 2369.95   108.1 2369.18
  138.512368.896   148.6 2367.66   167.22362.989   177.2 2361.13   181.3 2362.23
   182.62362.968   189.4 2366.01   201.7 2367.14     218 2371.33   229.3 2372.44
     255 2373.04   292.7 2371.35   305.2 2372.21   338.5 2371.54   350.9 2371.88
   355.1 2372.38   363.4 2374.32   380.1 2381.03   394.3 2387.54     410 2395.45
#Mann= 5 ,-1 , 0
       0     .05       0   38.11     .06       0  138.51     .05       0
   167.2    .045       0   182.6     .05       0
Bank Sta=167.2,182.6
XS Rating Curve= 0 ,0
Exp/Cntr(USF)=0,0
Exp/Cntr=0.3,0.1