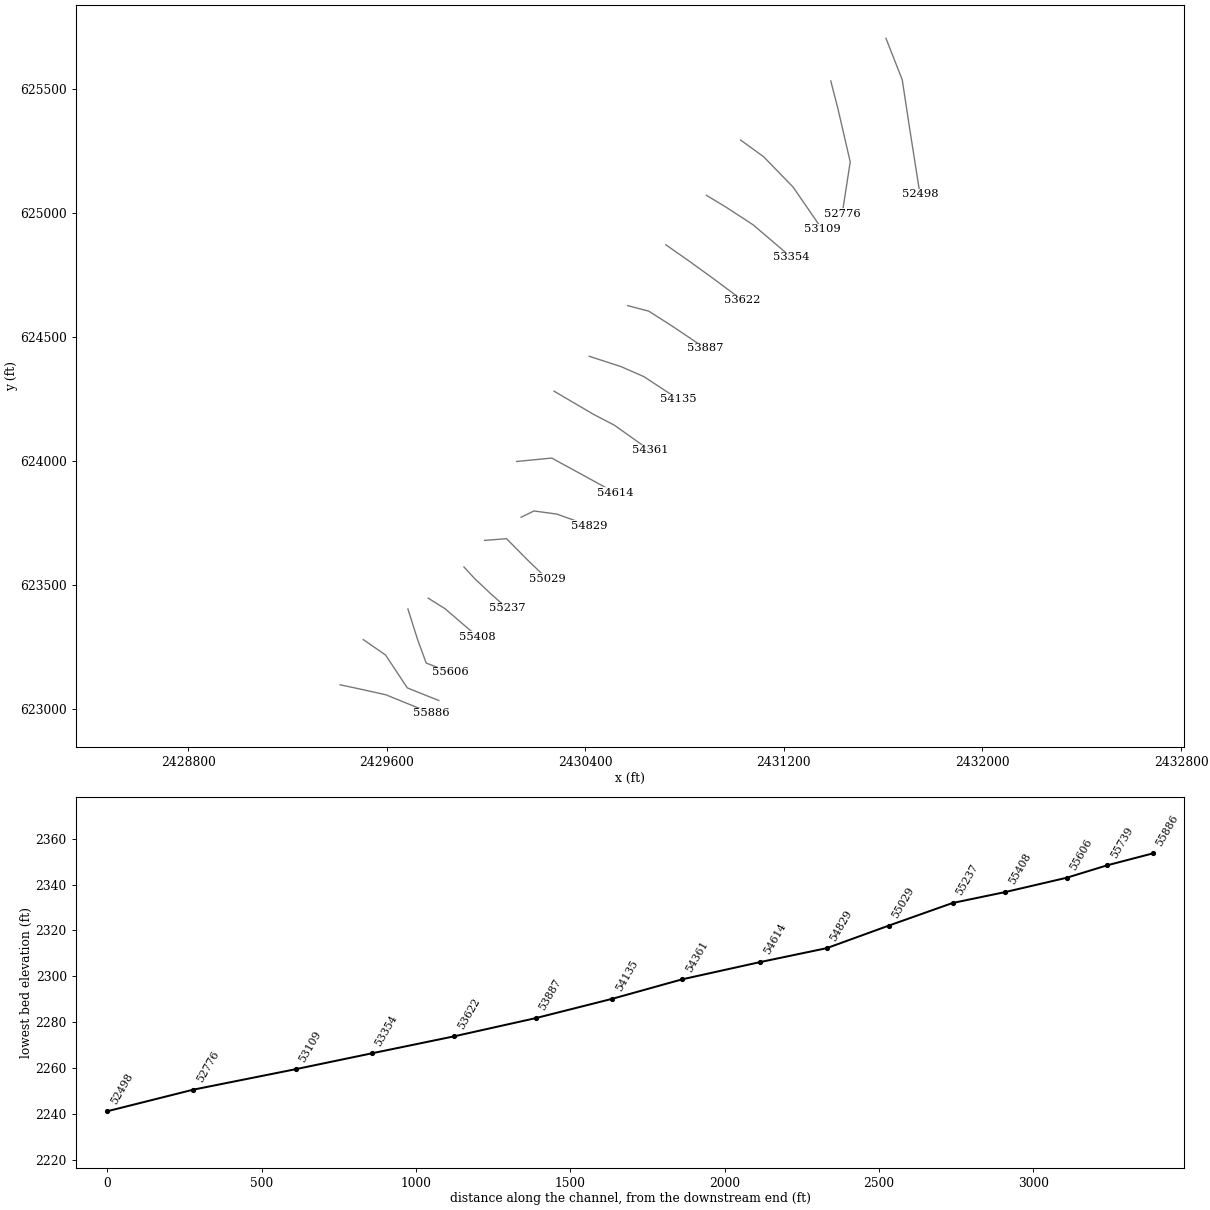
HEC-RAS study REEDSCK.prj: REEDSCK

--- REEDSCK.g01 (geometry) --- (continued)

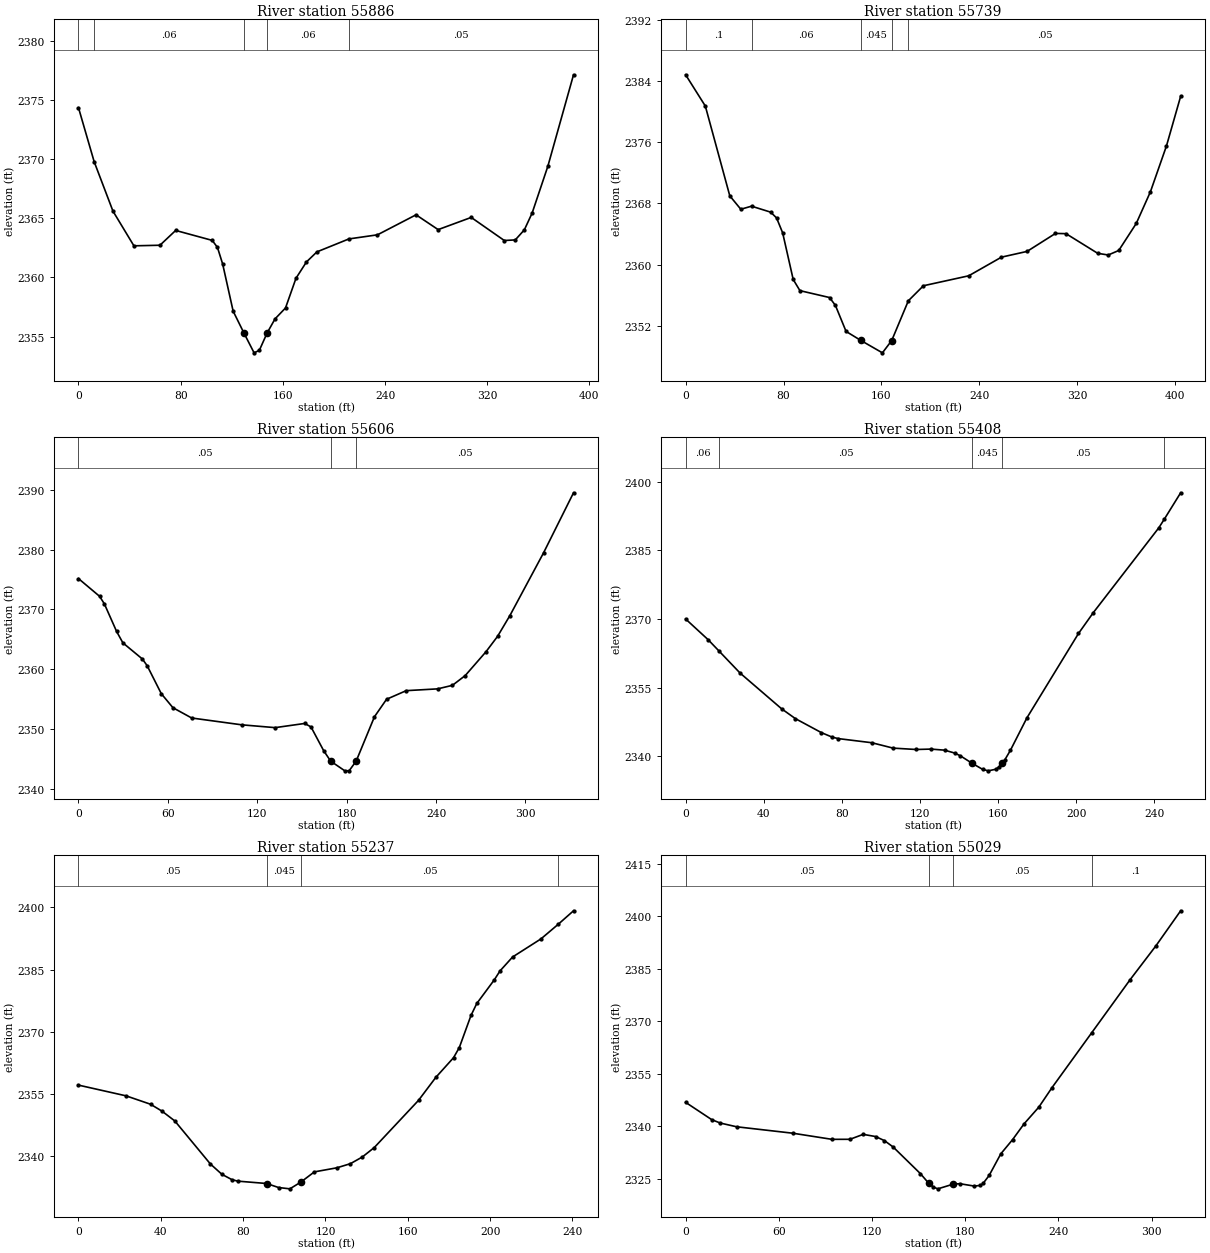
Type RM Length L Ch R = 1 ,55886   ,155.7,147.1,139.1
XS GIS Cut Line= 4
2429412.34493655623098.0836785352429509.09492976623077.351537133
 2429596.6306379623057.7711813652429780.91633925622982.905115192
#Sta/Elev= 30
       0 2374.34   12.282369.776      27  2365.6    43.4 2362.67    63.8 2362.72
    76.1 2363.97   104.7 2363.13   108.8 2362.54   112.9 2361.13   121.1 2357.15
   129.52355.313   137.5 2353.63   141.6 2353.84   147.7 2355.31   153.9  2356.5
   162.1 2357.42   170.3 2359.93   178.5 2361.31   186.7 2362.16  211.762363.254
   234.1  2363.6   264.3 2365.29   281.6 2364.04   307.5 2365.07   333.4 2363.12
     342 2363.17   349.1 2364.02   355.2 2365.44   367.5 2369.39   387.6 2377.12
#Mann= 5 ,-1 , 0
       0     .05       0   12.28     .06       0   129.5    .045       0
   147.7     .06       0  211.76     .05       0
Bank Sta=129.5,147.7
XS Rating Curve= 0 ,0
Exp/Cntr(USF)=0,0
Exp/Cntr=0.3,0.1

Type RM Length L Ch R = 1 ,55739   ,135.4,132.1,130.1
XS GIS Cut Line= 4
2429505.63957286623280.0658086162429595.47885227623217.869384411
2429683.01456041623085.4140365672429809.71098009623034.735468696
#Sta/Elev= 30
       0 2384.82    16.1 2380.73    36.1 2368.99    45.1 2367.24   53.852367.643
    69.5 2366.86    74.3 2366.11    79.3 2364.15    87.9 2358.06    93.4  2356.6
   117.6  2355.7   122.4 2354.67   131.1 2351.27   143.22350.089   160.8 2348.47
   168.42350.079  181.992355.275   194.3 2357.24   231.3 2358.54   258.1 2360.98
     279 2361.73   302.2 2364.08   310.8 2364.05   336.7 2361.48   345.3 2361.26
   353.9 2361.85   368.2 2365.38   379.8 2369.53   392.9 2375.52   404.5 2382.01
#Mann= 5 ,-1 , 0
       0      .1       0   53.85     .06       0   143.2    .045       0
   168.4     .06       0  181.99     .05       0
Bank Sta=143.2,168.4
XS Rating Curve= 0 ,0
Exp/Cntr(USF)=0,0
Exp/Cntr=0.3,0.1

Type RM Length L Ch R = 1 ,55606   ,193.4,198.6,201.8
XS GIS Cut Line= 4
2429685.31813168623403.3068713932429724.47884321623280.065808616
2429759.03241221623185.6193866752429854.63061979623148.762246405
#Sta/Elev= 30
       0 2375.14    14.2 2372.17    17.4  2370.9    25.6  2366.3    29.8  2364.4
    42.9  2361.7    46.1 2360.58    55.6  2355.9    63.4 2353.56      76 2351.84
   109.6  2350.7     132 2350.23   151.9 2350.93   156.1 2350.34   164.6 2346.37
   169.32344.628   178.8 2343.01   181.7 2343.03   186.42344.635   198.7 2352.06
   206.8 2354.97     220 2356.41   241.1 2356.71     251  2357.3   259.6 2358.93
   273.5  2362.9   281.3 2365.48   289.6 2368.96   312.2 2379.45   332.3 2389.48
#Mann= 3 ,-1 , 0
       0     .05       0   169.3    .045       0   186.4     .05       0
Bank Sta=169.3,186.4
XS Rating Curve= 0 ,0
Exp/Cntr(USF)=0,0
Exp/Cntr=0.3,0.1

Type RM Length L Ch R = 1 ,55408   ,171.5,171.2,170.5
XS GIS Cut Line= 3
2429767.09491165623447.0747254642429835.05026402623404.458657027
2429966.35382623623291.583664951
#Sta/Elev= 30
       0    2370    11.5 2365.48   17.252362.921    27.9 2358.16    49.2 2350.33
    56.2  2348.2    69.5 2345.14    75.1 2344.14    78.2 2343.83    95.3 2342.93
   106.2 2341.75     118 2341.45   125.6 2341.54   132.6  2341.3   137.8 2340.66
   140.7 2340.05   146.62338.443     152 2337.11   154.9 2336.78   158.9 2337.14
   160.5 2337.69     1622338.432   163.4 2339.19   166.2 2341.23   174.7 2348.37
   201.1 2366.83   208.7  2371.4   242.2 2389.94  245.092391.877   253.4 2397.61
#Mann= 5 ,-1 , 0
       0     .06       0   17.25     .05       0   146.6    .045       0
     162     .05       0  245.09      .1       0
Bank Sta=146.6,162
XS Rating Curve= 0 ,0
Exp/Cntr(USF)=0,0
Exp/Cntr=0.3,0.1

Type RM Length L Ch R = 1 ,55237   ,207.5,207.4,206.9
XS GIS Cut Line= 4
2429911.06811583623572.619359508  2429951.380613623528.851505437
2430019.33596537623464.3515099652430084.98774648623406.762228294
#Sta/Elev= 30
       0 2357.06    23.1 2354.47      35 2352.44    40.6 2350.76    46.8  2348.4
    64.1 2337.99    69.7 2335.49    74.6  2334.2    77.4 2333.85    91.4 2333.28
    97.2 2332.31   102.7 2331.99     108 2333.61   114.6 2336.09   125.5 2337.07
   132.1 2338.07   137.9 2339.69   143.7 2341.97   165.2 2353.38   173.6 2358.93
   182.2 2363.68     185 2366.12   190.7 2373.91   193.5 2376.79     202  2382.5
   204.8 2384.67   210.9 2388.03   224.7 2392.41  232.972395.893   240.5  2399.2
#Mann= 4 ,-1 , 0
       0     .05       0    91.4    .045       0     108     .05       0
  232.97      .1       0
Bank Sta=91.4,108
XS Rating Curve= 0 ,0
Exp/Cntr(USF)=0,0
Exp/Cntr=0.3,0.1

Type RM Length L Ch R = 1 ,55029   ,194.7,200.3,206.2
XS GIS Cut Line= 4
2429993.99668143623679.7354234162430082.68417521623686.646137217
2430172.52345462623595.6550721762430246.23773516623525.396148537
#Sta/Elev= 30
       0 2346.81    16.8 2341.87    22.2 2340.91    32.8 2339.83      69 2337.99
    94.2 2336.24   105.8 2336.25   114.3 2337.66   122.3 2337.04     128 2335.87
   133.6 2334.05   151.1 2326.46   156.4 2323.74   159.5 2322.59   162.4 2322.09
   172.22323.423   176.5 2323.56   185.8 2322.88   189.8 2323.07   191.5 2323.63
   195.4 2325.91   202.9 2332.09   210.5 2336.16   217.9 2340.68   227.4 2345.45
   235.9 2351.04  261.36 2366.66   286.2  2381.9   302.8 2391.57   318.7 2401.57
#Mann= 4 ,-1 , 0
       0     .05       0   156.4    .045       0   172.2     .05       0
  261.36      .1       0
Bank Sta=156.4,172.2
XS Rating Curve= 0 ,0
Exp/Cntr(USF)=0,0
Exp/Cntr=0.3,0.1

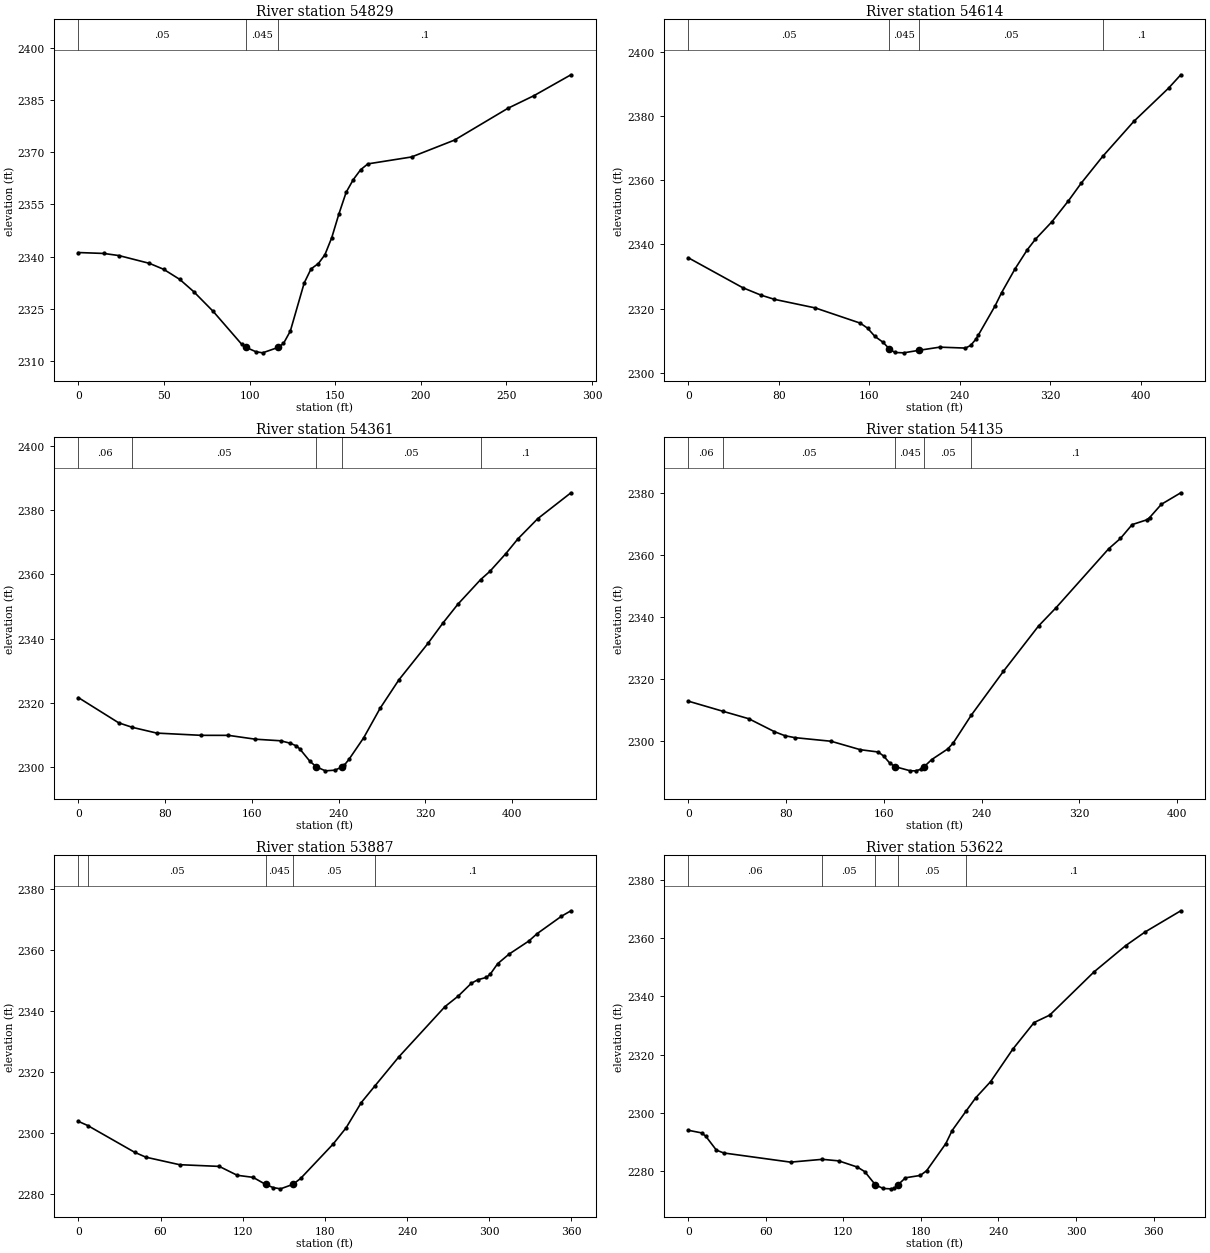
Type RM Length L Ch R = 1 ,54829   ,217.3,214.6,207.6
XS GIS Cut Line= 4
2430141.42524251623773.0300597242430193.25559602 623798.36934366
2430285.39844669623785.6997016922430414.39843764623739.628276355
#Sta/Elev= 30
       0 2341.15    14.8 2340.89    23.7 2340.28    41.5 2338.04    49.8 2336.33
    59.2 2333.43    67.3 2329.93    78.8 2324.19    95.5  2314.7      982313.846
   103.6 2312.63   107.6 2312.29   116.72313.851   119.8 2314.98   123.8 2318.55
   131.9 2332.39   135.9 2336.44   140.2 2337.99     144 2340.52     148 2345.44
   152.1 2352.14   156.4 2358.48   160.6 2362.16   164.9    2365   169.1 2366.66
   194.6 2368.65   219.7 2373.51     251 2382.69   266.1 2386.29   287.7  2392.3
#Mann= 3 ,-1 , 0
       0     .05       0      98    .045       0   116.7      .1       0
Bank Sta=98,116.7
XS Rating Curve= 0 ,0
Exp/Cntr(USF)=0,0
Exp/Cntr=0.3,0.1

Type RM Length L Ch R = 1 ,54614   ,252.5,253.2,248.6
XS GIS Cut Line= 4
2430122.99667238623997.6282582432430264.66630529624011.449685844
2430391.36272497623942.3425478382430521.51450155623870.931838566
#Sta/Elev= 30
       0 2335.85      48 2326.55    64.1 2324.23    76.1  2322.9   112.3 2320.22
   151.9  2315.5   158.4 2313.94   164.9 2311.37     172 2309.57   177.82307.441
   182.6 2306.36   190.3 2306.25   203.9 2307.04   222.2 2308.02   244.9 2307.73
   249.5 2308.56   254.1 2310.49   256.3 2311.79   271.1 2320.88   276.8 2324.96
   288.7 2332.38   299.6 2338.37   306.7 2341.59   321.2 2347.01   335.9 2353.57
   347.1 2359.02  366.082367.356   393.6 2378.26   424.3 2388.61   435.1 2392.77
#Mann= 4 ,-1 , 0
       0     .05       0   177.8    .045       0   203.9     .05       0
  366.08      .1       0
Bank Sta=177.8,203.9
XS Rating Curve= 0 ,0
Exp/Cntr(USF)=0,0
Exp/Cntr=0.3,0.1

Type RM Length L Ch R = 1 ,54361   ,225,226.7,226.7
XS GIS Cut Line= 4
2430273.88059036624280.9675240672430432.82700777624187.672887759
2430516.90735901624143.9050336892430659.72877756624042.547897947
#Sta/Elev= 30
       0 2321.57    37.2 2313.69   49.742312.286    72.3 2310.49   113.2 2309.79
   138.4 2309.78   163.3 2308.58   186.5 2308.09   195.5 2307.32   201.1 2306.47
   204.1 2305.58   213.5 2301.69   219.52299.944   227.8 2298.71   236.7 2298.92
   243.12299.949   245.1 2300.43   249.6 2302.33   263.1 2309.03   278.2 2318.21
   295.5 2327.08   322.3 2338.46   336.1 2344.81     350 2350.73  370.992358.415
   379.4 2360.94   394.2 2366.51   405.3  2371.1   423.6 2377.41   454.2 2385.48
#Mann= 5 ,-1 , 0
       0     .06       0   49.74     .05       0   219.5    .045       0
   243.1     .05       0  370.99      .1       0
Bank Sta=219.5,243.1
XS Rating Curve= 0 ,0
Exp/Cntr(USF)=0,0
Exp/Cntr=0.3,0.1

Type RM Length L Ch R = 1 ,54135   ,249.3,247.6,246.1
XS GIS Cut Line= 4
2430415.55022327624421.4853713452430543.39842858624380.021088542
2430635.54127925624339.7085913722430776.05912653624247.565740697
#Sta/Elev= 30
       0 2312.76   28.672309.445    49.6 2307.06    70.6 2302.87    79.1 2301.58
    87.2 2300.95   116.9 2299.78   140.8 2297.05   155.5  2296.3   159.9 2294.99
   165.1 2292.63   169.42291.547   181.7 2290.22   186.1 2290.21   190.4 2290.73
     193 2291.54   199.2 2293.85   212.3 2297.28   216.8  2299.2   231.62308.221
   257.9 2322.41   286.6 2337.05     301 2342.99     344 2362.04   353.6 2365.37
   363.2 2369.85   375.1 2371.39   377.5 2372.13   387.1 2376.42     403 2380.15
#Mann= 5 ,-1 , 0
       0     .06       0   28.67     .05       0   169.4    .045       0
     193     .05       0   231.6      .1       0
Bank Sta=169.4,193
XS Rating Curve= 0 ,0
Exp/Cntr(USF)=0,0
Exp/Cntr=0.3,0.1

Type RM Length L Ch R = 1 ,53887   ,264.9,264.8,264
XS GIS Cut Line= 4
2430571.04128378624625.3514284622430655.12163502624603.467501427
 2430743.8091288624547.0300053892430883.17519044624453.735369081
#Sta/Elev= 30
       0  2303.9    6.822302.532      41 2293.79    49.3 2292.16    73.9  2289.7
   102.9 2289.14     116 2286.23   127.6 2285.55   136.82283.225   142.1 2282.22
   147.6 2281.79   156.62283.239   162.3 2285.19     186 2296.44   195.5 2301.77
   206.6 2310.06  216.582315.522     234 2325.01   267.7 2341.48   277.4 2344.94
     287 2349.15   291.8  2350.3     298 2351.06   300.9 2352.19   306.2 2355.55
   314.5 2358.68   328.9 2362.96   335.1 2365.42   352.8  2371.1   359.7 2372.88
#Mann= 5 ,-1 , 0
       0     .06       0    6.82     .05       0   136.8    .045       0
   156.6     .05       0  216.58      .1       0
Bank Sta=136.8,156.6
XS Rating Curve= 0 ,0
Exp/Cntr(USF)=0,0
Exp/Cntr=0.3,0.1

Type RM Length L Ch R = 1 ,53622   ,267.6,268,268.3
XS GIS Cut Line= 4
2430724.22877303624870.681768383 2430816.3716237624806.181772911
2430911.96983128624737.0746349052431032.90732279624647.235355497
#Sta/Elev= 30
       0 2293.97    10.3 2293.07    13.6 2291.92    21.8 2287.14    27.5 2286.16
    79.2 2283.01  103.822283.978   116.5 2283.44   130.9 2281.31   136.6 2279.74
   144.92275.164   150.9 2273.95   156.6 2273.83   159.5    2274   162.22275.177
   168.1 2277.63   179.6 2278.44   184.5 2280.08   199.3 2289.38   204.2 2293.88
  214.872300.493   222.5 2305.15     234 2310.71   251.1 2321.83   267.6    2331
   279.7 2333.56     314 2348.43   338.5 2357.46   353.5 2362.15   381.1 2369.43
#Mann= 5 ,-1 , 0
       0     .06       0  103.82     .05       0   144.9    .045       0
   162.2     .05       0  214.87      .1       0
Bank Sta=144.9,162.2
XS Rating Curve= 0 ,0
Exp/Cntr(USF)=0,0
Exp/Cntr=0.3,0.1

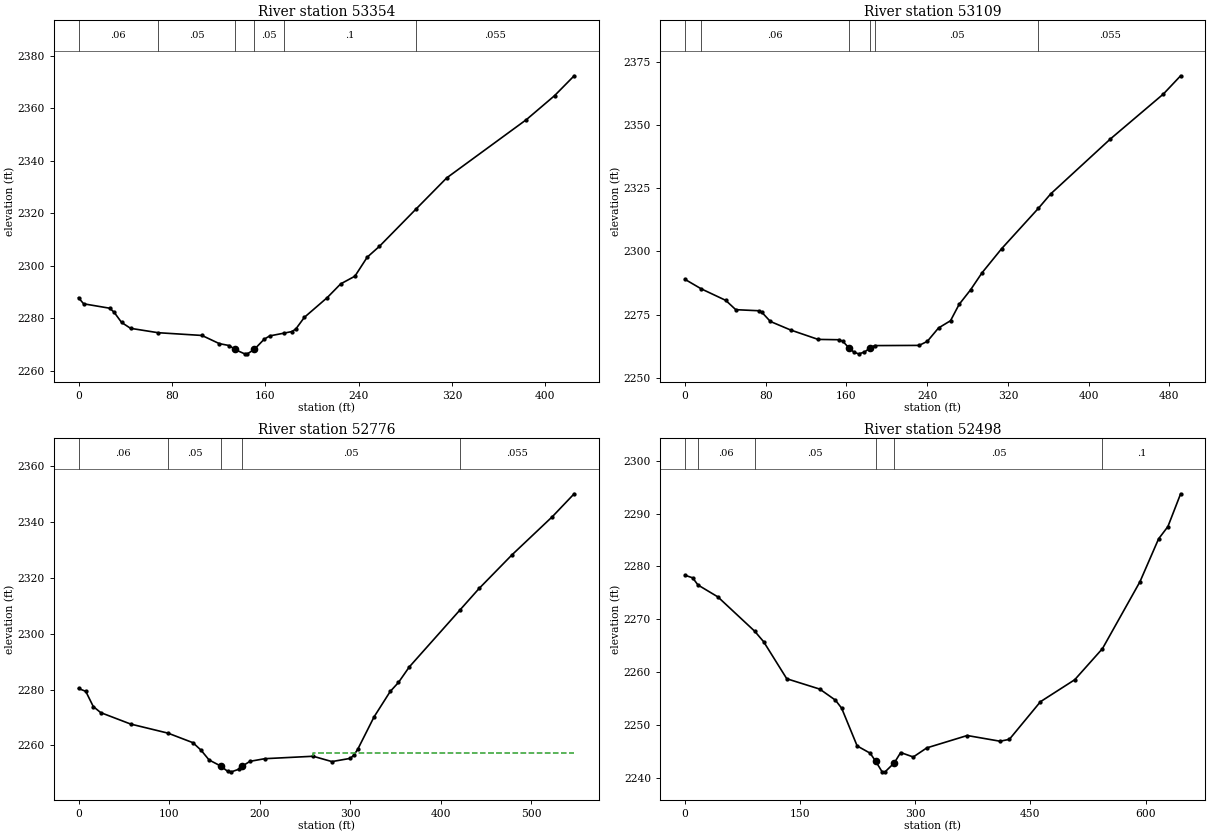
Type RM Length L Ch R = 1 ,53354   ,247.3,245.2,243.4
XS GIS Cut Line= 4
2430887.78233298625069.9406829662430966.10375605625022.717471996
2431075.52339123624951.306762723 2431229.8626661624820.003200512
#Sta/Elev= 30
       0 2287.78     4.4 2285.46    26.8 2283.77    30.6 2282.19    36.9 2278.36
    44.6 2276.11   68.152274.441   105.8 2273.39   120.7 2270.27   129.4 2269.52
     134 2268.04   142.4 2266.38   144.8 2266.41   150.62268.044   159.1 2271.95
   163.9 2273.22  176.45  2274.3     183 2274.89   186.3 2275.89   193.6 2280.31
   213.2 2287.84   224.7 2293.06   236.9 2295.99   247.4 2303.22   257.9 2307.38
  289.412321.665   315.6 2333.49   383.9 2355.71     408 2364.84   424.8 2372.42
#Mann= 6 ,-1 , 0
       0     .06       0   68.15     .05       0     134    .045       0
   150.6     .05       0  176.45      .1       0  289.41    .055       0
Bank Sta=134,150.6
XS Rating Curve= 0 ,0
Exp/Cntr(USF)=0,0
Exp/Cntr=0.3,0.1

Type RM Length L Ch R = 1 ,53109   ,337.7,332.4,325.4
XS GIS Cut Line= 4
2431025.99660899625292.2353102182431118.13945966625225.431743479
2431236.77337991625103.3424663362431354.25551452624932.878192588
#Sta/Elev= 30
       0 2288.97   16.042285.229    40.4 2280.65    50.3 2276.97    73.1 2276.55
      76 2276.01    84.6 2272.31   104.6 2268.94   131.9 2265.21   152.8 2265.08
   156.4 2264.44   162.62261.808   167.6 2260.09   172.1  2259.5   177.8 2260.18
   183.22261.816  187.782262.761     232 2262.84   240.1 2264.43   251.2 2269.73
   263.1  2272.6   271.6 2279.05   282.9 2284.79   294.3 2291.55   313.7 2301.08
  350.222317.096   362.3 2322.75   421.4 2344.47   474.1 2362.32   491.1  2369.5
#Mann= 6 ,-1 , 0
       0     .05       0   16.04     .06       0   162.6    .045       0
   183.2     .06       0  187.78     .05       0  350.22    .055       0
Bank Sta=162.6,183.2
XS Rating Curve= 0 ,0
Exp/Cntr(USF)=0,0
Exp/Cntr=0.3,0.1

Type RM Length L Ch R = 1 ,52776   ,279,278.6,276.9
XS GIS Cut Line= 4
2431388.80908352625530.6549363382431417.60372435625418.931729895
2431467.13050659625204.6996020772431434.88050886624995.074616793
#Sta/Elev= 30
       0  2280.4       8 2279.38    16.3 2273.94    24.5 2271.76    57.6 2267.66
   98.872264.402   126.4 2260.98   135.3  2258.3   144.2  2254.8   157.1 2252.62
   164.7 2250.72   168.8 2250.55     177 2251.48     1812252.627   189.3 2254.31
   205.7 2255.26   259.1 2256.13   279.8 2254.22   300.2 2255.38   304.3 2256.65
   308.4 2258.68   326.4 2270.26   344.2 2279.34   353.3 2282.56   365.2  2288.1
  421.322308.561   442.4 2316.24   478.7 2328.28   523.3 2341.96   547.3 2350.13
#Mann= 5 ,-1 , 0
       0     .06       0   98.87     .05       0   157.1    .045       0
     181     .05       0  421.32    .055       0
#XS Ineff= 2 , 0
                          258.74         2257.23
Permanent Ineff=
       F       F
Bank Sta=157.1,181
XS Rating Curve= 0 ,0
Exp/Cntr(USF)=0,0
Exp/Cntr=0.3,0.1

Type RM Length L Ch R = 1 ,52498   ,260.6,264.9,268.9
XS GIS Cut Line= 4
2431611.10371077625702.2709957192431676.75549188625535.262078872
2431706.70191834625338.3067355552431748.16620115  625074.5478255
#Sta/Elev= 30
       0 2278.33      10 2277.84   16.962276.482    42.8 2274.24   90.872267.734
   102.5 2265.75   132.6 2258.75   175.6 2256.79     196  2254.7   204.1 2253.18
   224.3 2246.04   241.2 2244.67   248.2 2243.19   256.7 2241.17   260.7 2241.14
   272.9 2242.87   272.9 2242.89     281 2244.79   297.4 2243.95     315 2245.67
   367.7 2248.01   410.5 2246.93   422.6 2247.29   463.1 2254.41   507.7 2258.56
  543.882264.451   592.7  2277.1     617 2285.22   629.1 2287.53   645.7 2293.74
#Mann= 6 ,-1 , 0
       0    .055       0   16.96     .06       0   90.87     .05       0
   248.2    .045       0   272.9     .05       0  543.88      .1       0
Bank Sta=248.2,272.9
XS Rating Curve= 0 ,0
Exp/Cntr(USF)=0,0
Exp/Cntr=0.3,0.1