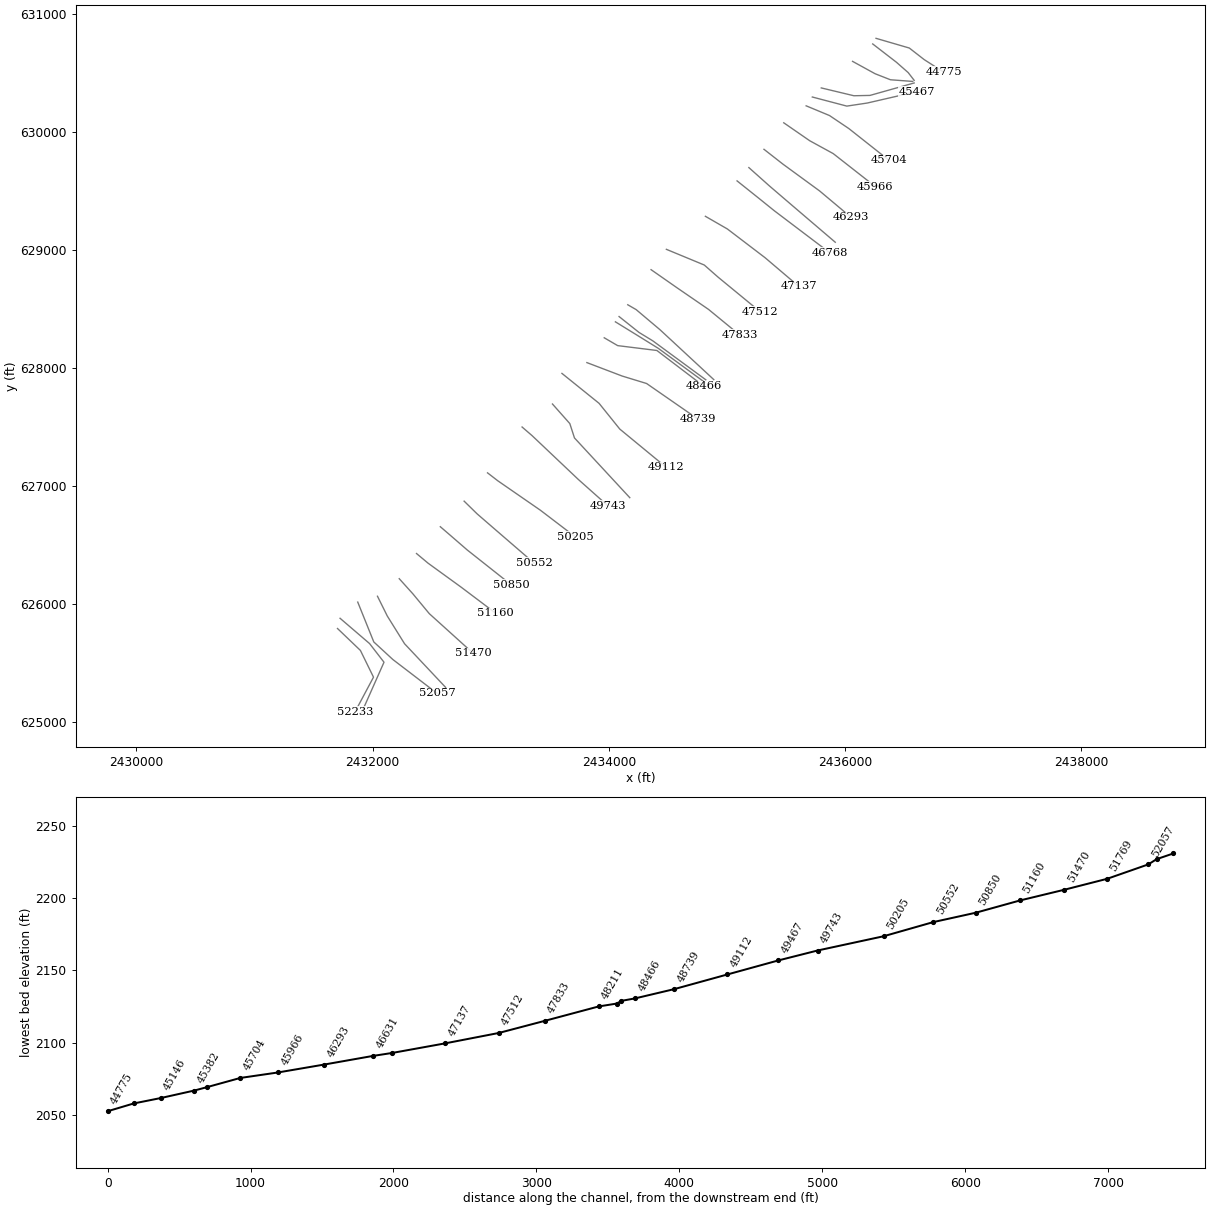
HEC-RAS study REEDSCK.prj: REEDSCK

--- REEDSCK.g01 (geometry) --- (continued)

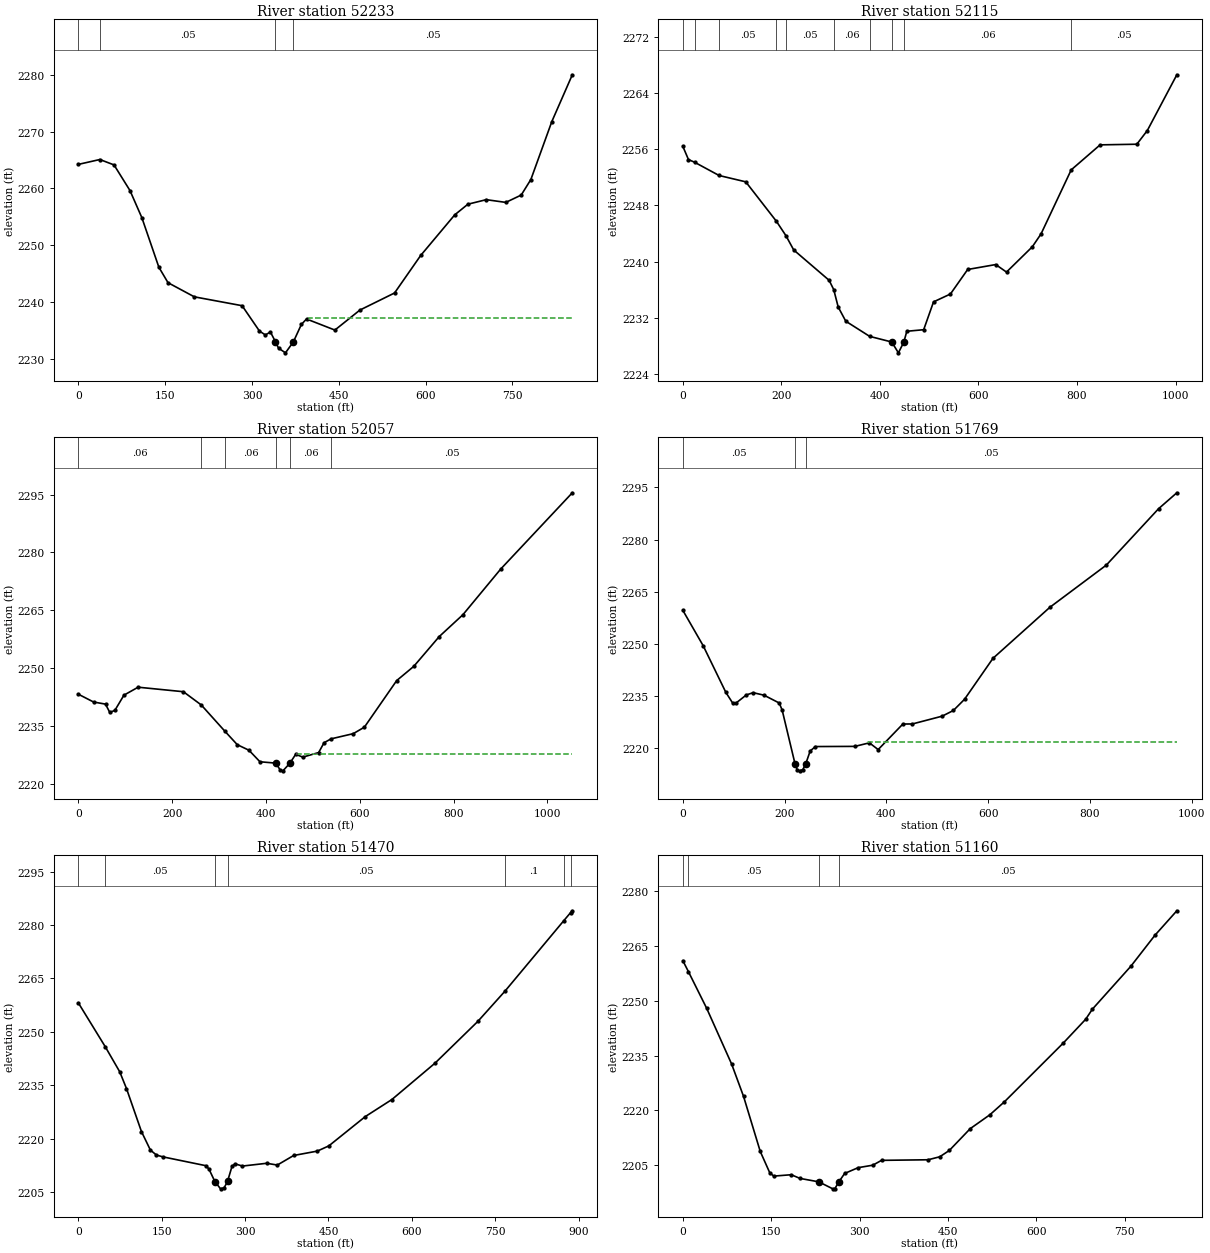
Type RM Length L Ch R = 1 ,52233   ,115.3,118.1,120.1
XS GIS Cut Line= 4
2431702.22125367625793.5776354532431896.23788515 625607.83455173
2432007.01037634625381.473374097 2431850.4840301  625087.6854627
#Sta/Elev= 30
       0 2264.21   37.25 2265.07    61.7 2264.12    89.3  2259.6   109.8 2254.83
   139.2  2246.1     155 2243.38   200.5 2240.89     283 2239.33     313 2234.86
   323.1 2234.19     332 2234.69   340.6 2232.98   345.9 2231.86   357.9 2231.03
   371.62232.964   385.4 2236.03   394.3 2236.99   443.3 2235.04   486.5 2238.56
   546.4 2241.57   591.5 2248.17   650.4 2255.33   673.1  2257.2   704.8    2258
   738.6 2257.52   765.2 2258.81   781.9 2261.55   818.1 2271.75   853.5 2279.99
#Mann= 4 ,-1 , 0
       0    .055       0   37.25     .05       0   340.6    .045       0
   371.6     .05       0
#XS Ineff= 2 , 0
                          397.86         2237.09
Permanent Ineff=
       F       F
Bank Sta=340.6,371.6
XS Rating Curve= 0 ,0
Exp/Cntr(USF)=0,0
Exp/Cntr=0.5,0.3

Type RM Length L Ch R = 1 ,52115   ,54.9,57.3,56.8
XS GIS Cut Line= 4
2431723.88515283625880.1052489052431973.82263528625665.873121087
2432095.91191242625508.0784893072431903.56371164625075.007091137
#Sta/Elev= 30
       0 2256.41    11.4 2254.53   23.972254.142   73.572252.261   127.7 2251.36
  189.922245.745  209.212243.703     225 2241.67   296.9 2237.35  306.272236.023
   315.3 2233.55   330.7 2231.53  379.162229.373     424 2228.57   437.5 2227.03
   448.4 2228.54   454.6  2230.1   488.8 2230.32   508.8 2234.28   543.1  2235.4
   578.1 2238.89     635 2239.59   656.9 2238.52   709.3 2242.12     727 2243.95
   788.2 2253.06   846.9 2256.62   921.4 2256.71   942.7 2258.66  1002.6 2266.59
#Mann= 10 ,-1 , 0
       0     .06       0   23.97    .055       0   73.57     .05       0
  189.92     .06       0  209.21     .05       0  306.27     .06       0
  379.16     .05       0     424    .045       0   448.4     .06       0
   788.2     .05       0
#XS Ineff= 2 , 0
             409    2227     463            2227
Permanent Ineff=
       F       F
Bank Sta=424,448.4
XS Rating Curve= 0 ,0
Exp/Cntr(USF)=0,0
Exp/Cntr=0.5,0.3

Type RM Length L Ch R = 1 ,52057   ,288.2,288.8,286.9
XS GIS Cut Line= 4
2431873.61728517626017.1677392832432009.52798992625679.694548688
 2432170.7779786625531.1142019762432543.95652383625245.471364885
#Sta/Elev= 30
       0 2243.29    32.6 2241.26      58 2240.72    67.1 2238.56      78 2239.11
    97.3 2243.04   127.5  2245.1     224 2243.93  262.122240.499  312.572233.683
   338.8 2230.22   363.8 2228.77   387.2 2225.79     4212225.436   430.7 2223.59
   436.2 2223.44   451.22225.443   463.4 2227.73   478.5 2226.99   512.3 2228.17
   523.8 2230.72  538.842231.726   586.1 2233.07   609.8 2234.75   678.7 2246.82
   715.1  2250.5   769.4 2258.22   819.8 2263.87   900.4  2275.7    1053 2295.45
#Mann= 6 ,-1 , 0
       0     .06       0  262.12    .055       0  312.57     .06       0
     421    .045       0   451.2     .06       0  538.84     .05       0
#XS Ineff= 2 , 0
                          463.65         2227.76
Permanent Ineff=
       F       F
Bank Sta=421,451.2
XS Rating Curve= 0 ,0
Exp/Cntr(USF)=0,0
Exp/Cntr=0.5,0.3

Type RM Length L Ch R = 1 ,51769   ,297.1,299,299.9
XS GIS Cut Line= 4
2432040.62620202626066.6945215212432123.55476763625899.685604673
2432269.83154307625664.7213354532432617.67080437625294.998147122
#Sta/Elev= 30
       0 2259.64      40 2249.45    84.6 2236.01      98 2232.94   103.7 2232.85
   124.8 2235.29   138.2 2235.94   159.6 2235.21   189.4 2232.97   195.2 2230.94
   220.52215.448   225.1 2213.63   229.8 2213.44   235.8 2213.78   241.5 2215.44
   250.3 2219.16   260.6 2220.43   338.2 2220.48   366.6  2221.5   383.9 2219.56
   432.4 2226.91   451.3 2226.94   509.7 2229.18   531.7 2230.81   553.6 2234.03
   609.5 2245.82   721.4 2260.52   832.3 2272.66   934.9 2288.88   970.9 2293.48
#Mann= 3 ,-1 , 0
       0     .05       0   220.5    .045       0   241.5     .05       0
#XS Ineff= 2 , 0
                          364.49          2221.8
Permanent Ineff=
       F       F
Bank Sta=220.5,241.5
XS Rating Curve= 0 ,0
Exp/Cntr(USF)=0,0
Exp/Cntr=0.3,0.1

Type RM Length L Ch R = 1 ,51470   ,306.7,309.9,311.9
XS GIS Cut Line= 4
2432224.91190337626215.2748682332432340.09046671626087.426662922
2432479.45652836625919.2659604422432849.17971669625585.248126747
#Sta/Elev= 30
       0 2258.15   48.47 2245.82    74.5 2238.78    86.7 2234.06   113.6 2221.98
   129.7 2216.78   140.5 2215.39   151.7 2214.89   229.9 2212.38   235.1 2211.43
   245.72207.935   255.9 2205.89   262.4 2206.19   268.42207.955   276.5 2212.21
   281.9 2212.92   295.3 2212.29     339 2213.07     358 2212.57   387.4 2215.26
   429.9 2216.49   450.7 2217.96   516.3 2226.19   564.1 2230.98   641.7  2241.2
   718.8 2252.94  767.272261.374  873.332281.221  885.542283.478   888.7 2284.01
#Mann= 7 ,-1 , 0
       0    .055       0   48.47     .05       0   245.7    .045       0
   268.4     .05       0  767.27      .1       0  873.33     .05       0
  885.54      .1       0
Bank Sta=245.7,268.4
XS Rating Curve= 0 ,0
Exp/Cntr(USF)=0,0
Exp/Cntr=0.3,0.1

Type RM Length L Ch R = 1 ,51160   ,309.6,309.8,309.2
XS GIS Cut Line= 4
2432371.18867882626428.3552104182432469.09045766626346.578430445
2432750.12615221626142.7123733272433040.37613184625923.873102976
#Sta/Elev= 30
       0 2261.04    9.512258.012    40.5 2247.96    82.8 2232.69     103 2223.84
   131.4 2208.72   147.5 2202.89   154.3 2201.97     184 2202.35   198.8 2201.34
   230.7  2200.4   254.5 2198.48   258.1 2198.56   264.72200.386   274.6  2202.7
   297.6 2204.29   322.3 2204.96   337.2 2206.29   416.2 2206.45     436 2207.27
   452.2    2209   487.7 2214.98     521 2218.78   545.7 2222.34   645.9  2238.5
   683.6 2244.97     695 2247.74   760.2 2259.49   801.1 2267.99   838.3 2274.71
#Mann= 4 ,-1 , 0
       0    .055       0    9.51     .05       0   230.7    .045       0
   264.7     .05       0
Bank Sta=230.7,264.7
XS Rating Curve= 0 ,0
Exp/Cntr(USF)=0,0
Exp/Cntr=0.3,0.1

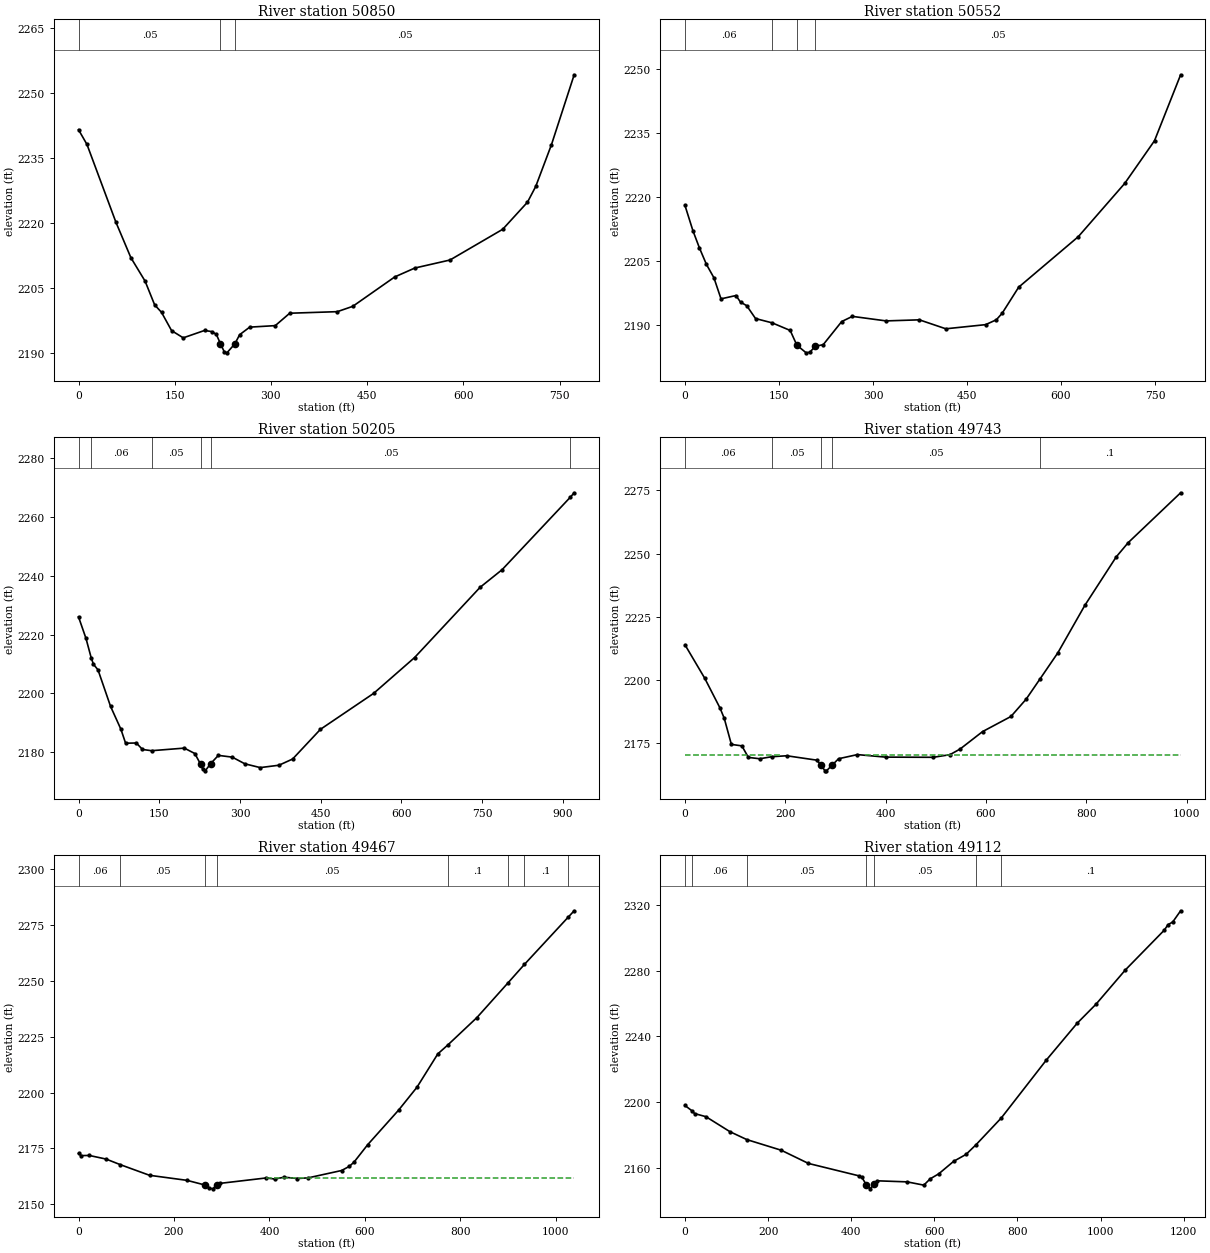
Type RM Length L Ch R = 1 ,50850   ,298.6,297.6,296.7
XS GIS Cut Line= 4
2432572.75116467626655.2569802042432654.52794464626584.998056565
2432800.80472008626458.3016368872433170.52790842626165.748085996
#Sta/Elev= 30
       0 2241.47    13.2 2238.06    58.4 2220.09    81.7 2211.92   103.8 2206.53
   118.7 2201.05   129.4 2199.33   145.1 2195.11   163.3 2193.44   196.6 2195.15
   207.7 2194.88   214.9 2194.24   221.3 2192.08   227.1 2190.27   231.4 2189.98
   243.82192.062   251.2 2194.16   266.9 2195.91   306.8 2196.26   329.3 2199.12
   403.5 2199.48   427.6 2200.71   493.1  2207.5   524.4 2209.55   579.2  2211.4
   661.4 2218.49     700 2224.74   712.9 2228.38   737.4 2238.01   772.8 2254.14
#Mann= 3 ,-1 , 0
       0     .05       0   221.3    .045       0   243.8     .05       0
Bank Sta=221.3,243.8
XS Rating Curve= 0 ,0
Exp/Cntr(USF)=0,0
Exp/Cntr=0.3,0.1

Type RM Length L Ch R = 1 ,50552   ,347,347.8,348
XS GIS Cut Line= 4
2432774.31365052626871.7926792892432883.73328569 626764.67661538
2433046.13506001626624.158768101 2433366.3314661626347.730216078
#Sta/Elev= 30
       0 2218.04    12.7 2212.11      23 2208.11    34.2 2204.23    46.2 2201.08
    57.5 2196.14    81.3 2196.92    88.6 2195.38    98.5 2194.54   112.6 2191.52
   139.22190.508   167.9 2188.73   178.52185.284   193.4 2183.48   199.4 2183.63
   207.6    2185   220.6  2185.4   250.1 2190.82   267.1 2192.03   320.9 2190.97
     374 2191.22   416.2 2189.12   479.7 2190.09   496.8 2191.23   506.1 2192.76
   532.5 2198.88   627.6 2210.72   701.6  2223.2   749.2 2233.22   790.9 2248.69
#Mann= 4 ,-1 , 0
       0     .06       0   139.2     .05       0   178.5    .045       0
   207.6     .05       0
Bank Sta=178.5,207.6
XS Rating Curve= 0 ,0
Exp/Cntr(USF)=0,0
Exp/Cntr=0.3,0.1

Type RM Length L Ch R = 1 ,50205   ,463.2,462,460.4
XS GIS Cut Line= 4
2432972.42077947627111.3640910422433058.80470197627044.560524303
2433420.46539087626794.6230418492433716.47429866626568.873057697
#Sta/Elev= 30
       0 2226.05    13.9 2218.71   23.442212.221    27.7 2209.94    36.2 2208.03
    59.6 2195.58    78.8 2187.82    87.5 2183.08   107.5 2183.15   118.9 2180.95
  135.722180.528   196.6 2181.41   216.1 2179.57   226.92175.934   231.1 2174.17
   235.5 2173.68   245.5 2176.12   259.9 2178.94   285.7 2178.34   309.1 2176.07
   337.7 2174.78   372.5 2175.59   397.9  2177.7   449.6  2187.8   548.4 2200.02
   624.5  2212.2   746.3  2236.1   787.1 2242.08  914.112266.773   921.1 2268.25
#Mann= 6 ,-1 , 0
       0      .1       0   23.44     .06       0  135.72     .05       0
   226.9    .045       0   245.5     .05       0  914.11      .1       0
#XS Ineff= 2 , 0
                          287.09         2176.65
Permanent Ineff=
       F       F
Bank Sta=226.9,245.5
XS Rating Curve= 0 ,0
Exp/Cntr(USF)=0,0
Exp/Cntr=0.3,0.1

Type RM Length L Ch R = 1 ,49743   ,279.7,275.3,252.1
XS GIS Cut Line= 4
2433264.97433036627499.515849508 2433349.0546816627426.953354602
 2433741.8135826627054.9265950042433992.90285069626831.480182119
#Sta/Elev= 30
       0 2213.79    39.3 2200.56    69.8 2188.74    78.3 2184.64    92.5  2174.3
   113.4 2173.71   126.4 2169.14   149.1  2168.6  172.732169.403   202.8 2169.79
   262.3 2168.06   271.82166.046   278.7  2163.9   282.1 2163.81   293.22166.034
   306.2 2168.61   343.8 2170.25   399.9 2169.25     495 2169.18   528.2 2170.21
   548.6 2172.47   593.3 2179.37   649.9 2185.37   680.1 2192.21   707.32200.098
   743.4 2210.62   797.2 2229.43   859.6 2248.61   883.5 2254.28   988.2 2274.09
#Mann= 5 ,-1 , 0
       0     .06       0  172.73     .05       0   271.8    .045       0
   293.2     .05       0   707.3      .1       0
#XS Ineff= 2 , 0
          192.43  2169.9  359.78            2170
Permanent Ineff=
       F       F
Bank Sta=271.8,293.2
XS Rating Curve= 0 ,0
Exp/Cntr(USF)=0,0
Exp/Cntr=0.3,0.1

Type RM Length L Ch R = 1 ,49467   ,351.2,354.9,348.5
XS GIS Cut Line= 4
2433522.20281139627694.1993232972433669.07781139627528.574323311
2433708.66114473627406.6993233112434176.71670029626901.317378864
#Sta/Elev= 30
       0 2172.75     5.6 2171.81    22.6 2171.86    57.9 2170.24   87.482167.747
   148.8 2162.98   227.3 2160.72   265.6 2158.59   273.6 2157.29   281.2 2156.92
   289.9 2158.75     297 2159.38   392.9 2161.79   411.4 2161.31     431 2162.14
   458.4 2161.54   481.1 2161.84     551 2165.12   567.3 2166.98   577.3 2168.92
   605.7 2176.66   670.5 2192.15   709.1 2202.43   752.7 2217.34  773.642221.321
   834.5 2233.57  899.652249.107  934.082257.379 1025.662278.504  1038.3 2281.39
#Mann= 8 ,-1 , 0
       0     .06       0   87.48     .05       0   265.6    .045       0
   289.9     .05       0  773.64      .1       0  899.65     .05       0
  934.08      .1       0 1025.66     .05       0
#XS Ineff= 2 , 0
                          392.58         2161.97
Permanent Ineff=
       F       F
Bank Sta=265.6,289.9
XS Rating Curve= 0 ,0
Exp/Cntr(USF)=0,0
Exp/Cntr=0.3,0.1

Type RM Length L Ch R = 1 ,49112   ,366.8,373.2,384
XS GIS Cut Line= 4
2433602.44752095 627953.319389082433916.88499888627699.926549725
2434091.95641516627482.239065007 2434485.0960848627158.411927246
#Sta/Elev= 30
       0 2197.93   17.712194.534      23 2193.02    50.3 2191.14   108.3 2181.99
  148.84 2177.19   231.6 2170.72   297.1 2162.69   419.6 2155.09   425.7 2154.21
   436.22149.748   445.7 2147.25   454.5 2150.13   461.6 2152.14   534.5 2151.49
   574.6  2149.5     590 2153.34   610.5 2156.37   646.4 2163.98   676.2 2168.19
  700.142174.051  761.152190.392   869.4 2225.57   943.6 2247.96   988.8 2259.49
  1059.6 2280.38  1153.2 2304.56  1162.1 2307.87  1173.5 2309.52  1192.5 2316.33
#Mann= 7 ,-1 , 0
       0     .05       0   17.71     .06       0  148.84     .05       0
   436.2    .045       0   454.5     .05       0  700.14      .1       0
  761.15      .1       0
#XS Ineff= 2 , 0
                          477.36         2151.58
Permanent Ineff=
       F       F
Bank Sta=436.2,454.5
XS Rating Curve= 0 ,0
Exp/Cntr(USF)=0,0
Exp/Cntr=0.3,0.1

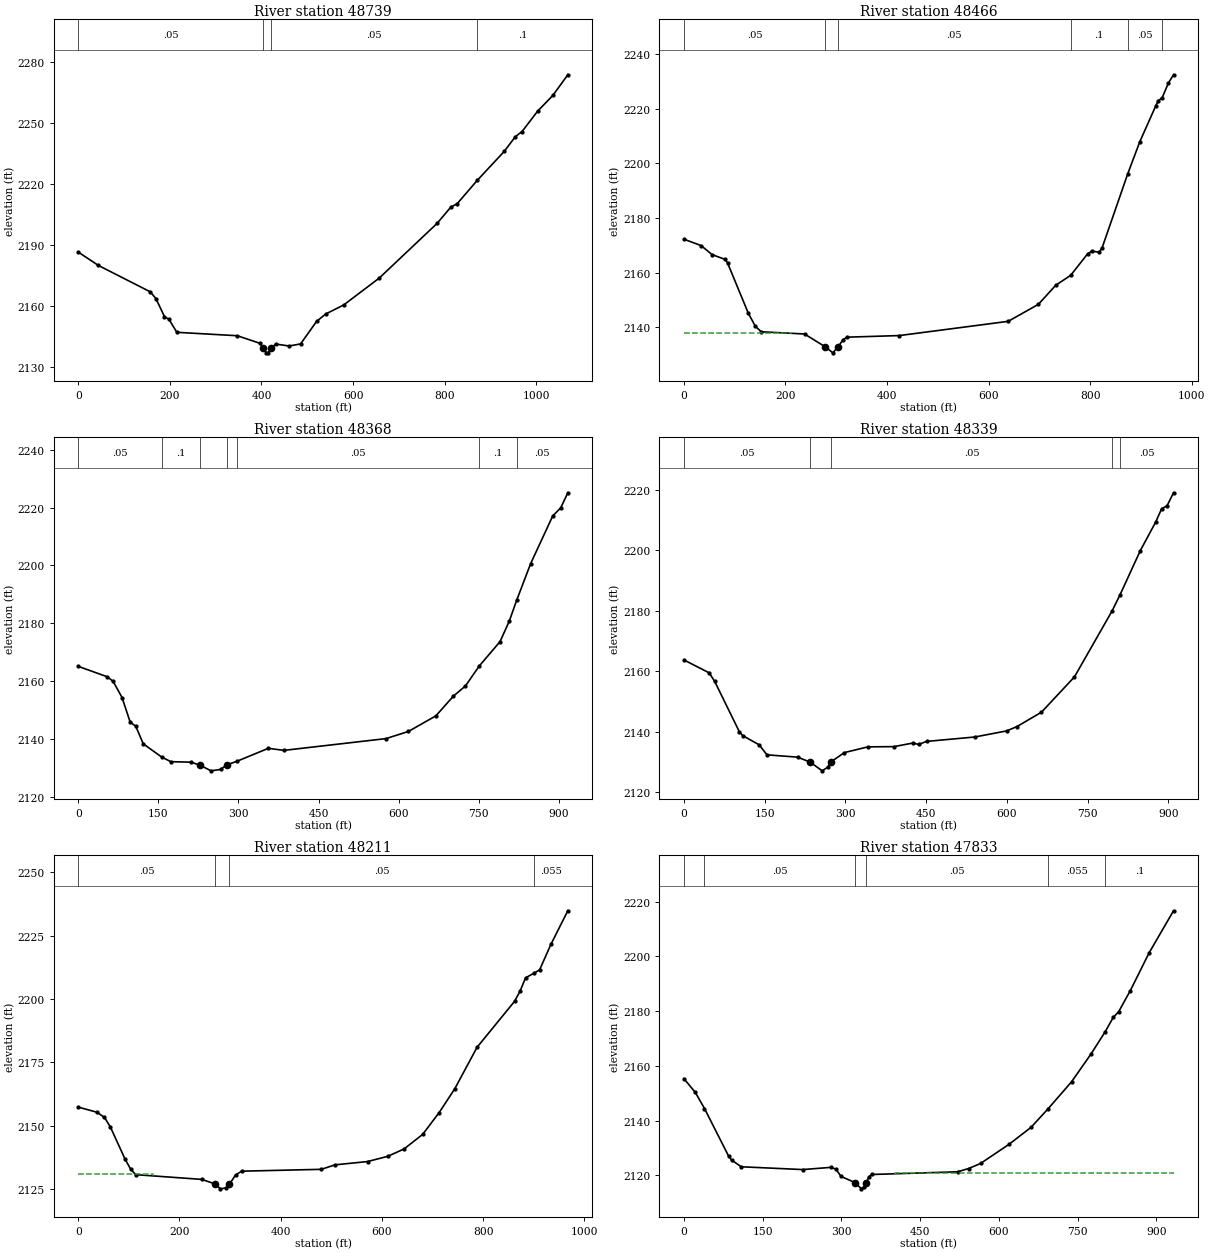
Type RM Length L Ch R = 1 ,48739   ,271,272.8,276.4
XS GIS Cut Line= 4
2433813.61612018628044.7654805442434112.22721033627931.008874773
2434319.20103472627867.8107604562434756.84797636627564.459811734
#Sta/Elev= 30
       0 2186.55      44 2179.98   157.3 2167.02   169.7 2163.67   188.3  2154.8
   198.1 2153.53   215.2 2147.15   347.3 2145.47   397.5 2141.68   403.52139.391
     410 2137.17   414.2 2137.07   421.4 2139.35   430.9 2141.39   460.2 2140.43
   485.3 2141.44   520.3 2152.54   540.3 2156.16   579.4 2160.57     657 2173.78
   783.5 2200.68   812.8 2208.51   827.4 2210.37  870.592221.678   929.6 2235.92
     954  2243.2   968.6  2245.7  1002.6  2255.7  1036.1 2263.51  1068.5 2273.57
#Mann= 4 ,-1 , 0
       0     .05       0   403.5    .045       0   421.4     .05       0
  870.59      .1       0
Bank Sta=403.5,421.4
XS Rating Curve= 0 ,0
Exp/Cntr(USF)=0,0
Exp/Cntr=0.3,0.1

Type RM Length L Ch R = 1 ,48466   ,103.1,98,92.2
XS GIS Cut Line= 4
2433960.55173597628254.8992106482434074.30834174628188.541190616
 2434406.0984419628147.4624163092434802.66660924627845.691420445
#Sta/Elev= 30
       0 2172.28    33.8 2169.95    55.6 2166.63    81.3 2164.87    85.9  2163.6
     127  2145.1   140.7 2140.41   152.3 2138.39   237.6 2137.58   278.42132.866
   293.4 2130.68   303.52132.886   313.5 2135.48   321.6 2136.42   424.1    2137
   638.7 2142.21   698.2 2148.44   732.3 2155.42  761.762159.055   795.1 2166.93
   803.6 2167.89     818 2167.53   823.7 2169.15   874.32196.305   897.9 2207.96
   929.3 2221.08   934.3 2223.01  941.73 2223.98   954.4 2229.52   964.3 2232.47
#Mann= 6 ,-1 , 0
       0     .05       0   278.4    .045       0   303.5     .05       0
  761.76      .1       0   874.3     .05       0  941.73      .1       0
#XS Ineff= 2 , 0
          212.92 2138.05
Permanent Ineff=
       F       F
Bank Sta=278.4,303.5
XS Rating Curve= 0 ,0
Exp/Cntr(USF)=0,0
Exp/Cntr=0.5,0.3

Type RM Length L Ch R = 1 ,48368   ,29.2,29.4,29.6
XS GIS Cut Line= 4
2434055.06855217628389.9348557592434225.90188551628284.726522416
2434417.56855217628165.9765224312434813.48869106627876.393189102
#Sta/Elev= 30
       0 2165.08    54.3 2161.48    65.4 2159.89    82.1 2154.28    97.3 2145.76
   107.7 2144.38   121.8 2138.27   156.1 2133.72   173.4  2132.1   211.3 2131.93
   228.7 2130.82   248.7 2128.93   266.5 2129.42   278.1    2131   296.5 2132.19
     356 2136.72   385.1 2136.01   576.2 2140.08   618.1 2142.55   669.6 2147.95
   702.4 2154.78   724.9 2158.28  750.552165.138   789.8 2173.66     807 2180.73
  820.99 2188.02     847 2200.61   888.4 2217.13   903.3 2219.91   916.6 2225.13
#Mann= 7 ,-1 , 0
       0     .05       0   156.1      .1       0   228.7    .045       0
   278.1      .1       0   296.5     .05       0  750.55      .1       0
  820.99     .05       0
#XS Ineff= 2 , 0
           224.9 2129.28  280.38         2129.37
Permanent Ineff=
       F       F
Bank Sta=228.7,278.1
XS Rating Curve= 0 ,0
Exp/Cntr(USF)=0,0
Exp/Cntr=0.5,0.3

Type RM Length L Ch R = 1 ,48339   ,129.7,127.9,125.7
XS GIS Cut Line= 4
2434086.05813551628434.7265224312434254.80813551628300.351522431
2434372.51646885628228.4765224312434820.43313554627899.309855744
#Sta/Elev= 30
       0 2163.77    46.9 2159.51    57.1  2156.7   102.8  2140.1   108.9 2138.79
   139.9  2135.7   154.3  2132.4     211 2131.64   234.4 2130.01   256.9 2127.11
   267.2 2128.32   272.8 2130.04   298.2 2133.15   341.9 2135.04   390.1 2135.11
   425.9 2136.32   435.8 2135.82   450.7 2136.84   540.1 2138.29   599.5 2140.31
   618.8 2141.76   664.2  2146.5   725.5 2158.18  795.522180.021  810.172185.316
   847.8 2199.91   876.4 2209.38   887.5 2213.78   897.5 2214.74   909.5 2219.04
#Mann= 5 ,-1 , 0
       0     .05       0   234.4    .045       0   272.8     .05       0
  795.52      .1       0  810.17     .05       0
Bank Sta=234.4,272.8
XS Rating Curve= 0 ,0
Exp/Cntr(USF)=0,0
Exp/Cntr=0.5,0.3

Type RM Length L Ch R = 1 ,48211   ,376.5,377.9,378.1
XS GIS Cut Line= 4
2434159.62579606628534.5508665022434230.72367467628493.472092196
2434432.95764049628322.8371835392434887.98406357627900.989770472
#Sta/Elev= 30
       0 2157.35    37.2 2155.31    51.8 2153.29    63.5 2149.52    92.5 2136.83
   103.8  2132.8   113.5 2130.69   244.4 2128.81   271.12126.969     281 2125.09
   291.2 2125.42   298.8 2126.97     311 2130.58   322.9 2132.06   480.1 2132.79
   507.3 2134.56   571.5 2135.86   611.2  2137.9   643.7 2140.83   680.4 2146.57
   713.1  2155.2   744.2 2164.69   787.9 2180.96   861.9 2199.07   872.8 2203.07
   883.7 2208.37  900.542210.217   911.5 2211.52   933.8 2221.58   967.2 2234.83
#Mann= 4 ,-1 , 0
       0     .05       0   271.1    .045       0   298.8     .05       0
  900.54    .055       0
#XS Ineff= 2 , 0
          148.02 2130.77
Permanent Ineff=
       F       F
Bank Sta=271.1,298.8
XS Rating Curve= 0 ,0
Exp/Cntr(USF)=0,0
Exp/Cntr=0.3,0.1

Type RM Length L Ch R = 1 ,47833   ,321.2,321.7,321.5
XS GIS Cut Line= 4
2434357.11990331628831.5820037932434576.73335056628678.326576573
2434843.74538355628495.0520450542435107.59751082628278.598503517
#Sta/Elev= 30
       0 2155.36    21.8 2150.31   39.212144.446      85 2127.12    90.7 2125.63
   109.3 2123.16   226.4 2122.14   280.3 2122.95   289.6 2122.28   299.4 2119.64
   325.9 2117.38   338.2  2115.1     343 2115.73   347.52117.389   352.7 2119.51
   357.6 2120.34   521.3 2121.32   542.5 2122.52   565.2 2124.37   619.5 2131.37
   661.3 2137.55  694.022144.373   738.9 2154.28   775.8  2164.4  802.782172.522
     818 2177.73   828.4 2179.82   850.5  2187.5   886.6  2201.4   932.9 2216.69
#Mann= 6 ,-1 , 0
       0     .06       0   39.21     .05       0   325.9    .045       0
   347.5     .05       0  694.02    .055       0  802.78      .1       0
#XS Ineff= 2 , 0
                           402.9         2120.84
Permanent Ineff=
       F       F
Bank Sta=325.9,347.5
XS Rating Curve= 0 ,0
Exp/Cntr(USF)=0,0
Exp/Cntr=0.3,0.1

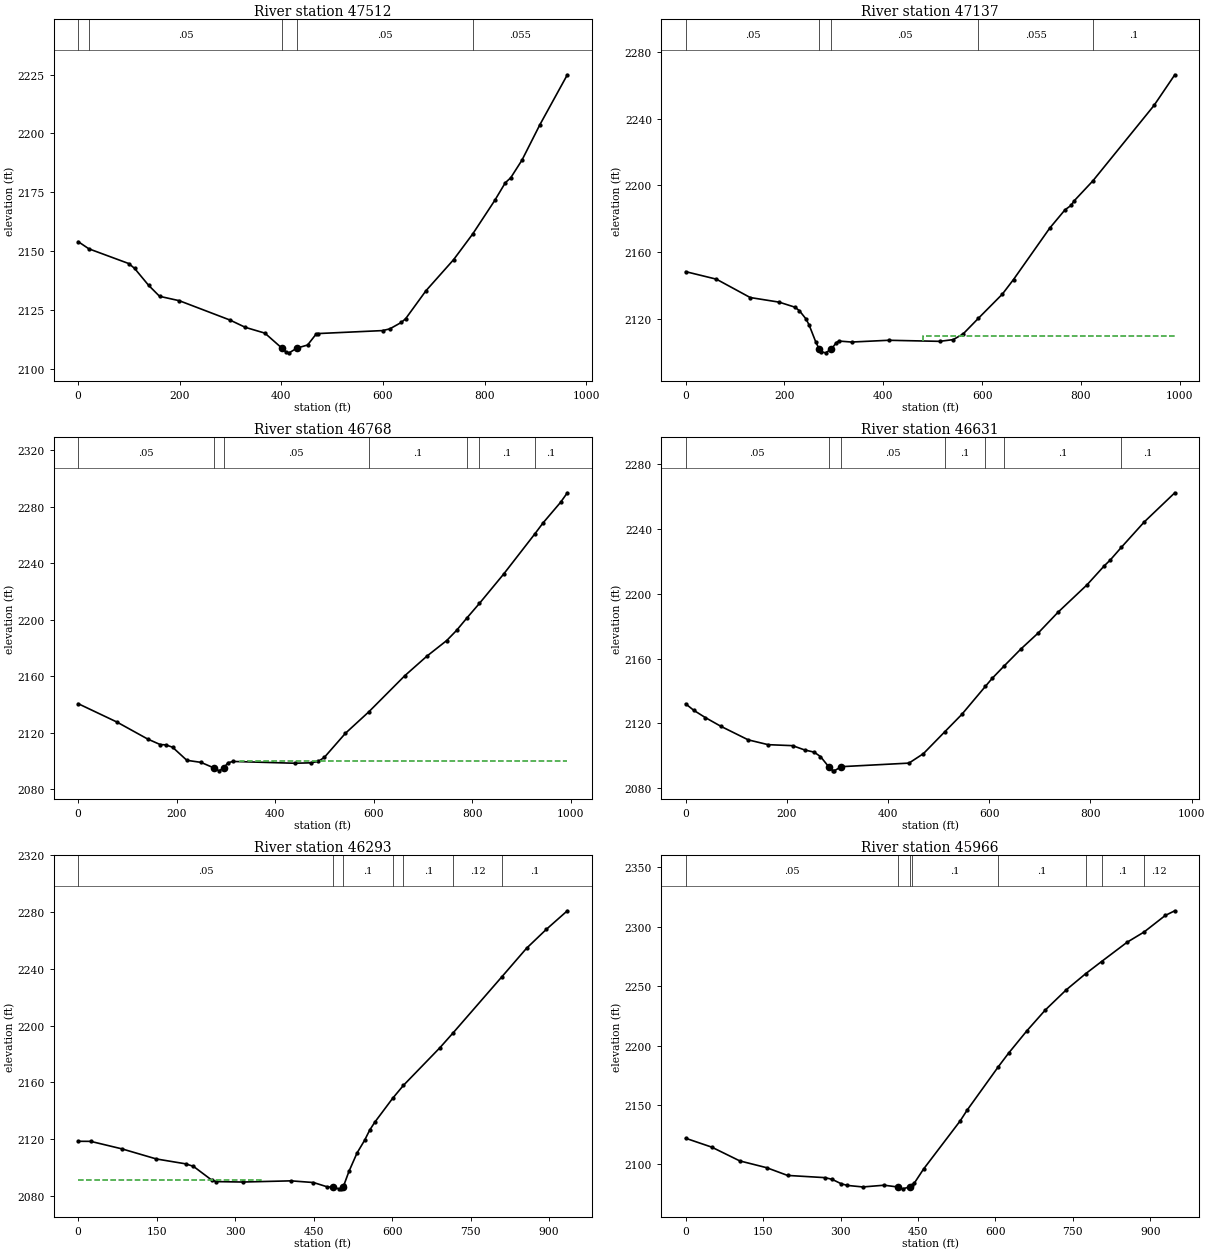
Type RM Length L Ch R = 1 ,47512   ,372.8,374.7,375.6
XS GIS Cut Line= 4
2434486.67603766629003.7968653072434807.40646782628871.080825241
 2434924.3229793628768.3838894752435279.81237234628476.092610759
#Sta/Elev= 30
       0 2153.99   21.112150.928    99.6 2144.67     111 2142.62   138.5 2135.45
   160.2 2130.75   199.2 2128.87   298.8 2120.66   329.1 2117.55   367.5  2115.1
   401.1  2108.7   409.1 2107.07   415.4 2106.72   430.32108.712   451.6 2110.05
   468.6 2114.75   471.5 2114.91   599.3 2116.18   613.5 2116.92   636.2 2119.66
   644.8 2121.29   684.5 2133.09   738.9  2146.3  776.592157.236     820  2171.5
   840.8 2179.02   851.5 2181.15   873.5  2188.6     909 2203.75   962.9 2224.92
#Mann= 5 ,-1 , 0
       0     .06       0   21.11     .05       0   401.1    .045       0
   430.3     .05       0  776.59    .055       0
Bank Sta=401.1,430.3
XS Rating Curve= 0 ,0
Exp/Cntr(USF)=0,0
Exp/Cntr=0.3,0.1

Type RM Length L Ch R = 1 ,47137   ,369,369.1,375.8
XS GIS Cut Line= 4
2434816.88618496 629283.44852116 2435003.3206222629176.011726821
 2435322.4710995  628932.69898672435606.86261393628690.966199437
#Sta/Elev= 30
       0 2148.28    62.2 2143.76   130.6 2132.74   189.2 2129.97   221.3 2126.93
   230.2 2124.81   243.4 2119.93   249.7 2116.34   263.2 2106.14   270.32101.728
   274.8 2100.21     283 2099.54   294.72101.736     305 2105.73     310 2106.62
   335.8 2106.02   410.6 2107.08   513.9 2106.44   541.4 2107.47   561.5 2110.91
  592.322120.276   640.7 2134.75   663.4 2143.56   736.6 2174.39   767.5 2185.37
   779.6    2188     786 2190.75  823.692202.682   947.6 2248.02   989.7 2266.45
#Mann= 5 ,-1 , 0
       0     .05       0   270.3    .045       0   294.7     .05       0
  592.32    .055       0  823.69      .1       0
#XS Ineff= 2 , 0
                          479.94         2109.43
Permanent Ineff=
       F       F
Bank Sta=270.3,294.7
XS Rating Curve= 0 ,0
Exp/Cntr(USF)=0,0
Exp/Cntr=0.3,0.1

Type RM Length L Ch R = 1 ,46768   ,138.2,137,146.6
XS GIS Cut Line= 4
2435085.05003363629583.2618233112435264.21670029629440.206267744
2435400.32781142 629330.484045522435869.77225584628974.928489983
#Sta/Elev= 30
       0 2140.51    78.3 2127.56   140.9  2115.5   166.5 2111.55   177.9 2111.34
   191.6 2109.66   220.6 2100.38   249.1 2098.95     276 2094.93   286.1 2092.93
     295 2094.97   304.4 2098.68   314.2 2099.59   439.8 2098.31   472.4 2098.61
   487.4 2099.62   499.8  2102.5   542.6 2119.57  589.862134.694     663 2160.32
   708.2 2174.28   748.2 2185.28   768.2 2192.47  789.372201.351  814.68 2211.62
   863.8 2232.38  927.092260.851     944 2268.73   979.2 2283.16     993 2289.95
#Mann= 7 ,-1 , 0
       0     .05       0     276    .045       0     295     .05       0
  589.86      .1       0  789.37    .055       0  814.68      .1       0
  927.09      .1       0
#XS Ineff= 2 , 0
                          329.49         2099.75
Permanent Ineff=
       F       F
Bank Sta=276,295
XS Rating Curve= 0 ,0
Exp/Cntr(USF)=0,0
Exp/Cntr=0.3,0.1

Type RM Length L Ch R = 1 ,46631   ,312.1,338,284.4
XS GIS Cut Line= 4
2435185.01520086 629695.816217082435360.38996809629539.400884145
2435548.40435818629378.2456926362435916.53337408629063.835073908
#Sta/Elev= 30
       0 2132.11      16 2128.13    38.7 2123.68    69.9 2118.22   123.7 2109.91
   163.1 2106.95   211.4 2106.34     235 2103.71   253.9 2102.35   266.5 2099.61
   282.62093.401   290.9 2090.92   293.8 2090.83   307.32093.392   441.3 2095.59
   469.9 2101.42  512.582115.044   545.6 2125.54  592.282142.837   605.8  2147.8
   628.82155.231   662.6 2165.91   697.2 2175.88   736.3 2188.66   793.1 2205.38
   827.6 2217.22   838.9 2220.62  861.252228.588   906.5 2244.21   966.7 2262.13
#Mann= 7 ,-1 , 0
       0     .05       0   282.6    .045       0   307.3     .05       0
  512.58      .1       0  592.28     .05       0   628.8      .1       0
  861.25      .1       0
Bank Sta=282.6,307.3
XS Rating Curve= 0 ,0
Exp/Cntr(USF)=0,0
Exp/Cntr=0.3,0.1

Type RM Length L Ch R = 1 ,46293   ,319.1,326.6,326.6
XS GIS Cut Line= 4
2435312.99138235629850.651597157  2435472.566621 629725.83532138
2435783.81733402629498.3221098392436049.24941415629275.548756871
#Sta/Elev= 30
       0 2118.42    23.9 2118.36    83.5 2113.08   149.5 2105.95   205.3 2102.53
   220.2 2100.76   254.8 2091.17   263.5 2090.01   314.3 2089.71   406.6 2090.54
   449.6 2089.36   475.3 2086.39   486.8 2085.99     499 2084.91   502.6 2084.98
   505.8 2086.25   507.5  2087.3   517.4  2097.2   532.9 2110.21   547.2 2119.05
   557.1 2126.34   566.8 2131.88  601.022148.752  621.542157.831   691.2 2184.35
  716.642194.898  809.95 2234.48   856.7 2254.41   894.8 2267.84   934.7 2280.84
#Mann= 7 ,-1 , 0
       0     .05       0   486.8    .045       0   505.8      .1       0
  601.02     .12       0  621.54      .1       0  716.64     .12       0
  809.95      .1       0
#XS Ineff= 2 , 0
          351.79 2090.81
Permanent Ineff=
       F       F
Bank Sta=486.8,505.8
XS Rating Curve= 0 ,0
Exp/Cntr(USF)=0,0
Exp/Cntr=0.3,0.1

Type RM Length L Ch R = 1 ,45966   ,262.6,262.5,259.3
XS GIS Cut Line= 4
2435480.46638529630075.0049029832435700.07983255629923.329428621
2435899.15389264629814.3126814242436256.22323854629534.661025571
#Sta/Elev= 30
       0 2121.97    50.6 2114.48   104.9 2102.89     157 2097.17   197.3 2090.68
   269.9  2088.8   283.6  2087.4   301.1 2083.69   313.4 2082.25   343.1 2080.97
   384.4 2082.43   410.6 2080.95   420.4 2079.38   434.1 2081.08  438.492082.368
   443.2  2084.4   460.7 2095.98   531.9 2136.69   544.8  2145.4  605.752182.281
   625.4 2193.56     661 2212.49   696.6 2229.96   737.2 2246.95  774.462260.407
  805.452270.731     855 2286.99  887.862295.608   929.1  2309.6   947.4 2313.49
#Mann= 8 ,-1 , 0
       0     .05       0   410.6    .045       0   434.1     .05       0
  438.49      .1       0  605.75      .1       0  774.46     .12       0
  805.45      .1       0  887.86     .12       0
Bank Sta=410.6,434.1
XS Rating Curve= 0 ,0
Exp/Cntr(USF)=0,0
Exp/Cntr=0.3,0.1

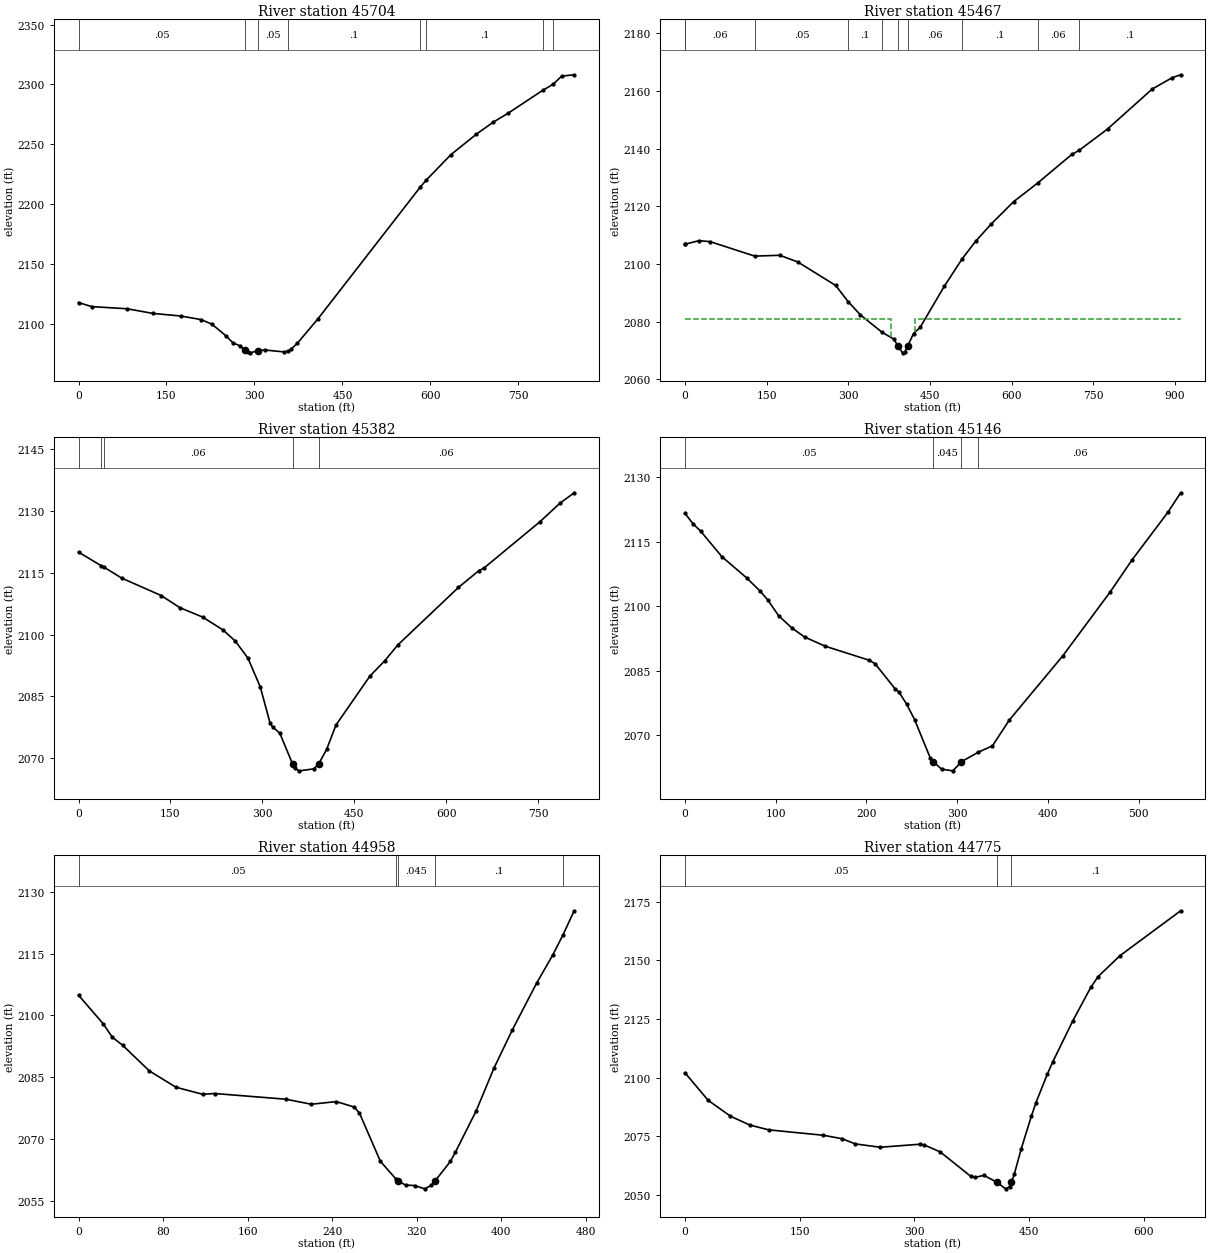
Type RM Length L Ch R = 1 ,45704   ,230.2,236.3,230.9
XS GIS Cut Line= 4
2435670.06072824630218.7806130542435867.55483549630136.623064442
2436031.86993271630026.0263643872436371.55979717629757.434378539
#Sta/Elev= 30
       0 2117.63    22.4 2114.26      83 2112.44   126.4 2108.58     174 2106.39
   208.5 2103.45   227.4 2099.58   251.5 2089.79   263.5 2083.86   275.6  2081.4
   283.82077.597   288.6 2075.89   292.4  2075.6   306.8 2077.48   317.3 2077.99
     350  2076.4  356.912076.972   362.4 2078.64   373.1 2083.63   407.7 2103.71
  582.112213.822  593.01 2220.08   634.9 2241.26   678.4  2258.4   707.2 2268.47
   731.8 2275.68  791.062294.928  809.492300.181   823.6  2306.9     845 2308.02
#Mann= 8 ,-1 , 0
       0     .05       0   283.8    .045       0   306.8     .05       0
  356.91      .1       0  582.11     .12       0  593.01      .1       0
  791.06     .12       0  809.49      .1       0
Bank Sta=283.8,306.8
XS Rating Curve= 0 ,0
Exp/Cntr(USF)=0,0
Exp/Cntr=0.5,0.3

Type RM Length L Ch R = 1 ,45467   ,84.6,84.9,96.6
XS GIS Cut Line= 4
2435722.27185039630293.3812471472436014.42428041630216.435428147
2436187.95230395630242.5579263132436609.64406006630339.584348073
#Sta/Elev= 30
       0 2106.85     .442106.859    25.3 2108.08      46 2107.76  128.03 2102.73
   174.2 2103.01   207.3 2100.68   276.8 2092.54  299.792086.887   322.1 2082.34
  362.232076.244   383.3 2073.95   391.32071.557   399.5 2069.15   403.6 2069.31
   409.1 2071.55   419.7 2075.83   431.9 2077.99   476.4  2092.3  509.142101.795
   533.8 2107.87   562.6 2113.92   603.6 2121.62  647.472128.057   710.3    2138
  723.63 2139.41     776 2146.83   858.1 2160.72     895 2164.68   910.3 2165.67
#Mann= 10 ,-1 , 0
       0     .05       0     .44     .06       0  128.03     .05       0
  299.79      .1       0  362.23     .06       0   391.3    .045       0
   409.1     .06       0  509.14      .1       0  647.47     .06       0
  723.63      .1       0
#XS Ineff= 2 , 0
             378    2081     422            2081
Permanent Ineff=
       F       F
Bank Sta=391.3,409.1
XS Rating Curve= 0 ,0
Exp/Cntr(USF)=0,0
Exp/Cntr=0.5,0.3

Type RM Length L Ch R = 1 ,45382   ,236,236.5,218.1
XS GIS Cut Line= 4
2435797.98072418630370.3715780552436074.13284765630304.132386276
2436210.34301666630306.9312253652436584.45450826630412.354164393
#Sta/Elev= 30
       0 2120.02   37.452116.678   41.652116.359    70.7 2113.69     135 2109.47
   165.3 2106.54   202.6 2104.24   235.8 2101.12   255.7 2098.44   276.4  2094.3
   296.6  2087.3   312.6 2078.51   316.6 2077.58   328.6 2076.02   349.5 2068.52
   352.6 2067.51   360.6  2066.9   383.9 2067.38   391.72068.511   404.9 2072.09
   420.2 2078.03   475.6 2089.92   499.6  2093.6     521 2097.46   620.1 2111.45
   653.4 2115.52   661.7 2116.15   753.1  2127.4   785.4 2131.86   808.9 2134.43
#Mann= 5 ,-1 , 0
       0     .06       0   37.45     .05       0   41.65     .06       0
   349.5    .045       0   391.7     .06       0
Bank Sta=349.5,391.7
XS Rating Curve= 0 ,0
Exp/Cntr(USF)=0,0
Exp/Cntr=0.5,0.3

Type RM Length L Ch R = 1 ,45146   ,192.7,188.2,184.3
XS GIS Cut Line= 4
2436062.93749129630595.2116515572436253.25854936630490.721658892
2436383.87104019630439.4096089232436572.32620554630425.415413476
#Sta/Elev= 30
       0 2121.61     8.9 2119.16    17.3 2117.45    40.8  2111.5    68.2 2106.54
    82.6 2103.55    91.4 2101.41   103.2 2097.78   117.9 2094.91   132.1 2092.79
   154.9 2090.66   203.4 2087.39   209.7 2086.57   231.6 2080.77   235.9 2080.01
   244.5 2077.14   253.1 2073.61   270.3 2064.71   273.62063.805   282.9 2062.06
   295.3 2061.67   304.82063.797  323.312066.003     339  2067.5   357.4 2073.45
   416.5 2088.44   468.9 2103.35   492.7 2110.73   532.4 2121.86   546.4 2126.39
#Mann= 4 ,-1 , 0
       0     .05       0   273.6    .045       0   304.8     .05       0
  323.31     .06       0
Bank Sta=273.6,304.8
XS Rating Curve= 0 ,0
Exp/Cntr(USF)=0,0
Exp/Cntr=0.3,0.1

Type RM Length L Ch R = 1 ,44958   ,185.1,182.3,180.8
XS GIS Cut Line= 4
2436233.66667574630742.617176923 2436434.2501438630587.748080652
2436534.07540465630500.0511225232436584.45450825630434.744877107
#Sta/Elev= 30
       0 2104.93    23.4 2097.98    31.9 2094.75    41.8 2092.76    67.1 2086.53
    92.3 2082.58   117.5 2080.88   128.9 2081.07   195.9 2079.69   220.2 2078.47
   243.9 2079.11   260.8 2077.78   265.7 2076.34   285.5 2064.63  300.592060.214
   301.82059.893   309.3 2058.85     318 2058.74   327.4 2057.94   333.5 2058.76
   337.32059.885   351.7 2064.58   356.4  2066.8   376.2  2076.9   392.8 2087.15
   410.4 2096.55   433.2 2107.81   448.4  2114.6  458.112119.496   468.8 2125.41
#Mann= 5 ,-1 , 0
       0     .05       0  300.59      .1       0   301.8    .045       0
   337.3      .1       0  458.11     .06       0
Bank Sta=301.8,337.3
XS Rating Curve= 0 ,0
Exp/Cntr(USF)=0,0
Exp/Cntr=0.3,0.1

Type RM Length L Ch R = 1 ,44775   ,249.5,256.1,260.9
XS GIS Cut Line= 4
2436261.65506663 630790.197441442436543.40486828630708.098161489
2436669.35262729630610.138793366 2436833.5511872630504.715854338
#Sta/Elev= 30
       0    2102    30.3 2090.29    59.5 2083.52    84.5 2079.77   109.5 2077.69
     181 2075.39   205.3 2073.92   222.9  2071.7   255.3 2070.28   307.8 2071.58
   312.9 2071.26   333.8  2068.3   373.7  2057.9   379.4 2057.43   390.8 2058.32
   407.82055.401   419.3 2052.56   424.4 2053.52   426.92055.353   430.7 2058.84
   439.6 2069.46     453 2083.55     459 2089.26   473.8 2101.39   481.2 2106.81
     507 2124.04   530.7 2138.43   540.3 2143.01   568.8  2151.9   648.2 2171.05
#Mann= 3 ,-1 , 0
       0     .05       0   407.8    .045       0   426.9      .1       0
Bank Sta=407.8,426.9
XS Rating Curve= 0 ,0
Exp/Cntr(USF)=0,0
Exp/Cntr=0.3,0.1