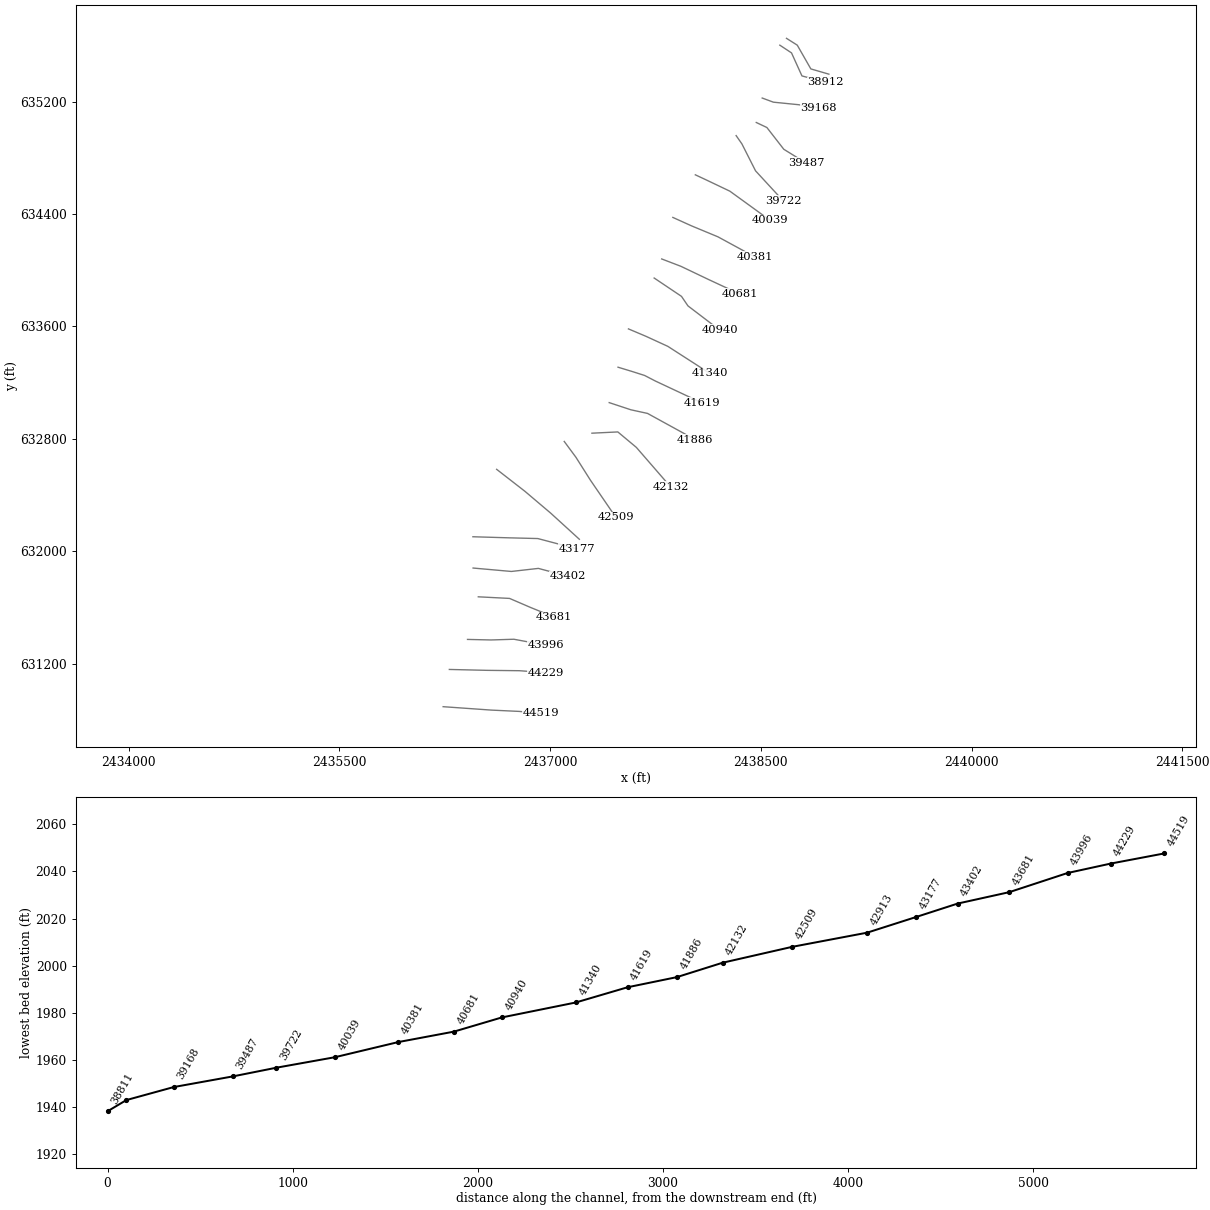
HEC-RAS study REEDSCK.prj: REEDSCK

--- REEDSCK.g01 (geometry) --- (continued)

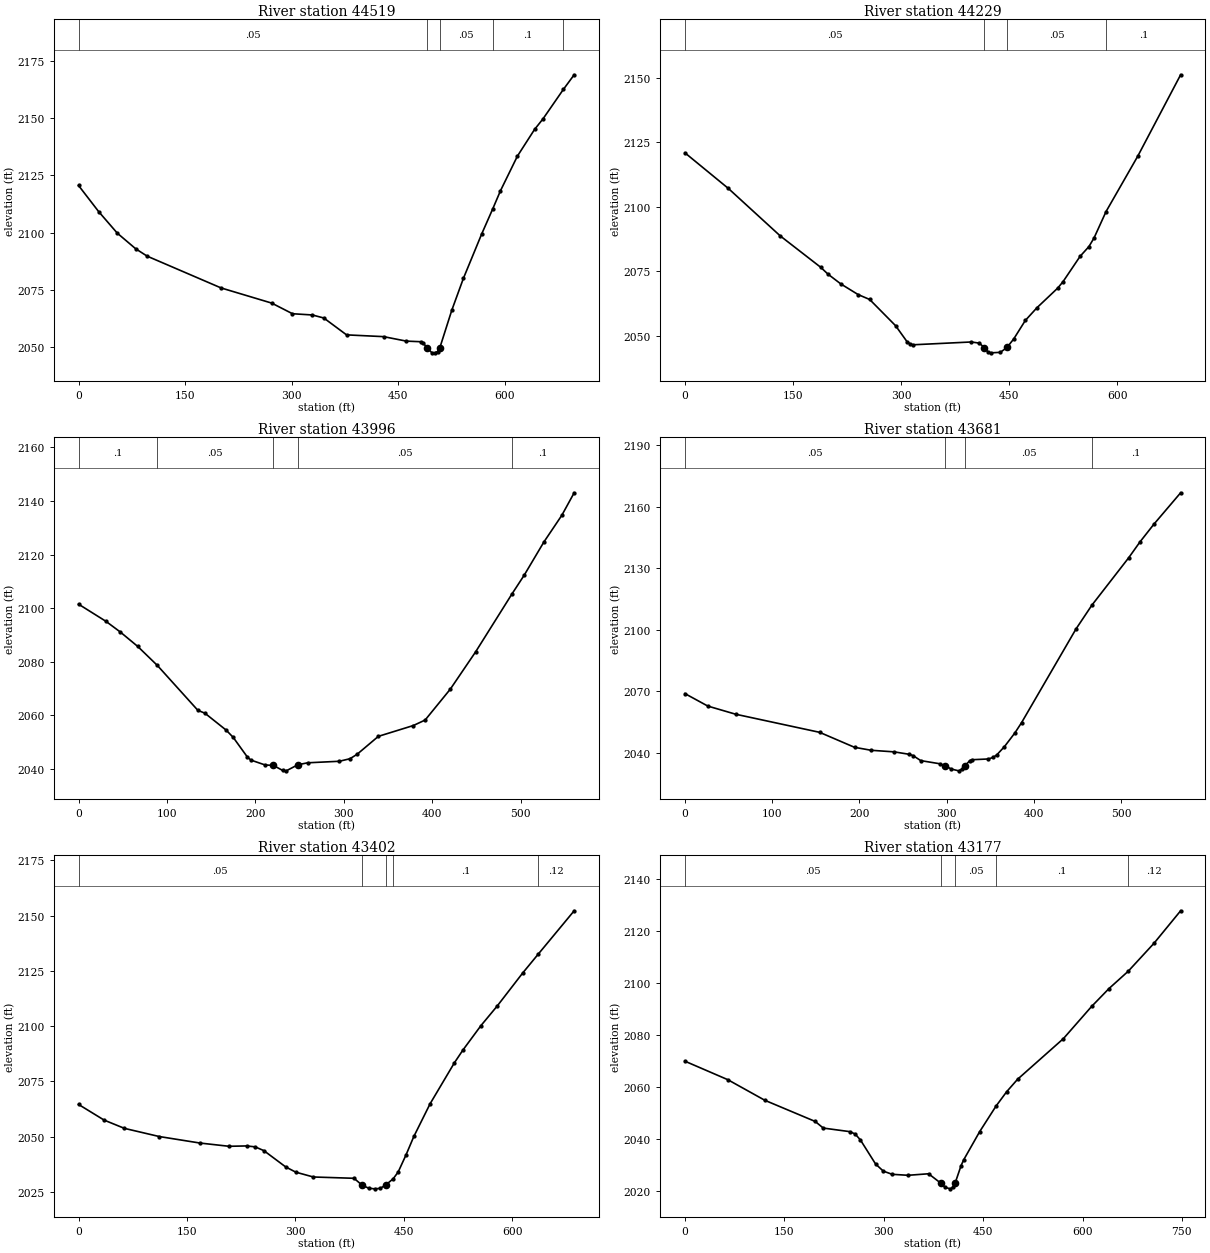
Type RM Length L Ch R = 1 ,44519   ,293.5,290.6,290.2
XS GIS Cut Line= 4
2436238.33140755630892.8215413792436581.65566917630868.564935939
2436779.44029814630859.2354723082436934.30939441630845.241276862
#Sta/Elev= 30
       0 2120.58    28.4 2109.17    54.6 2099.79    80.6 2092.96    96.7 2089.76
   200.7 2075.92   271.9 2069.32   301.2 2064.68   329.2 2064.14   345.3 2062.82
   377.3 2055.47   429.4  2054.7   461.4 2052.75   481.4 2052.49   485.4 2051.88
   490.42049.853   497.4  2047.7   501.4 2047.64   505.4 2048.22   508.62049.852
   525.5 2066.26   541.8 2080.11   567.6 2099.49  582.922110.256     594  2118.3
   617.8 2133.36   641.9 2144.97   653.9 2149.63  682.482162.426   697.7 2168.81
#Mann= 5 ,-1 , 0
       0     .05       0   490.4    .045       0   508.6     .05       0
  582.92      .1       0  682.48     .12       0
Bank Sta=490.4,508.6
XS Rating Curve= 0 ,0
Exp/Cntr(USF)=0,0
Exp/Cntr=0.3,0.1

Type RM Length L Ch R = 1 ,44229   ,228.7,232.7,234.1
XS GIS Cut Line= 4
2436282.53821993631157.8858084862436551.28820106631151.486999411
2436781.64532775631148.9274757812436969.77031454631134.850095817
#Sta/Elev= 30
       0 2120.83    60.2 2107.04   132.2 2088.64   188.3 2076.49   198.5 2073.81
   216.3 2070.02   240.3  2065.9   256.3    2064   292.3 2053.82   308.3 2047.58
   312.3 2046.78   316.4 2046.44   397.1 2047.53   408.3  2047.1   415.3 2045.38
   420.3 2043.66   424.3 2043.32   437.6 2043.51   446.9 2045.42   456.3 2048.75
   472.3 2055.88   488.3 2060.77   517.1 2068.38   524.4 2070.82   548.4 2080.77
   560.5 2084.49   567.6 2087.82  584.332098.092   628.3 2119.54   687.8  2151.1
#Mann= 4 ,-1 , 0
       0     .05       0   415.3    .045       0   446.9     .05       0
  584.33      .1       0
Bank Sta=415.3,446.9
XS Rating Curve= 0 ,0
Exp/Cntr(USF)=0,0
Exp/Cntr=0.3,0.1

Type RM Length L Ch R = 1 ,43996   ,320.8,314.8,275
XS GIS Cut Line= 4
2436411.79416323631371.6060315782436579.44296099631367.766746133
2436741.97271148631372.8857933932436968.49055272631330.653653501
#Sta/Elev= 30
       0 2101.49      31 2095.09      47 2091.17      67 2085.72   89.122078.658
     135  2061.9     143 2060.82     167 2054.52     175 2051.81     191 2044.48
     195 2043.34     211 2041.53   220.5 2041.34     231 2039.47     235 2039.33
   248.12041.594   259.3 2042.33   295.1  2042.9   307.1 2043.85   315.1 2045.49
   339.2 2052.19   378.8 2056.23   392.1 2058.27   420.6  2069.8   449.3 2083.74
  490.17 2105.21   504.2  2112.3   526.4 2124.64   546.7  2134.6   560.7 2143.02
#Mann= 5 ,-1 , 0
       0      .1       0   89.12     .05       0   220.5    .045       0
   248.1     .05       0  490.17      .1       0
Bank Sta=220.5,248.1
XS Rating Curve= 0 ,0
Exp/Cntr(USF)=0,0
Exp/Cntr=0.3,0.1

Type RM Length L Ch R = 1 ,43681   ,268.3,278.8,284.4
XS GIS Cut Line= 4
2436488.57987213631674.9095817152436711.25842792631663.391725381
2436859.71079845631599.4036346352437029.91911984631530.296496629
#Sta/Elev= 30
       0 2068.89    26.2 2062.81    58.2 2058.83   154.4    2050   194.4 2042.69
   213.5 2041.24   239.8 2040.47   257.3 2039.27   261.6 2038.63   270.3  2036.2
   292.1 2034.67   298.52033.702   305.2 2032.11   313.9 2031.21   317.3 2031.96
   321.12033.722   326.5 2036.18   329.5 2036.64   347.8    2037   353.1 2037.73
   357.4 2038.95   366.2 2042.98   378.2 2049.67     386 2054.78   448.3 2100.42
  466.552112.058   508.8 2135.22   521.7 2142.93   537.8 2151.65   568.3  2166.9
#Mann= 4 ,-1 , 0
       0     .05       0   298.5    .045       0   321.1     .05       0
  466.55      .1       0
Bank Sta=298.5,321.1
XS Rating Curve= 0 ,0
Exp/Cntr(USF)=0,0
Exp/Cntr=0.3,0.1

Type RM Length L Ch R = 1 ,43402   ,227.2,225.4,223.4
XS GIS Cut Line= 4
2436451.46677949631879.6714721032436724.05604607631855.355997619
2436916.02031831631877.1119484732437127.18101777631820.802428616
#Sta/Elev= 30
       0 2064.57    35.4 2057.47    63.5 2053.73   111.7 2050.03   167.9 2047.09
   208.1 2045.62   232.3 2045.78   244.2 2045.37   256.3 2043.66   286.5 2036.28
   300.5 2033.91   324.7 2031.73     381 2031.14   391.72028.144   401.2 2026.65
   409.5 2026.37   417.3 2026.58   424.82028.131  435.092030.901     442 2033.97
   452.9 2041.73   463.7 2050.06   486.2 2064.87   519.9 2083.46   531.8 2089.27
   556.6 2100.26   578.8 2109.01   614.3 2124.05  635.742132.567   685.4 2152.17
#Mann= 5 ,-1 , 0
       0     .05       0   391.7    .045       0   424.8     .05       0
  435.09      .1       0  635.74     .12       0
Bank Sta=391.7,424.8
XS Rating Curve= 0 ,0
Exp/Cntr(USF)=0,0
Exp/Cntr=0.3,0.1

Type RM Length L Ch R = 1 ,43177   ,271.9,263.7,257.2
XS GIS Cut Line= 4
2436450.18701768632102.3500278992436708.69890429 632094.67145701
2436912.18103287 632089.552409752437188.60958489  632016.6059863
#Sta/Elev= 30
       0 2069.75    64.6 2062.65   120.6 2054.71   196.6 2046.57   208.7 2044.03
   248.7 2042.66   256.7 2041.78   264.7  2039.5   287.7  2030.2   299.4 2027.46
   312.7 2026.24   336.7 2025.86   367.7 2026.45   386.42022.769   392.7  2021.2
   400.7 2020.65   404.7 2021.29   407.62022.754   416.7 2029.57   420.7 2031.83
   444.7 2042.62   469.4 2052.46   485.5 2058.01   502.1 2062.83   571.2 2078.45
   613.7 2090.81   639.9 2097.69  668.982104.366   707.8  2115.1   748.1 2127.63
#Mann= 5 ,-1 , 0
       0     .05       0   386.4    .045       0   407.6     .05       0
   469.4      .1       0  668.98     .12       0
Bank Sta=386.4,407.6
XS Rating Curve= 0 ,0
Exp/Cntr(USF)=0,0
Exp/Cntr=0.3,0.1

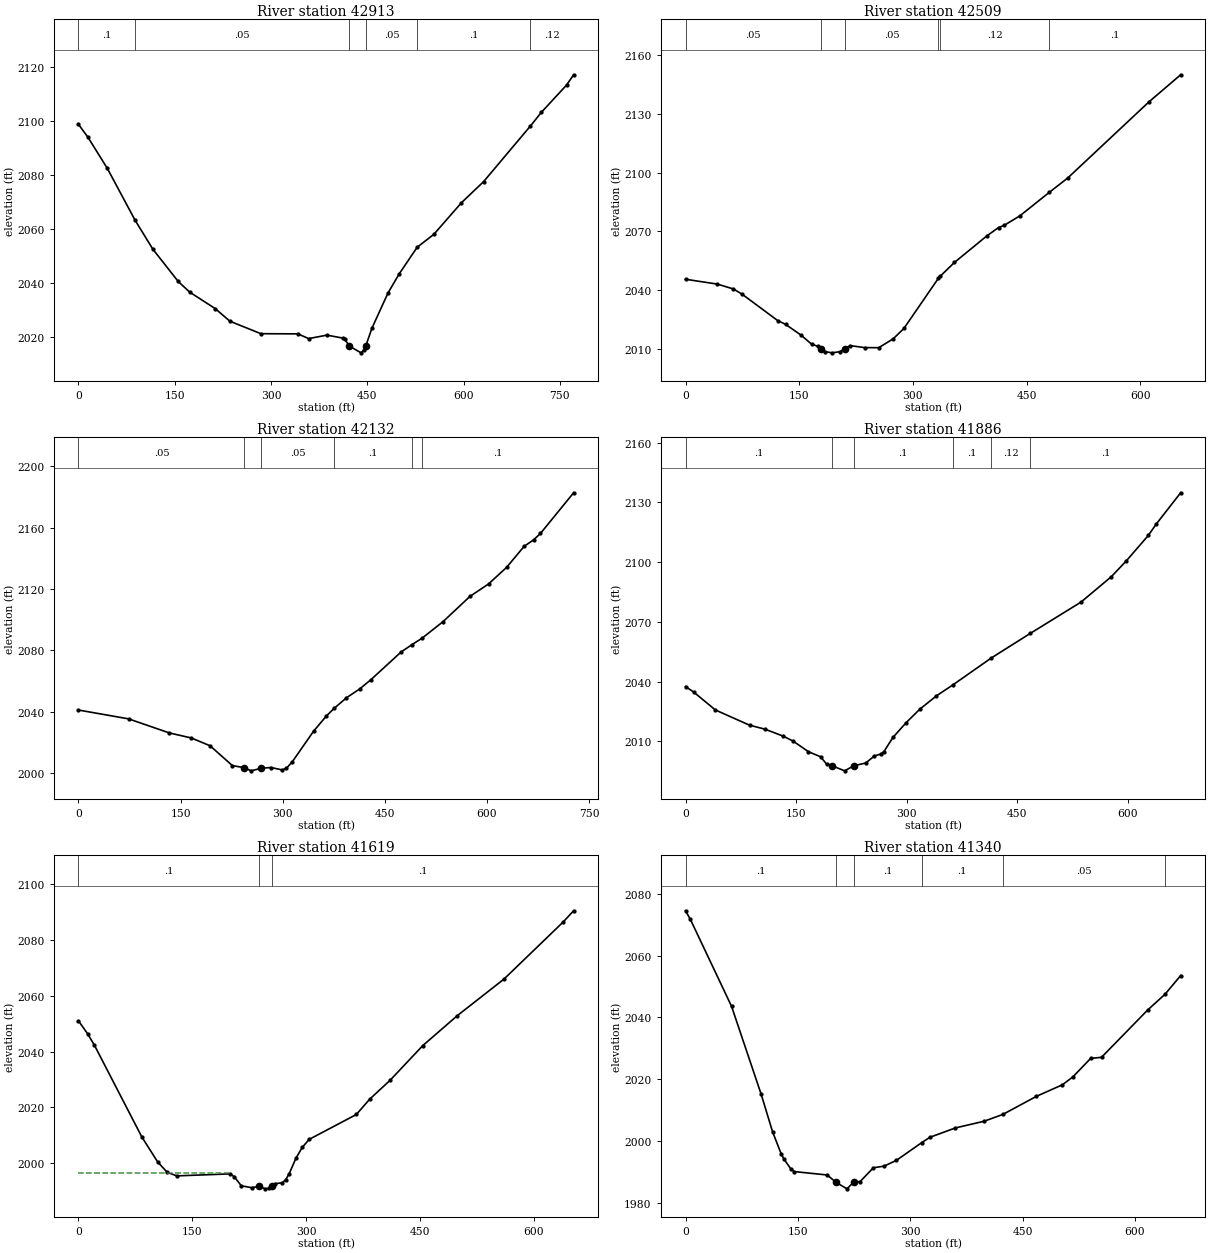
Type RM Length L Ch R = 1 ,42913   ,408.9,404.5,399.4
XS GIS Cut Line= 4
2436619.11557725632582.2607084962436820.03818219632426.129767075
2437004.32388354632269.9988256552437207.80601211632084.433362491
#Sta/Elev= 30
       0 2098.67    14.7 2093.92    44.9 2082.37   88.182063.165     116 2052.38
   155.4 2040.47   173.2 2036.53   213.1 2030.41   235.9 2025.74   284.2 2021.12
   341.9 2021.06   358.5 2019.31   387.1 2020.59   411.9 2019.49   414.8 2019.12
   422.12016.507   440.3 2014.03   445.1 2015.14   447.4 2016.47   457.2 2023.17
   482.2  2036.2   499.9 2043.37  527.63 2053.14   553.7 2057.95   596.7 2069.66
   631.2 2077.47  704.192098.097   721.2 2103.14   760.4 2113.24   771.4 2117.05
#Mann= 6 ,-1 , 0
       0      .1       0   88.18     .05       0   422.1    .045       0
   447.4     .05       0  527.63      .1       0  704.19     .12       0
Bank Sta=422.1,447.4
XS Rating Curve= 0 ,0
Exp/Cntr(USF)=0,0
Exp/Cntr=0.3,0.1

Type RM Length L Ch R = 1 ,42509   ,373.5,376.5,380.5
XS GIS Cut Line= 4
2437100.30601966632780.6237898092437183.49053763632668.004750096
2437287.15124464632504.1952377862437467.59766054632240.564303911
#Sta/Elev= 30
       0 2045.58    41.9 2043.12      63 2040.65    74.5    2038   121.5 2024.53
     132 2022.56   151.9 2017.22   166.4 2012.44   174.5 2011.38   178.52010.129
   183.8 2008.66   193.4 2008.03   204.1 2008.65     2102010.115   217.1 2011.72
   236.2 2010.71   254.9 2010.65   273.9 2015.15   288.1 2020.46  333.492045.999
  335.852047.049   354.8 2054.16   397.8 2067.79     413 2071.96   420.8 2073.18
     441 2077.91  479.872089.906   504.3 2097.26   611.7 2136.19   653.3 2149.94
#Mann= 6 ,-1 , 0
       0     .05       0   178.5    .045       0     210     .05       0
  333.49      .1       0  335.85     .12       0  479.87      .1       0
Bank Sta=178.5,210
XS Rating Curve= 0 ,0
Exp/Cntr(USF)=0,0
Exp/Cntr=0.3,0.1

Type RM Length L Ch R = 1 ,42132   ,240,246.7,247
XS GIS Cut Line= 4
2437297.38933916632839.4928332952437481.67504051   632848.451166
2437613.49050745632738.3916499162437856.64525228632458.123812448
#Sta/Elev= 30
       0 2040.97    73.6 2035.21   133.5 2026.02   165.6 2022.75   193.2 2017.67
   226.1 2004.68   243.72003.338   253.6 2001.28   268.7 2003.02   282.9 2003.44
   299.3 2001.87   305.5 2002.97   314.2 2007.27   345.4 2027.21   364.2  2037.1
  375.332041.985   393.6 2048.97   413.1 2054.75   429.7 2060.85   474.1 2078.95
  489.652083.596  504.692087.866   535.2 2098.56   575.1 2115.18   602.3 2123.26
     629 2134.17   654.5 2147.78   668.7 2152.13   678.6 2156.25   727.3  2182.8
#Mann= 6 ,-1 , 0
       0     .05       0   243.7    .045       0   268.7     .05       0
  375.33      .1       0  489.65     .12       0  504.69      .1       0
Bank Sta=243.7,268.7
XS Rating Curve= 0 ,0
Exp/Cntr(USF)=0,0
Exp/Cntr=0.3,0.1

Type RM Length L Ch R = 1 ,41886   ,268,266.5,261.8
XS GIS Cut Line= 4
2437420.24647339633057.052341832  2437575.097653633005.861869235
2437692.83573997632980.2666329372438033.25238274632793.421407958
#Sta/Elev= 30
       0  2037.5    11.1 2034.72    40.5 2025.74    86.9 2018.09     108 2016.08
   132.7 2012.57   145.9 2010.12   166.8 2004.79   183.2 2002.25   191.4 1998.57
     1991997.707   215.9 1995.18   228.3 1997.72   244.6 1999.11   256.1 2002.61
   265.1 2003.65   269.2  2004.8   281.4 2011.92   299.4 2019.38   317.7 2026.04
   340.5 2032.83  362.512038.246  414.872051.816   467.9 2064.19   536.7  2079.9
   577.7 2092.61   598.3 2100.64     628 2113.35   638.9 2119.14   671.9 2134.77
#Mann= 6 ,-1 , 0
       0      .1       0     199    .045       0   228.3      .1       0
  362.51      .1       0  414.87     .12       0   467.9      .1       0
Bank Sta=199,228.3
XS Rating Curve= 0 ,0
Exp/Cntr(USF)=0,0
Exp/Cntr=0.3,0.1

Type RM Length L Ch R = 1 ,41619   ,280.3,279.4,280
XS GIS Cut Line= 5
2437482.95480232633309.165419372 2437584.0559857633278.451135814
2437672.35955093633250.2963758862437749.14525983633210.623759623
2438081.88333171633054.492818203
#Sta/Elev= 30
       0 2050.99    12.3 2046.24    20.9 2042.31    83.4 2009.47   104.3 2000.51
   116.9 1996.79   129.5 1995.52   199.7 1996.23   205.3  1995.2   214.5 1991.97
     228  1991.3   238.3 1991.73   246.1 1990.88   250.6 1991.05   255.1 1992.01
     259 1992.72   268.6 1993.07   273.1 1994.19   277.6 1996.31   286.5 2001.85
   294.8  2005.7   303.8 2008.56   366.1 2017.48   383.7 2022.98   410.3 2029.66
   453.6 2042.13   499.3 2052.89   560.5 2065.91   638.3 2086.28   652.3 2090.36
#Mann= 3 ,-1 , 0
       0      .1       0   238.3    .045       0   255.1      .1       0
#XS Ineff= 2 , 0
          199.43 1996.58
Permanent Ineff=
       F       F
Bank Sta=238.3,255.1
XS Rating Curve= 0 ,0
Exp/Cntr(USF)=0,0
Exp/Cntr=0.3,0.1

Type RM Length L Ch R = 1 ,41340   ,387.3,399.5,391.7
XS GIS Cut Line= 4
2437557.18098759633581.7546859512437681.31788364633529.284451539
2437837.44882506633457.6177899032438135.63332793633265.653517665
#Sta/Elev= 30
       0 2074.49     6.4 2071.74    61.4 2043.58   101.1    2015   116.3 2002.86
   127.6 1995.85   131.6    1994   140.7 1990.87   145.1 1990.02   189.2 1988.92
     201 1986.52   215.6 1984.43   224.4 1986.58   233.2 1986.79   250.8 1991.25
   265.2 1991.79   281.6 1993.65  315.321999.383   326.4 2001.13   360.4 2004.16
   398.5 2006.31  423.672008.521   468.6 2014.39   503.4 2018.15   517.4 2020.72
     541 2026.68   555.5 2027.03   617.3 2042.39  640.372047.473   661.2  2053.5
#Mann= 6 ,-1 , 0
       0      .1       0     201    .045       0   224.4      .1       0
  315.32      .1       0  423.67     .05       0  640.37      .1       0
Bank Sta=201,224.4
XS Rating Curve= 0 ,0
Exp/Cntr(USF)=0,0
Exp/Cntr=0.3,0.1

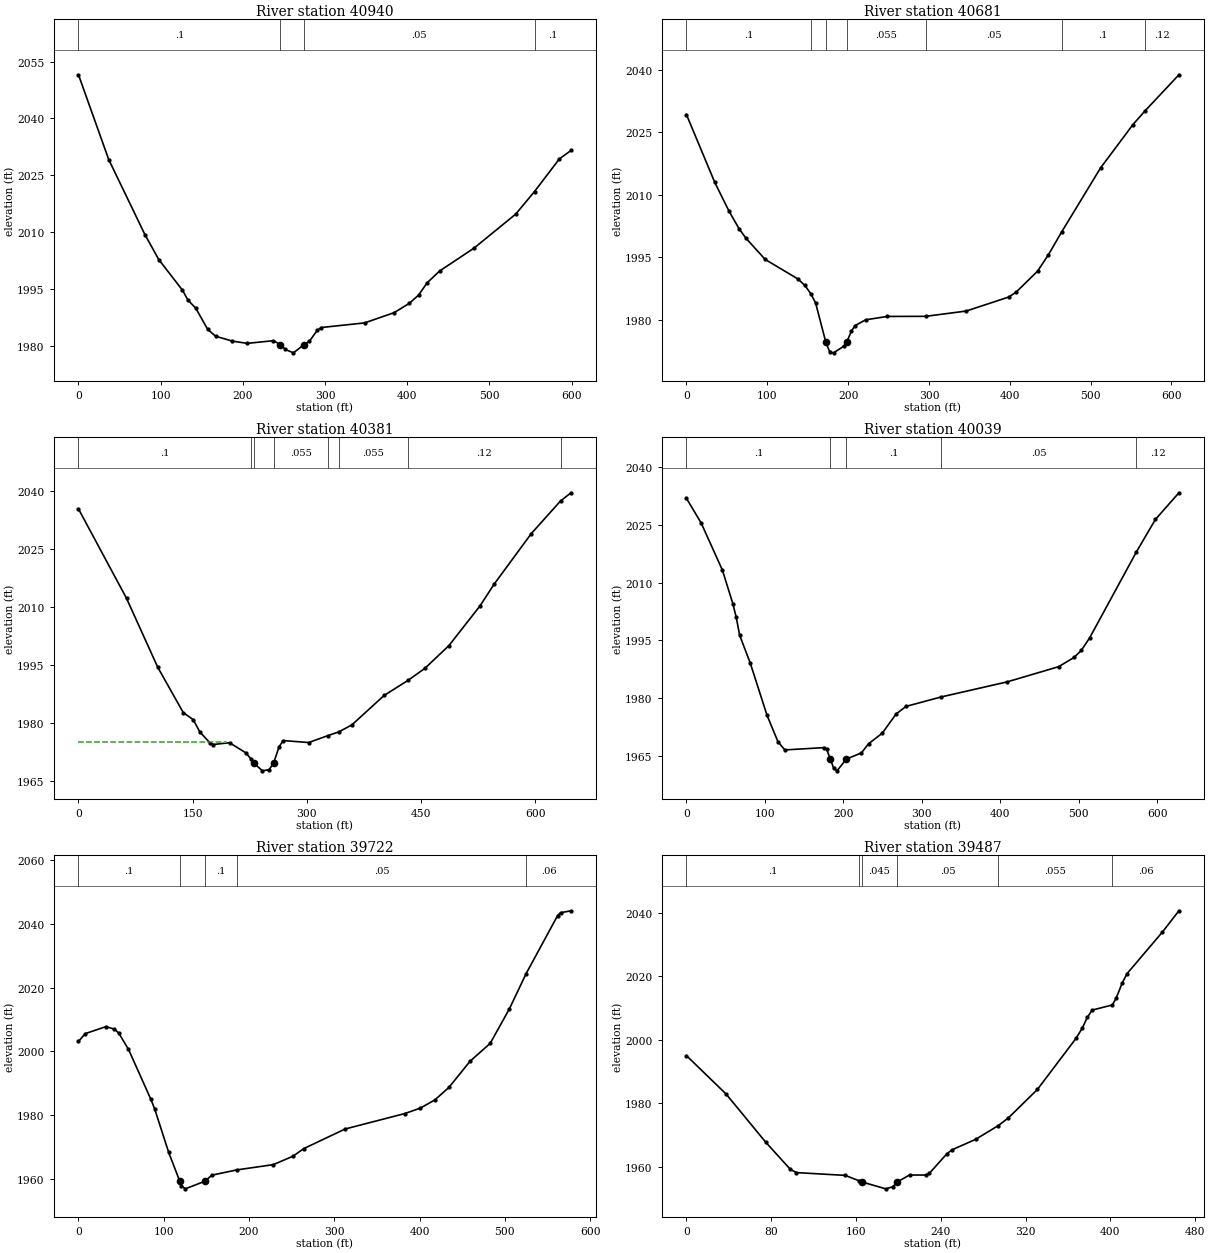
Type RM Length L Ch R = 1 ,40940   ,194.3,259.1,261.4
XS GIS Cut Line= 4
2437740.18692712633943.9272795742437934.71072299633813.391574452
2437980.78214833633745.5641982612438206.02022776633574.076115062
#Sta/Elev= 30
       0  2051.5    36.8 2029.12    80.8 2009.32    97.7 2002.71   126.5 1994.65
   133.1 1992.05   142.8 1989.86   157.2 1984.29   166.9 1982.47   187.1 1981.19
   205.4 1980.59   237.3  1981.3   245.61980.254   251.8 1978.98   261.5 1978.09
   274.5 1980.25   280.8 1981.09   290.5 1984.02   295.3 1984.77   348.1 1985.99
   384.1  1988.7   402.3 1991.12   413.8 1993.32   424.3 1996.59   439.4 1999.69
   481.1  2005.7     532 2014.71  554.912020.676   585.2 2029.31   599.3 2031.51
#Mann= 4 ,-1 , 0
       0      .1       0   245.6    .045       0   274.5     .05       0
  554.91      .1       0
Bank Sta=245.6,274.5
XS Rating Curve= 0 ,0
Exp/Cntr(USF)=0,0
Exp/Cntr=0.3,0.1

Type RM Length L Ch R = 1 ,40681   ,299.1,300.1,300.2
XS GIS Cut Line= 4
2437793.93692335634079.5820319562437930.87143755634027.111797545
2438129.23451886 633932.409423242438349.35355103633830.028478046
#Sta/Elev= 30
       0 2029.29    35.1 2012.98    52.3 2006.23    65.1 2001.87    73.7 1999.58
    97.4  1994.5   137.9 1989.81   146.6 1988.24  153.89 1986.25   159.8 1984.06
   172.41974.632   177.5 1972.17     182 1972.07   195.3 1973.73   198.3 1974.65
   204.1 1977.28   208.6 1978.61   221.7    1980   248.5 1980.81  295.881980.834
     346  1982.1     399 1985.49   407.9 1986.66   434.3 1991.67   447.5 1995.53
  464.052001.069   512.3 2016.48   552.4 2026.89  567.232030.154   609.2 2038.83
#Mann= 7 ,-1 , 0
       0      .1       0  153.89    .055       0   172.4    .045       0
   198.3    .055       0  295.88     .05       0  464.05      .1       0
  567.23     .12       0
Bank Sta=172.4,198.3
XS Rating Curve= 0 ,0
Exp/Cntr(USF)=0,0
Exp/Cntr=0.3,0.1

Type RM Length L Ch R = 1 ,40381   ,344.2,341.7,340.4
XS GIS Cut Line= 4
2437873.28215588634375.2070112042438006.37738463634315.058205902
2438194.50237142634236.9927351922438455.57378167634094.939173735
#Sta/Elev= 30
       0 2035.29    63.1 2012.21   104.1 1994.41   137.7 1982.68   150.8 1980.86
   159.4 1977.71   172.4 1974.92   177.1 1974.45   198.4 1974.91   219.9  1972.3
  226.031970.831   230.61969.583   241.7 1967.65   250.4 1967.96   256.21969.571
   263.4 1973.81   268.9 1975.47   302.4 1974.96   328.11976.773  341.821977.696
   359.1 1979.51   401.6 1987.13  432.681990.981     455 1994.11   486.6 1999.98
   527.6 2010.28   545.8  2015.8   594.8 2028.91  633.222037.334     647 2039.46
#Mann= 8 ,-1 , 0
       0      .1       0  226.03    .055       0   230.6    .045       0
   256.2    .055       0   328.1     .05       0  341.82    .055       0
  432.68     .12       0  633.22      .1       0
#XS Ineff= 2 , 0
          194.29 1975.18
Permanent Ineff=
       F       F
Bank Sta=230.6,256.2
XS Rating Curve= 0 ,0
Exp/Cntr(USF)=0,0
Exp/Cntr=0.3,0.1

Type RM Length L Ch R = 1 ,40039   ,329.7,316.9,303.6
XS GIS Cut Line= 4
2438033.25238274634678.510561341 2438115.1571389634640.117706893
2438278.96665121634562.0522361832438566.91305956 634353.45106035
#Sta/Elev= 30
       0 2031.84    18.9 2025.39    45.8 2013.25    59.1 2004.58    63.5 2000.97
    67.9 1996.31    81.2 1989.23   102.6 1975.69   116.6 1968.79   125.4 1966.66
   175.1 1967.25   178.6 1966.84   183.51964.262   187.5 1961.97   191.9 1961.24
   203.7 1964.28   222.9 1965.88   232.1 1968.27   249.5 1970.98   267.2 1975.98
   279.8 1977.93  324.43 1980.37   408.6 1984.28   474.2 1988.21   493.9 1990.61
   503.2 1992.45   513.7 1995.66  573.252017.919   597.6 2026.37   627.5 2033.26
#Mann= 5 ,-1 , 0
       0      .1       0   183.5    .045       0   203.7      .1       0
  324.43     .05       0  573.25     .12       0
Bank Sta=183.5,203.7
XS Rating Curve= 0 ,0
Exp/Cntr(USF)=0,0
Exp/Cntr=0.3,0.1

Type RM Length L Ch R = 1 ,39722   ,240.4,235.4,236.5
XS GIS Cut Line= 4
2438323.75831473634957.4986369942438364.71069281634898.629593507
2438461.97259074634706.6653212692438659.05591024634492.945098177
#Sta/Elev= 30
       0 2003.11       8 2005.56    32.4 2007.76    42.2 2006.93    47.1 2005.76
    58.6 2000.64    84.9  1984.9    89.4 1981.86   105.8 1968.21   118.81959.163
   120.7 1957.76   125.2 1956.78     1481959.142   156.6 1961.09  186.041962.744
   228.4 1964.38   251.6 1967.03   264.2 1969.42   312.8 1975.59   382.5 1980.42
   400.9 1982.14   417.9 1984.72   434.5 1988.66   459.2 1996.87   482.8 2002.47
   505.3  2013.3  525.032024.429   561.9 2042.63   565.4 2043.54   577.6 2044.15
#Mann= 5 ,-1 , 0
       0      .1       0   118.8    .045       0     148      .1       0
  186.04     .05       0  525.03     .06       0
Bank Sta=118.8,148
XS Rating Curve= 0 ,0
Exp/Cntr(USF)=0,0
Exp/Cntr=0.3,0.1

Type RM Length L Ch R = 1 ,39487   ,213,318.8,327
XS GIS Cut Line= 4
  2438467.091638635050.9212494832438542.59758508635015.087918665
2438662.89519568 634860.236739062438820.30589892634762.974841125
#Sta/Elev= 30
       0 1995.03    37.4 1982.95    74.7 1967.82    98.1 1959.21   103.8  1958.2
   149.7 1957.33  162.571955.678   165.31955.282   188.1 1953.09   194.7 1953.73
     1991955.272   210.5 1957.44   225.7 1957.43   229.2 1957.96   245.9 1964.18
     251 1965.43   272.9 1968.67  294.391973.024   303.8 1975.42   331.2 1984.38
   367.7  2000.5   373.5 2003.67   378.2 2007.03   382.9 2009.36  401.892010.965
   405.5  2013.1   411.1 2017.82   415.8 2020.84   448.8 2033.79   464.7 2040.61
#Mann= 6 ,-1 , 0
       0      .1       0  162.57     .05       0   165.3    .045       0
     199     .05       0  294.39    .055       0  401.89     .06       0
Bank Sta=165.3,199
XS Rating Curve= 0 ,0
Exp/Cntr(USF)=0,0
Exp/Cntr=0.3,0.1

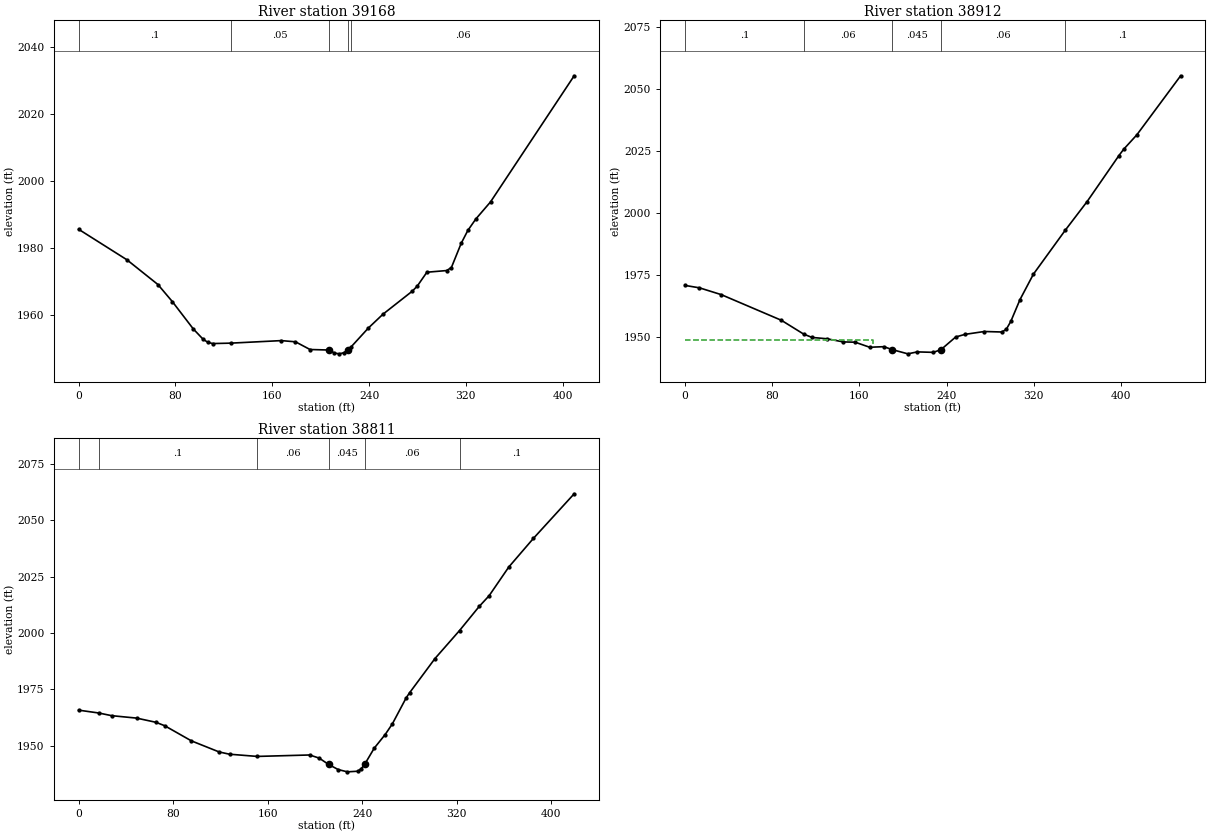
Type RM Length L Ch R = 1 ,39168   ,313.9,255.9,248.5
XS GIS Cut Line= 4
2438509.32377789635224.9688563132438588.66901042 635195.53433457
2438766.55590269635177.6176691612438911.16898778635157.141480122
#Sta/Elev= 30
       0 1985.66    39.9 1976.58    65.5 1969.22    77.4 1964.15    94.8 1955.97
   102.8 1952.95   106.8    1952   110.8 1951.64  125.931951.768   167.5 1952.52
   179.2 1952.16   191.2 1949.87   207.3 1949.71   211.3 1948.81   215.4 1948.58
   219.4 1948.93   222.2 1949.75  225.42 1950.75   239.5 1956.29   251.5 1960.38
   275.7 1967.23   279.8 1968.73   287.8 1972.88     304 1973.37     308 1974.24
   316.1 1981.45   321.6  1985.3   328.2 1988.71   340.4 1993.82   409.5 2031.36
#Mann= 5 ,-1 , 0
       0      .1       0  125.93     .05       0   207.3    .045       0
   222.2     .05       0  225.42     .06       0
Bank Sta=207.3,222.2
XS Rating Curve= 0 ,0
Exp/Cntr(USF)=0,0
Exp/Cntr=0.5,0.3

Type RM Length L Ch R = 1 ,38912   ,91.6,101.4,101.2
XS GIS Cut Line= 4
2438634.74043575635601.2188299012438717.92495372635546.189071859
2438792.15113899635382.3795595492438961.07969856635336.308134211
#Sta/Elev= 30
       0 1970.71    13.2 1969.74    33.2 1966.99    88.3 1956.63   108.9 1951.01
   116.5 1949.69     130 1949.16   145.2 1947.88   156.1 1947.76   169.3 1945.73
   182.4 1945.95   190.21944.748   204.4 1943.06   213.1 1943.85   227.7 1943.66
   234.71944.726   248.3 1949.87   256.8 1950.93   274.6 1952.09   290.6 1951.89
   294.7 1952.96   298.9  1956.2   307.3 1964.99   319.6 1975.26  348.871993.052
   368.9 2004.62     398 2023.16   402.5 2025.79   414.5 2031.58   454.7 2055.46
#Mann= 5 ,-1 , 0
       0      .1       0   108.9     .06       0   190.2    .045       0
   234.7     .06       0  348.87      .1       0
#XS Ineff= 2 , 0
             172  1948.6     252          1948.6
Permanent Ineff=
       F       F
Bank Sta=190.2,234.7
XS Rating Curve= 0 ,0
Exp/Cntr(USF)=0,0
Exp/Cntr=0.5,0.3

Type RM Length L Ch R = 1 ,38811   ,106.9,115.4,123
XS GIS Cut Line= 4
2438682.09162291635649.849778868 2438758.8773318635601.218829901
2438855.44496973635432.1815121152438983.89926678635394.883740806
#Sta/Elev= 30
       01965.715  17.1121964.441  27.9581963.261  48.9991962.184  65.337 1960.33
  72.8131958.803  95.4311952.071 118.8861947.154 127.6811946.151 151.136 1945.17
 195.4531945.809 203.5171944.433 211.5811941.591 219.6451939.334 227.3631938.324
 236.1591938.595  239.091939.689 242.0221941.638 250.1991948.882 259.4131954.894
 265.477 1959.62 277.2041971.214 280.1361973.487 301.4991988.603 322.325 2001.06
 338.985 2011.77 347.3742016.527 363.9772029.246 384.8032041.953 419.3262061.779
#Mann= 6 ,-1 , 0
       0     .05       0  17.112      .1       0 151.136     .06       0
 211.581    .045       0 242.022     .06       0 322.325      .1       0
#XS Ineff= 2 , 0
          163.64 1945.09
Permanent Ineff=
       F       F
Bank Sta=211.581,242.022
XS Rating Curve= 0 ,0
Exp/Cntr(USF)=0,0
Exp/Cntr=0.5,0.3