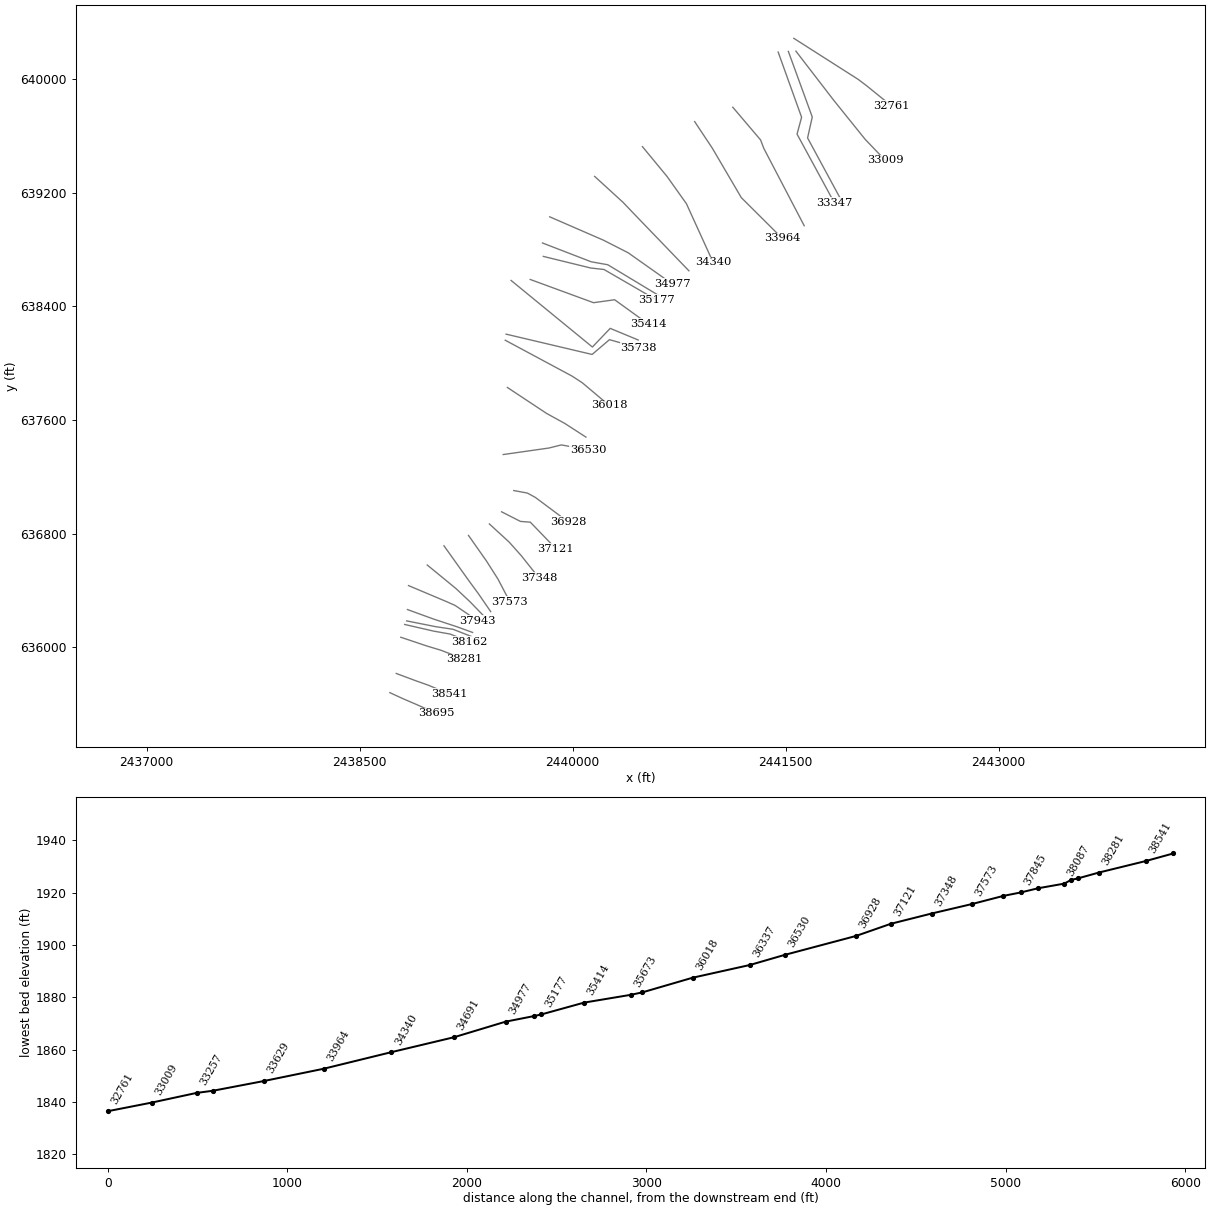
HEC-RAS study REEDSCK.prj: REEDSCK

--- REEDSCK.g01 (geometry) --- (continued)

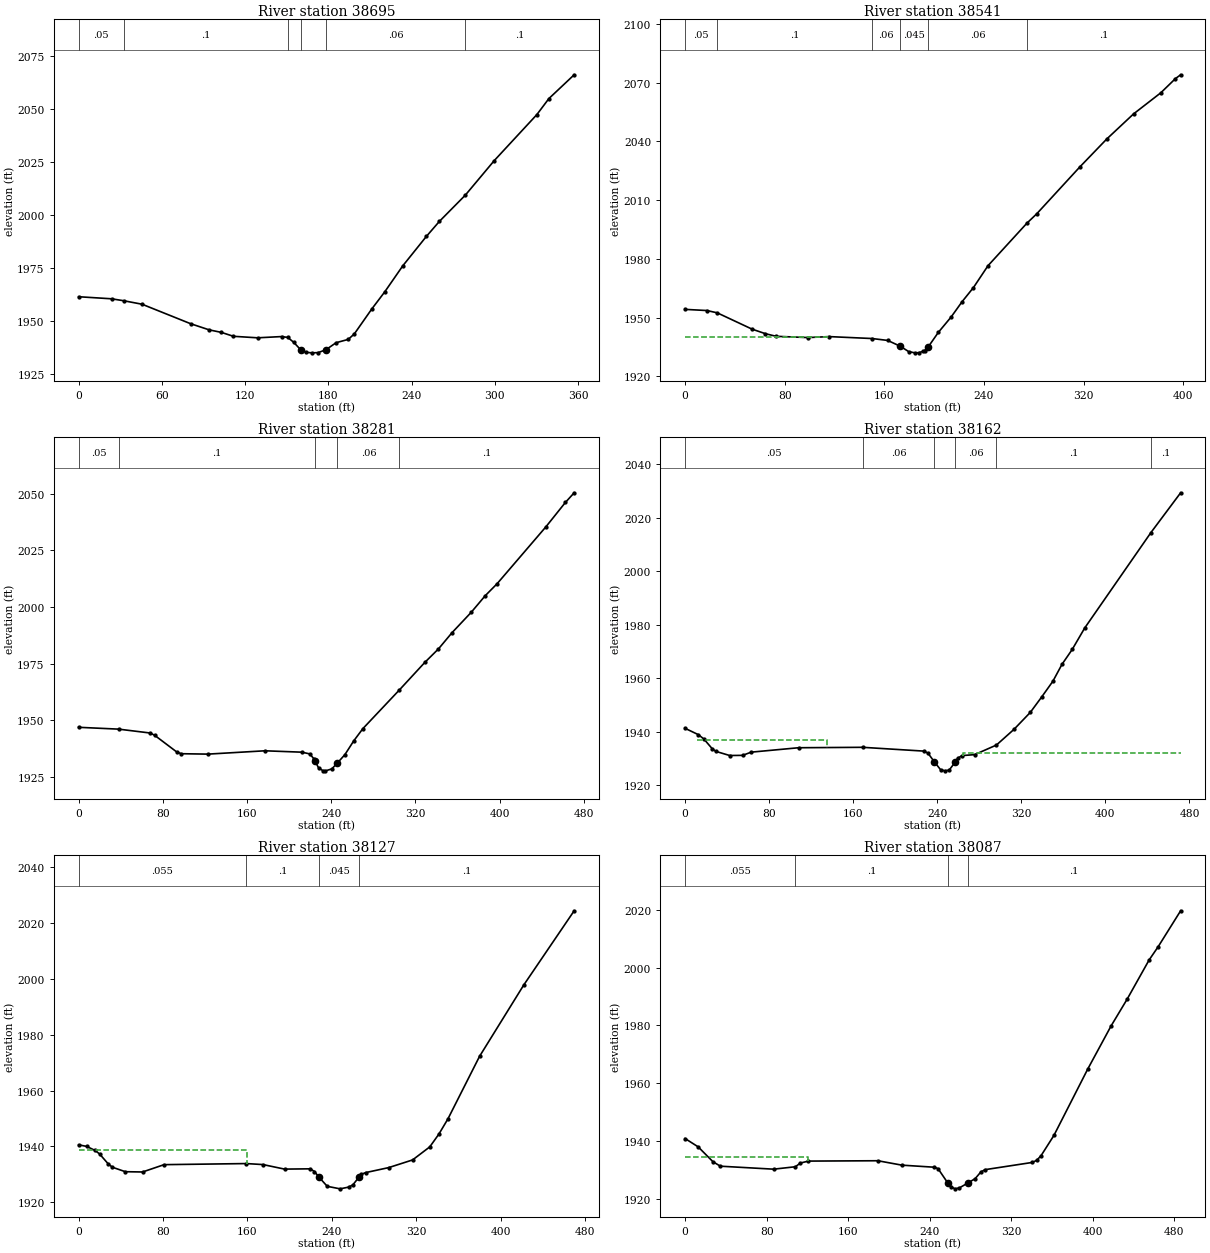
Type RM Length L Ch R = 1 ,38695   ,153.6,154.4,155.2
XS GIS Cut Line= 4
 2438713.2479879635680.4394580542438803.36515944635638.938129057
2438905.33985355635595.065295545 2439039.3298586635534.591930435
#Sta/Elev= 30
       0 1961.41    23.7 1960.44    32.4 1959.53    45.7 1957.88    80.7 1948.69
    94.1 1945.78   102.9 1944.59   111.6 1942.74     129 1942.03   146.4 1942.62
   150.8 1942.21   155.1 1939.86   160.1 1936.36   163.9 1935.18   168.2 1934.94
   172.6 1935.04   178.31936.416   185.6 1939.73   194.3 1941.27   198.7 1943.85
   211.4 1955.71   220.7 1963.75   233.7 1976.03   250.7  1989.9     260 1996.93
   278.7 2009.31   299.5 2025.57   330.3 2047.34     339 2054.92   357.2 2066.13
#Mann= 6 ,-1 , 0
       0     .05       0    32.4      .1       0   150.8     .06       0
   160.1    .045       0   178.3     .06       0   278.7      .1       0
Bank Sta=160.1,178.3
XS Rating Curve= 0 ,0
Exp/Cntr(USF)=0,0
Exp/Cntr=0.3,0.1

Type RM Length L Ch R = 1 ,38541   ,258.9,259.7,260
XS GIS Cut Line= 4
2438758.30657367635815.6152153592438885.18206518635768.185125077
2438984.78525477635732.6125573652439129.44703013635672.139192254
#Sta/Elev= 30
       0 1954.22    17.5 1953.63    25.8 1952.46    53.7 1944.15    64.5  1941.8
    73.1 1940.46    98.7 1939.82   115.8 1940.31   150.2 1939.33   162.7 1938.36
   172.91935.362   179.6 1932.64   184.6 1932.02   187.8  1932.1   190.9 1932.76
   192.3 1933.17   195.4 1935.17   203.4 1942.48   213.6 1950.27   222.5 1958.17
   231.6 1965.37   243.3 1976.54   274.6 1998.29   282.4 2003.02     317 2026.95
   338.7 2041.27   360.2 2054.07   382.1 2064.86   393.8 2072.08     398 2074.05
#Mann= 6 ,-1 , 0
       0     .05       0    25.8      .1       0   150.2     .06       0
   172.9    .045       0   195.4     .06       0   274.6      .1       0
#XS Ineff= 2 , 0
          115.44 1940.33
Permanent Ineff=
       F       F
Bank Sta=172.9,195.4
XS Rating Curve= 0 ,0
Exp/Cntr(USF)=0,0
Exp/Cntr=0.3,0.1

Type RM Length L Ch R = 1 ,38281   ,118.1,119.4,120.7
XS GIS Cut Line= 4
2438790.32188461636070.5519506292438974.11348446636008.892833261
2439072.53092179635979.2490268352439234.97898101 635916.40415721
#Sta/Elev= 30
       0 1946.87      38 1946.06      68 1944.35    72.2 1943.35    93.3 1935.95
    97.5 1935.21   122.8 1935.03     177  1936.5     212 1935.89   219.6 1935.13
   223.8 1932.79   224.8 1931.82   227.9    1929   232.1  1927.7   234.5 1927.65
   240.5 1928.49   245.9 1931.14     253 1934.82   261.4  1940.9   270.1 1946.31
   304.8 1963.39     329 1975.57   341.9  1981.5   354.8 1988.67   372.9 1997.59
   386.3 2004.97   397.6 2010.27     444 2035.41   462.5 2046.17   470.8 2050.41
#Mann= 5 ,-1 , 0
       0     .05       0      38      .1       0   224.8    .045       0
   245.9     .06       0   304.8      .1       0
#XS Ineff= 2 , 0
           178.9 1936.39
Permanent Ineff=
       F       F
Bank Sta=224.8,245.9
XS Rating Curve= 0 ,0
Exp/Cntr(USF)=0,0
Exp/Cntr=0.5,0.3

Type RM Length L Ch R = 1 ,38162   ,34.2,35.4,36.9
XS GIS Cut Line= 4
2438817.44239479636160.6431890732439021.43545035636113.768189073
2439138.62295032636092.9348557592439271.43545035636039.115411296
#Sta/Elev= 30
       0 1941.25    12.6 1938.89    17.8 1937.29    25.9 1933.59    29.2 1932.65
    42.4  1931.1    54.7 1931.15    62.9 1932.35     108    1934  168.85 1934.16
   226.9 1932.75     231 1932.05   237.1  1928.8   243.1 1925.81   247.2 1925.37
   251.3 1925.63   256.8 1928.51   259.4 1930.07   263.5 1931.07   275.6 1931.42
   296.3 1935.01     313 1940.87   328.5 1947.19   339.4 1952.99     350 1958.83
   358.7 1965.17   368.4 1970.71   380.3 1978.73  443.362014.407   471.6 2029.25
#Mann= 6 ,-1 , 0
       0     .05       0  168.85     .06       0   237.1    .045       0
   256.8     .06       0   296.3      .1       0  443.36      .1       0
#XS Ineff= 3 ,-1
   11.65  134.791936.826  141.47  230.09 1932.14     264   471.6    1932
Permanent Ineff=
       F       F       F
Bank Sta=237.1,256.8
XS Rating Curve= 0 ,0
Exp/Cntr(USF)=0,0
Exp/Cntr=0.5,0.3

Type RM Length L Ch R = 1 ,38127   ,42.5,39.8,37.3
XS GIS Cut Line= 4
2438831.33128369636185.8168002072439036.19239479636145.018189088
2439157.72017255636126.7890224312439286.19239476636076.441800207
#Sta/Elev= 30
       0 1940.59     7.6 1940.02    15.6 1938.58    19.8 1937.34      28 1933.79
      32 1932.57    44.3 1930.97    60.6 1930.87      81 1933.49  158.91 1933.88
   174.8 1933.52   195.2  1931.9   219.6    1932   223.6 1931.04   227.6 1929.13
   235.7 1925.74   247.9 1924.84     256 1925.46     260 1926.27   265.8 1929.02
   268.1 1930.05   272.1 1930.65   293.9 1932.43   316.6 1935.18   332.9 1939.85
   341.5  1944.4   350.1 1949.85   380.1 1972.24     422 1997.76   469.8 2024.31
#Mann= 4 ,-1 , 0
       0    .055       0  158.91      .1       0   227.6    .045       0
   265.8      .1       0
#XS Ineff= 2 , 0
          160.03 1938.74
Permanent Ineff=
       F       F
Bank Sta=227.6,265.8
XS Rating Curve= 0 ,0
Exp/Cntr(USF)=0,0
Exp/Cntr=0.5,0.3

Type RM Length L Ch R = 1 ,38087   ,145.1,143.8,142.5
XS GIS Cut Line= 4
2438837.08611462636265.5896075692439020.10132833636198.948198228
2439186.20752773636144.242563696 2439295.6187968636104.456647672
#Sta/Elev= 30
       0 1940.81    12.8 1937.93    27.3 1932.79    34.6 1931.23    86.9  1930.2
   108.2 1931.04   113.1 1932.33     121    1933   189.1 1933.12   212.7 1931.59
   244.4 1930.88   248.1  1930.4  257.59 1925.47   260.7  1924.1   264.9 1923.39
   269.1 1923.73  277.12 1925.36   284.5 1926.91   290.2 1929.27   294.4 1930.04
   340.7 1932.54     345  1933.3   349.2 1934.89   361.8 1941.89     395 1964.89
   417.9 1979.82   433.6 1989.06   455.2 2002.66   463.9 2007.15   486.1 2019.68
#Mann= 4 ,-1 , 0
       0    .055       0   108.2      .1       0  257.59    .045       0
  277.12      .1       0
#XS Ineff= 2 , 0
          120.16 1934.47
Permanent Ineff=
       F       F
Bank Sta=257.59,277.12
XS Rating Curve= 0 ,0
Exp/Cntr(USF)=0,0
Exp/Cntr=0.3,0.1

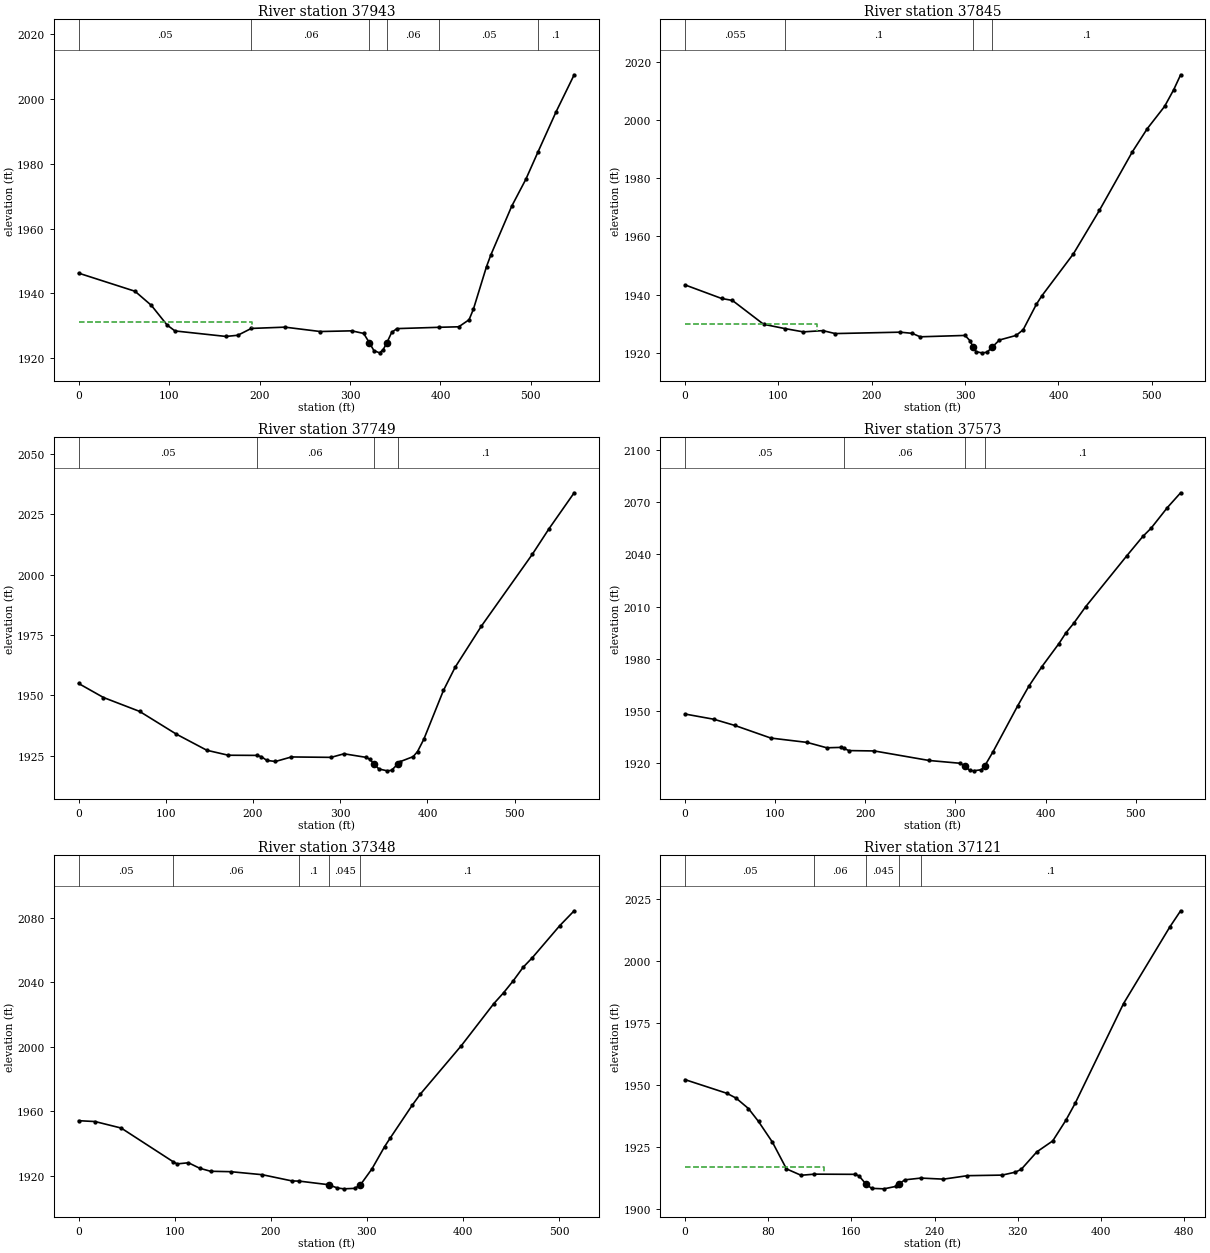
Type RM Length L Ch R = 1 ,37943   ,102.3,98.7,96.2
XS GIS Cut Line= 4
 2438844.6213734636434.3437714162439114.65111635636320.444969888
2439172.24039802636294.8497335892439330.93086307636187.349741136
#Sta/Elev= 30
       0 1946.25    62.3 1940.66    80.4  1936.3    97.8 1930.23   106.5 1928.41
   162.9 1926.71     176 1927.08  190.871929.182   228.1 1929.58   267.1 1928.23
   301.9 1928.44   315.1 1927.64   321.51924.722   326.4 1922.35   332.6 1921.65
   336.7 1922.66   340.61924.686   346.1 1927.98   351.9 1929.13  398.411929.533
   420.2 1929.69   431.6 1931.86   436.4 1935.12   450.9 1948.28   455.8 1951.95
   478.8 1966.94   494.4 1975.24   507.91983.724   527.8 1996.05   547.8 2007.48
#Mann= 6 ,-1 , 0
       0     .05       0  190.87     .06       0   321.5    .045       0
   340.6     .06       0  398.41     .05       0   507.9      .1       0
#XS Ineff= 2 , 0
           191.9 1931.25
Permanent Ineff=
       F       F
Bank Sta=321.5,340.6
XS Rating Curve= 0 ,0
Exp/Cntr(USF)=0,0
Exp/Cntr=0.3,0.1

Type RM Length L Ch R = 1 ,37845   ,98.1,95.7,94.1
XS GIS Cut Line= 4
2438976.55239597636579.0507483012439178.18045691636413.806698362
2439276.72048669636321.3306704142439370.71251509636224.306641092
#Sta/Elev= 30
       0 1943.35      39 1938.71    50.7 1938.02    84.1 1929.83   106.8 1928.36
   126.7 1927.22   147.6 1927.65   160.8 1926.64   230.4 1927.12   243.3 1926.72
   251.8 1925.53   299.9    1926   305.3 1924.16   308.4 1922.12   311.7 1920.44
   317.6 1920.02   323.4  1920.2   329.2 1922.03   336.7 1924.42   354.7 1926.01
   362.2 1927.96   376.3 1936.67   382.1 1939.56     416 1954.03   443.8 1968.93
   479.2  1989.1   495.2 1997.06   513.7 2004.68   523.5 2010.44   530.9 2015.55
#Mann= 4 ,-1 , 0
       0    .055       0   106.8      .1       0   308.4    .045       0
   329.2      .1       0
#XS Ineff= 2 , 0
          140.89 1929.96
Permanent Ineff=
       F       F
Bank Sta=308.4,329.2
XS Rating Curve= 0 ,0
Exp/Cntr(USF)=0,0
Exp/Cntr=0.3,0.1

Type RM Length L Ch R = 1 ,37749   ,177,175.9,175
XS GIS Cut Line= 4
2439094.17492731636714.6116088842439272.06181959636465.058054974
2439336.04991033636378.0342515592439423.07371375636251.337831882
#Sta/Elev= 30
       0 1954.88    28.5 1949.08    69.9 1943.33   112.1  1933.9     147 1927.24
   171.6 1925.18  204.231925.116   209.6 1924.58   215.8 1923.04   225.6 1922.59
     244 1924.47   289.5  1924.3   304.3 1925.78     330 1924.28     334 1923.43
   338.61921.578   344.3  1919.5   353.8 1918.72   358.8 1918.93     3661921.561
   368.7 1922.54   383.6  1924.6   388.6 1926.71   395.8  1931.8   418.3 1952.01
   431.7  1961.6   461.8 1978.63   520.2 2008.36   539.3 2018.93   568.2 2033.84
#Mann= 4 ,-1 , 0
       0     .05       0  204.23     .06       0   338.6    .045       0
     366      .1       0
#XS Ineff= 2 , 0
          304.45  1925.7
Permanent Ineff=
       F       F
Bank Sta=338.6,366
XS Rating Curve= 0 ,0
Exp/Cntr(USF)=0,0
Exp/Cntr=0.3,0.1

Type RM Length L Ch R = 1 ,37573   ,222.8,224.2,226.1
XS GIS Cut Line= 4
2439266.94277233636787.558032335  2439393.639192636607.111616431
2439474.26418634636480.4151967532439557.44870431636321.724731703
#Sta/Elev= 30
       0 1948.23    31.9 1945.24    55.3 1941.66    95.1 1934.43   135.3 1931.94
   157.2 1928.84   172.6 1929.06  176.271928.474   181.7 1927.23   209.9 1927.02
   270.7 1921.54   305.5 1919.92   310.41918.147   315.6 1915.98     320 1915.59
   328.6 1916.23   332.21918.188   341.8  1926.7   369.2 1953.14   381.4 1964.24
   395.8 1975.43   414.8 1988.76   422.5 1994.89   431.1 2000.35   444.6 2010.04
   489.8 2039.02   507.9 2050.34   516.9 2054.98   535.1 2066.92   549.8 2075.41
#Mann= 4 ,-1 , 0
       0     .05       0  176.27     .06       0   310.4    .045       0
   332.2      .1       0
Bank Sta=310.4,332.2
XS Rating Curve= 0 ,0
Exp/Cntr(USF)=0,0
Exp/Cntr=0.3,0.1

Type RM Length L Ch R = 1 ,37348   ,213.6,227,238.9
XS GIS Cut Line= 4
2439414.11538104636868.1830266752439553.60941887636740.206845183
2439638.07369865636645.504470878 2439762.2105947636489.373529458
#Sta/Elev= 30
       0 1954.25    17.1 1953.72    44.3 1949.68   98.031928.922   102.5 1927.46
   114.3 1928.15   125.9 1924.77   137.3 1922.88   158.3 1922.62   191.1 1920.75
   222.2 1916.87  229.431916.788   260.2 1914.54   269.1 1912.53     276 1911.98
   287.4 1912.28   293.31914.505   305.2 1924.32   318.5 1938.24   324.2 1943.43
     347 1963.72   355.5 1970.67   398.3 2000.81     432 2026.81   442.2 2033.57
   452.3 2041.02   462.6 2049.42   472.3 2055.44   500.7 2075.22   515.7 2084.45
#Mann= 5 ,-1 , 0
       0     .05       0   98.03     .06       0  229.43      .1       0
   260.2    .045       0   293.3      .1       0
Bank Sta=260.2,293.3
XS Rating Curve= 0 ,0
Exp/Cntr(USF)=0,0
Exp/Cntr=0.3,0.1

Type RM Length L Ch R = 1 ,37121   ,198.5,193.1,186.3
XS GIS Cut Line= 4
2439499.85942264636953.927068275 2439632.9546514636886.099692084
 2439702.0617894636880.9806448242439881.22844349 636695.41518166
#Sta/Elev= 30
       0  1952.1    40.1 1946.61      49 1944.67    60.9 1940.46    70.6 1935.23
      84 1926.88    97.5 1916.11   111.5 1913.53  124.371913.983   163.2 1913.91
   167.2  1913.3   173.61910.165   179.3 1908.26   191.3 1908.06   203.3  1909.1
   206.21910.152   211.3 1911.69  226.75  1912.4   248.5 1911.97   271.6 1913.37
     305  1913.6   317.6 1914.79   323.3 1915.93   338.3 1922.98   353.6  1927.4
   366.1 1935.64   375.1 1942.51   421.7 1982.81   466.2  2013.7   476.6 2020.22
#Mann= 5 ,-1 , 0
       0     .05       0  124.37     .06       0   173.6    .045       0
   206.2     .06       0  226.75      .1       0
#XS Ineff= 2 , 0
          133.32 1916.68
Permanent Ineff=
       F       F
Bank Sta=173.6,206.2
XS Rating Curve= 0 ,0
Exp/Cntr(USF)=0,0
Exp/Cntr=0.3,0.1

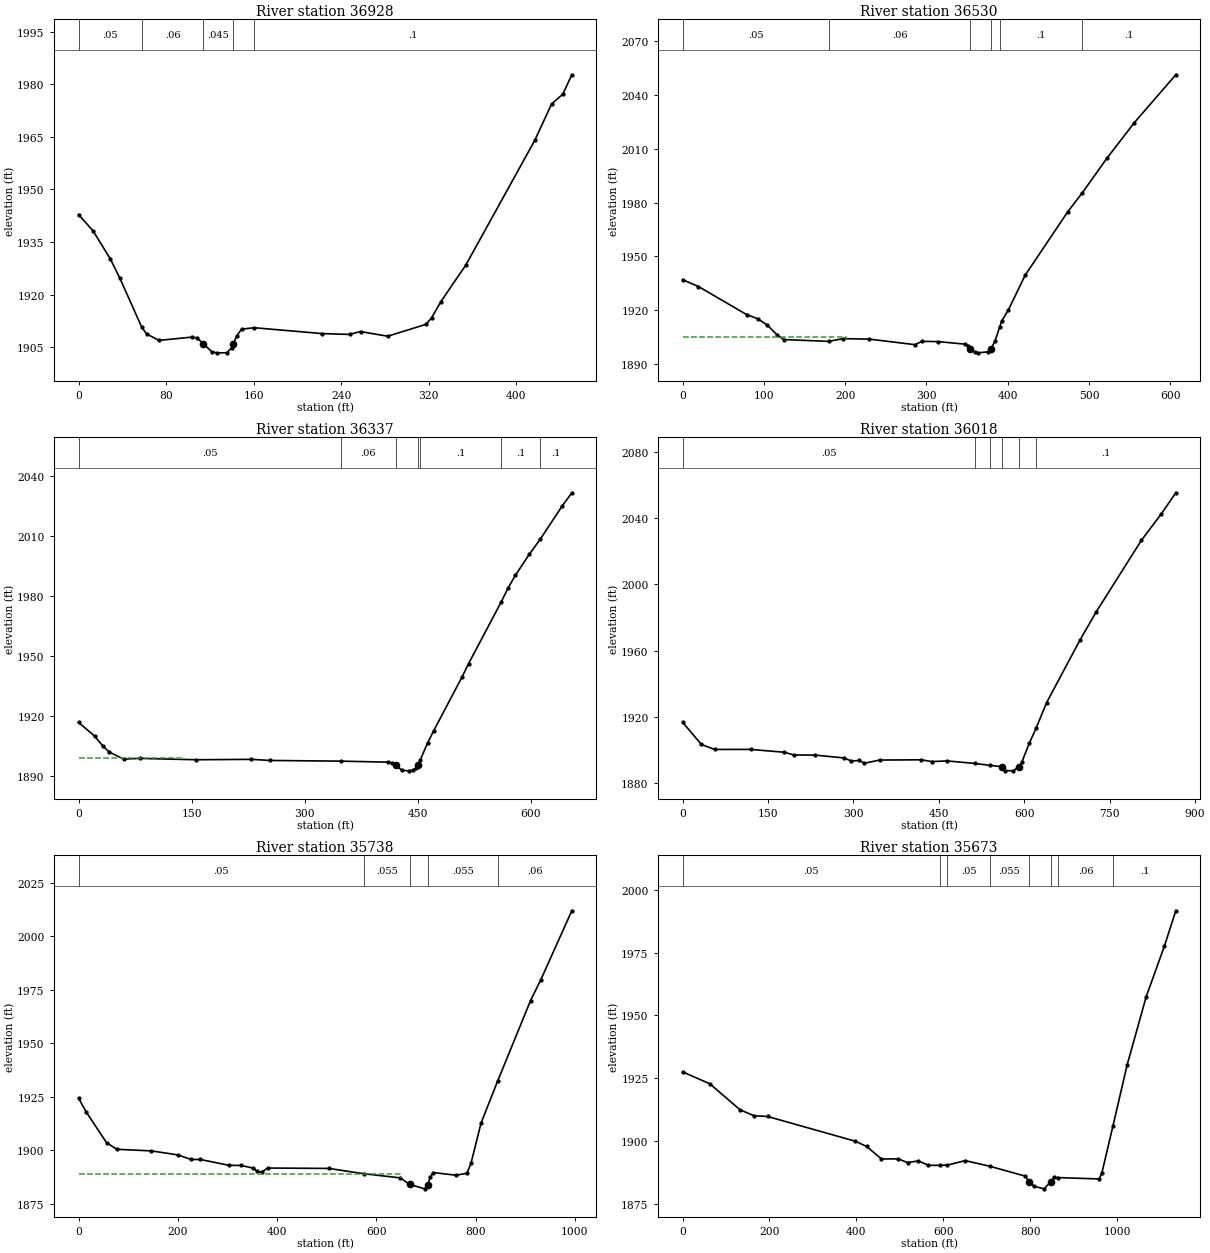
Type RM Length L Ch R = 1 ,36928   ,386.4,398,405.2
XS GIS Cut Line= 4
2439585.60346424637103.6592006212439681.58560036637085.742535212
2439737.89512022637055.0282516542439969.53200872636882.260406639
#Sta/Elev= 30
       0 1942.84    13.4 1938.15    29.1 1930.17    37.8 1924.69   57.761910.746
    62.2 1908.81    73.6 1906.98   103.5 1907.91   108.1 1907.72   114.11906.046
   121.7 1903.77   126.3 1903.43   135.4 1903.45     140 1904.88   141.5    1906
   144.5 1908.24   149.1 1910.18  160.671910.583   222.5 1908.92   247.7 1908.68
   257.7  1909.5   282.6 1908.16   317.5 1911.55   322.6 1913.37   331.1    1918
     354 1928.48   416.9 1963.95   432.3 1974.32   442.6 1977.15   450.8 1982.67
#Mann= 5 ,-1 , 0
       0     .05       0   57.76     .06       0   114.1    .045       0
   141.5     .06       0  160.67      .1       0
#XS Ineff= 2 , 0
                          161.67         1910.55
Permanent Ineff=
       F       F
Bank Sta=114.1,141.5
XS Rating Curve= 0 ,0
Exp/Cntr(USF)=0,0
Exp/Cntr=0.3,0.1

Type RM Length L Ch R = 1 ,36530   ,204.6,193.2,185.2
XS GIS Cut Line= 4
2439511.37727898637357.0520399762439833.87725634637403.123465313
2439920.90105975637424.8794161672440109.02604655637390.325847164
#Sta/Elev= 30
       0    1937    19.6 1933.18    78.8 1917.53    92.3 1915.24   104.4 1911.63
   116.5 1906.12   124.6 1903.58  179.741902.582   197.4 1904.09   229.7 1903.83
   286.2 1900.72   294.3 1902.58   314.5 1902.44   347.3 1901.03   351.4 1900.22
   354.2 1898.49   359.7 1896.42   363.8 1896.18   375.8 1896.76   379.51898.513
   384.4 1902.73  390.241910.853   392.6 1913.92   400.9 1920.24   421.4 1939.45
   473.7 1974.78  491.621985.393   521.8 2004.62   555.6 2024.52   606.7 2051.29
#Mann= 6 ,-1 , 0
       0     .05       0  179.74     .06       0   354.2    .045       0
   379.5     .06       0  390.24      .1       0  491.62      .1       0
#XS Ineff= 2 , 0
          201.02  1905.1
Permanent Ineff=
       F       F
Bank Sta=354.2,379.5
XS Rating Curve= 0 ,0
Exp/Cntr(USF)=0,0
Exp/Cntr=0.3,0.1

Type RM Length L Ch R = 1 ,36337   ,318.8,319.3,317.2
XS GIS Cut Line= 4
2439540.81180072637829.2841496832439817.24035274637646.278210149
2439945.21653424637575.8913103282440093.66890477637479.909174209
#Sta/Elev= 30
       0 1916.61    21.5 1909.69      32 1904.87    40.6 1901.79    59.9  1898.2
    81.1 1898.57   156.5 1897.89     229 1898.09   254.2 1897.54  347.711897.192
   410.8  1896.7   415.4 1896.38   420.91895.128   429.1  1892.6   438.2 1892.34
   444.1 1892.74   447.4 1893.67   449.8 1895.13  453.131897.531     463 1906.25
   471.3  1912.5   508.9  1939.4   517.5 1946.05  560.881976.985   569.9 1983.88
   579.4 1990.13     598 2000.73  612.452008.256   641.3  2024.7   654.4 2031.53
#Mann= 7 ,-1 , 0
       0     .05       0  347.71     .06       0   420.9    .045       0
   449.8     .06       0  453.13      .1       0  560.88      .1       0
  612.45      .1       0
#XS Ineff= 2 , 0
          139.32 1898.77
Permanent Ineff=
       F       F
Bank Sta=420.9,449.8
XS Rating Curve= 0 ,0
Exp/Cntr(USF)=0,0
Exp/Cntr=0.3,0.1

Type RM Length L Ch R = 1 ,36018   ,267.8,280.1,298.8
XS GIS Cut Line= 4
2439525.45465894638162.0222215632439995.12724502637909.909144023
2440068.07366847637862.5579568712440256.19865526 637703.86749182
#Sta/Elev= 30
       0 1916.84    33.2 1903.38    56.4 1900.38   119.5  1900.4   178.5 1898.69
   195.3 1897.06     233 1896.96   282.9 1895.28   296.6 1893.41   310.2 1893.71
   319.3 1892.06   345.9 1893.97   419.1 1894.14   437.5 1893.07   464.5 1893.45
  513.141891.938  539.311890.789   560.5 1890.04   566.8 1887.65   580.3 1887.47
   591.31890.045   595.7 1892.64   608.9 1904.12  621.081913.419   639.2 1928.57
   698.3 1966.64   726.7 1983.55   805.6 2026.51   840.3 2042.33   866.1 2055.24
#Mann= 6 ,-1 , 0
       0     .05       0  513.14    .055       0  539.31     .06       0
   560.5    .045       0   591.3     .06       0  621.08      .1       0
#XS Ineff= 2 , 0
           351.2 1893.83
Permanent Ineff=
       F       F
Bank Sta=560.5,591.3
XS Rating Curve= 0 ,0
Exp/Cntr(USF)=0,0
Exp/Cntr=0.5,0.3

Type RM Length L Ch R = 1 ,35738   ,50.1,65.2,70.4
XS GIS Cut Line= 4
2439531.82000512638204.7032573262440137.26910587638061.837097676
2440259.33888173638165.7946012772440462.86805623638109.039711294
#Sta/Elev= 30
       01924.327  15.335 1917.89  56.4331903.481  76.9831900.384  146.851899.623
 200.2781897.743 226.7271895.603 245.4871895.605 303.2071892.876 327.6841892.813
 352.3431891.542 359.7361890.073 368.7821889.668 381.1121891.603 504.4071891.422
 574.275 1888.95 648.3791886.996 666.888 1883.93 697.5711881.874 703.9041883.885
 708.0791887.188 714.6711889.484 760.6191888.238 782.4141889.155 790.7841893.952
 810.8661912.644 844.0871932.146 910.5291969.893 931.2921979.694 993.7092011.945
#Mann= 5 ,-1 , 0
       0     .05       0 574.275    .055       0 666.888    .045       0
 703.904    .055       0 844.087     .06       0
#XS Ineff= 2 , 0
          649.89 1888.78  714.89         1888.63
Permanent Ineff=
       F       F
Bank Sta=666.888,703.904
XS Rating Curve= 0 ,0
Exp/Cntr(USF)=0,0
Exp/Cntr=0.5,0.3

Type RM Length L Ch R = 1 ,35673   ,278.7,258.8,249
XS GIS Cut Line= 4
2439566.72009235638582.9248637422440139.15755217638114.148110935
2440264.70218621638245.4516731462440461.65752953638163.674893173
#Sta/Elev= 30
       0 1927.53    62.6  1922.8   132.6 1912.39   164.2 1910.06   195.8 1909.75
   397.8 1899.89   423.6  1897.8   457.7 1892.83   496.4 1892.86   517.7 1891.39
   542.9 1892.06   565.7 1890.29  591.56 1890.29  609.561890.391   650.3 1892.17
  706.371889.947   788.2 1886.01     7981883.639     808 1882.01   831.9 1880.93
   846.71883.641   855.1 1885.45  864.011885.406   958.7 1884.87   964.9 1887.36
  990.121905.881    1023 1930.39  1066.7 1957.45  1108.7 1977.68  1134.8 1991.69
#Mann= 8 ,-1 , 0
       0     .05       0  591.56     .06       0  609.56     .05       0
  706.37    .055       0     798    .045       0   846.7     .05       0
  864.01     .06       0  990.12      .1       0
Bank Sta=798,846.7
XS Rating Curve= 0 ,0
Exp/Cntr(USF)=0,0
Exp/Cntr=0.5,0.3

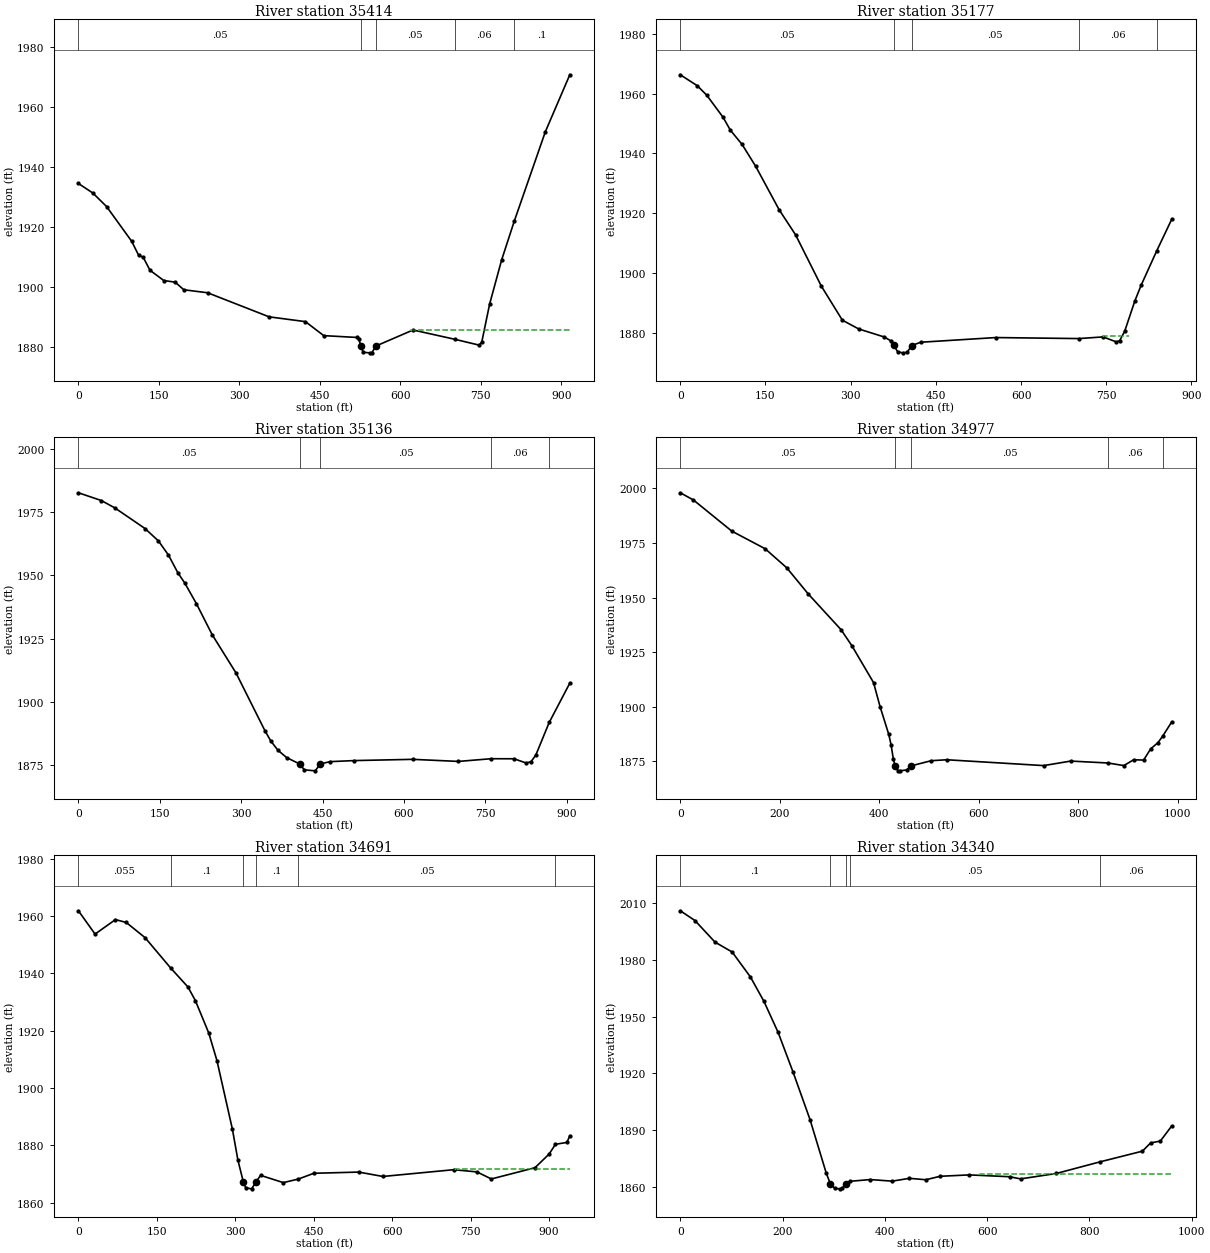
Type RM Length L Ch R = 1 ,35414   ,240.5,237.1,196.6
XS GIS Cut Line= 4
2439701.47901147638589.835577542 2440147.2200516638426.282017595
2440295.80039832638447.0141589972440531.91645317638276.549885249
#Sta/Elev= 30
       0 1934.47    26.9 1931.28    52.5 1926.77    99.3 1915.18   112.1 1910.56
   120.7 1909.87   133.4 1905.52   159.1 1902.09   180.3 1901.55   196.5 1899.01
   240.8 1898.01   355.5 1889.98   423.2 1888.38   457.3 1883.71   518.7 1883.11
   522.8 1882.57   526.61880.199   530.9 1878.13     543 1877.97     547 1877.98
   554.41880.232   623.8 1885.59   701.2 1882.51   746.9 1880.55   751.8 1881.47
   766.6 1894.27     789 1908.99  812.291921.787   870.5 1951.76     916 1970.73
#Mann= 5 ,-1 , 0
       0     .05       0   526.6    .045       0   554.4     .05       0
   701.2     .06       0  812.29      .1       0
#XS Ineff= 2 , 0
                          620.83         1885.74
Permanent Ineff=
       F       F
Bank Sta=526.6,554.4
XS Rating Curve= 0 ,0
Exp/Cntr(USF)=0,0
Exp/Cntr=0.5,0.3

Type RM Length L Ch R = 1 ,35177   ,41.7,41.2,43.8
XS GIS Cut Line= 4
2439793.62186214638752.2373518562440127.63969584638670.460571882
2440220.93433214638660.0945011822440590.65752047638445.862373363
#Sta/Elev= 30
       0 1966.27      30 1962.61    46.5 1959.47    75.3 1952.09    88.1 1947.79
   108.8 1943.02   132.9 1935.66   174.1  1921.2   202.9 1912.88   248.2 1895.77
   285.3 1884.37   314.1 1881.44   359.1 1878.76   371.2 1877.41   376.11875.927
   382.5 1873.86   391.3 1873.47   399.3 1873.59   407.3 1875.91   423.5 1877.01
   555.4 1878.57  701.89 1878.23   744.4 1878.79   767.8 1877.11   773.6 1877.53
   782.4 1880.69   800.4 1890.85   811.7 1896.18  839.021907.609   865.1    1918
#Mann= 5 ,-1 , 0
       0     .05       0   376.1    .045       0   407.3     .05       0
  701.89     .06       0  839.02      .1       0
#XS Ineff= 3 ,-1
       0     360 1876.86  421.25  701.38 1876.85  744.17  789.52  1879.1
Permanent Ineff=
       F       F       F
Bank Sta=376.1,407.3
XS Rating Curve= 0 ,0
Exp/Cntr(USF)=0,0
Exp/Cntr=0.5,0.3

Type RM Length L Ch R = 1 ,35136   ,163.6,158.9,147.8
XS GIS Cut Line= 4
2439787.86293397638846.6837737972440131.09505274638714.228425953
2440247.42540171638693.4962845512440606.78251934638476.960585466
#Sta/Elev= 30
       0 1982.63    42.3 1979.56      67 1976.67   122.7 1968.52   147.5  1963.6
     166 1958.02   183.2 1951.06     196    1947   217.5 1938.83   246.5  1926.6
   290.4  1911.5   343.8 1888.66   354.7 1884.57   367.9 1880.93   383.8 1878.06
   407.9 1875.54   416.3 1873.23   436.6 1872.84   445.41875.537   463.6 1876.47
   508.6 1876.89     616 1877.38   700.4 1876.56  760.611877.625   802.8  1877.6
   825.5 1875.91   834.2 1876.46     843 1879.07  867.621891.936   905.6 1907.45
#Mann= 5 ,-1 , 0
       0     .05       0   407.9    .045       0   445.4     .05       0
  760.61     .06       0  867.62      .1       0
Bank Sta=407.9,445.4
XS Rating Curve= 0 ,0
Exp/Cntr(USF)=0,0
Exp/Cntr=0.5,0.3

Type RM Length L Ch R = 1 ,34977   ,289.8,286,268.2
XS GIS Cut Line= 4
2439838.54150184639030.9694751462440217.47897524638866.264129566
2440391.39860589638777.5766357912440701.22894128 638558.73736544
#Sta/Elev= 30
       0 1997.99    26.4 1994.69   103.6 1980.42   170.5 1972.38   213.9 1963.66
   257.6 1951.56     323 1935.35   344.8    1928   388.4 1911.11   401.5 1900.12
   419.1 1887.33   423.6 1882.71   428.1 1876.28   431.61872.984   437.1  1870.8
   441.5 1870.69     455  1871.1     464 1872.97   504.4 1875.33   535.8 1875.76
   730.4 1873.09   784.9 1875.16   859.31874.286   891.6  1873.1   911.2 1875.75
   931.3 1875.62   945.5 1880.75     960 1883.56  969.83 1886.62   987.7 1893.06
#Mann= 5 ,-1 , 0
       0     .05       0   431.6    .045       0     464     .05       0
   859.3     .06       0  969.83      .1       0
Bank Sta=431.6,464
XS Rating Curve= 0 ,0
Exp/Cntr(USF)=0,0
Exp/Cntr=0.3,0.1

Type RM Length L Ch R = 1 ,34691   ,352,350.5,340.5
XS GIS Cut Line= 4
2440155.28255104639315.4605266042440355.69325126639132.326610888
2440423.64860363639060.9159016162440818.71107589638650.880216114
#Sta/Elev= 30
       0 1961.85    31.8 1953.71    70.8 1958.77    91.4 1957.77   127.4 1952.47
  176.111941.916   209.5 1935.22   223.7 1930.44   249.2 1919.16   264.8 1909.57
   294.5  1885.5   304.9 1874.79   315.4  1867.1   319.9 1865.12   331.2 1864.77
   339.5 1867.17   348.2 1869.48   391.8 1866.94  420.471868.188   450.1  1870.2
   535.9 1870.62   582.1 1869.09   717.3 1871.45   761.7 1870.69   789.5 1868.22
   872.8 1872.14   899.9 1876.91  911.961880.324   933.9 1880.98   939.4 1883.28
#Mann= 6 ,-1 , 0
       0    .055       0  176.11      .1       0   315.4    .045       0
   339.5      .1       0  420.47     .05       0  911.96     .06       0
#XS Ineff= 2 , 0
                          720.18         1871.76
Permanent Ineff=
       F       F
Bank Sta=315.4,339.5
XS Rating Curve= 0 ,0
Exp/Cntr(USF)=0,0
Exp/Cntr=0.3,0.1

Type RM Length L Ch R = 1 ,34340   ,377.3,376.2,367.6
XS GIS Cut Line= 4
  2440491.603956639525.0855118882440665.52358665 639314.30874097
2440801.43429139639123.1123258212440989.17534964638710.773069053
#Sta/Elev= 30
       0 2005.83    28.8 2000.65    67.8 1989.31   101.4 1984.06   136.9    1971
   163.6 1957.99   191.3 1941.63   220.7 1920.54   253.8 1895.51   285.2 1867.51
   293.31861.783     302 1859.24   311.8 1859.04   316.8 1859.35   323.8 1861.76
  331.311863.001   371.3 1863.94   414.3  1863.1     448 1864.59   480.3 1863.84
   508.1 1865.67   565.2  1866.4   644.3 1865.43   665.5 1864.29   735.5 1867.16
  821.451873.332   903.6 1878.92   919.7 1883.26   938.8 1884.27   960.9  1892.2
#Mann= 5 ,-1 , 0
       0      .1       0   293.3    .045       0   323.8      .1       0
  331.31     .05       0  821.45     .06       0
#XS Ineff= 2 , 0
                          586.21         1866.91
Permanent Ineff=
       F       F
Bank Sta=293.3,323.8
XS Rating Curve= 0 ,0
Exp/Cntr(USF)=0,0
Exp/Cntr=0.3,0.1

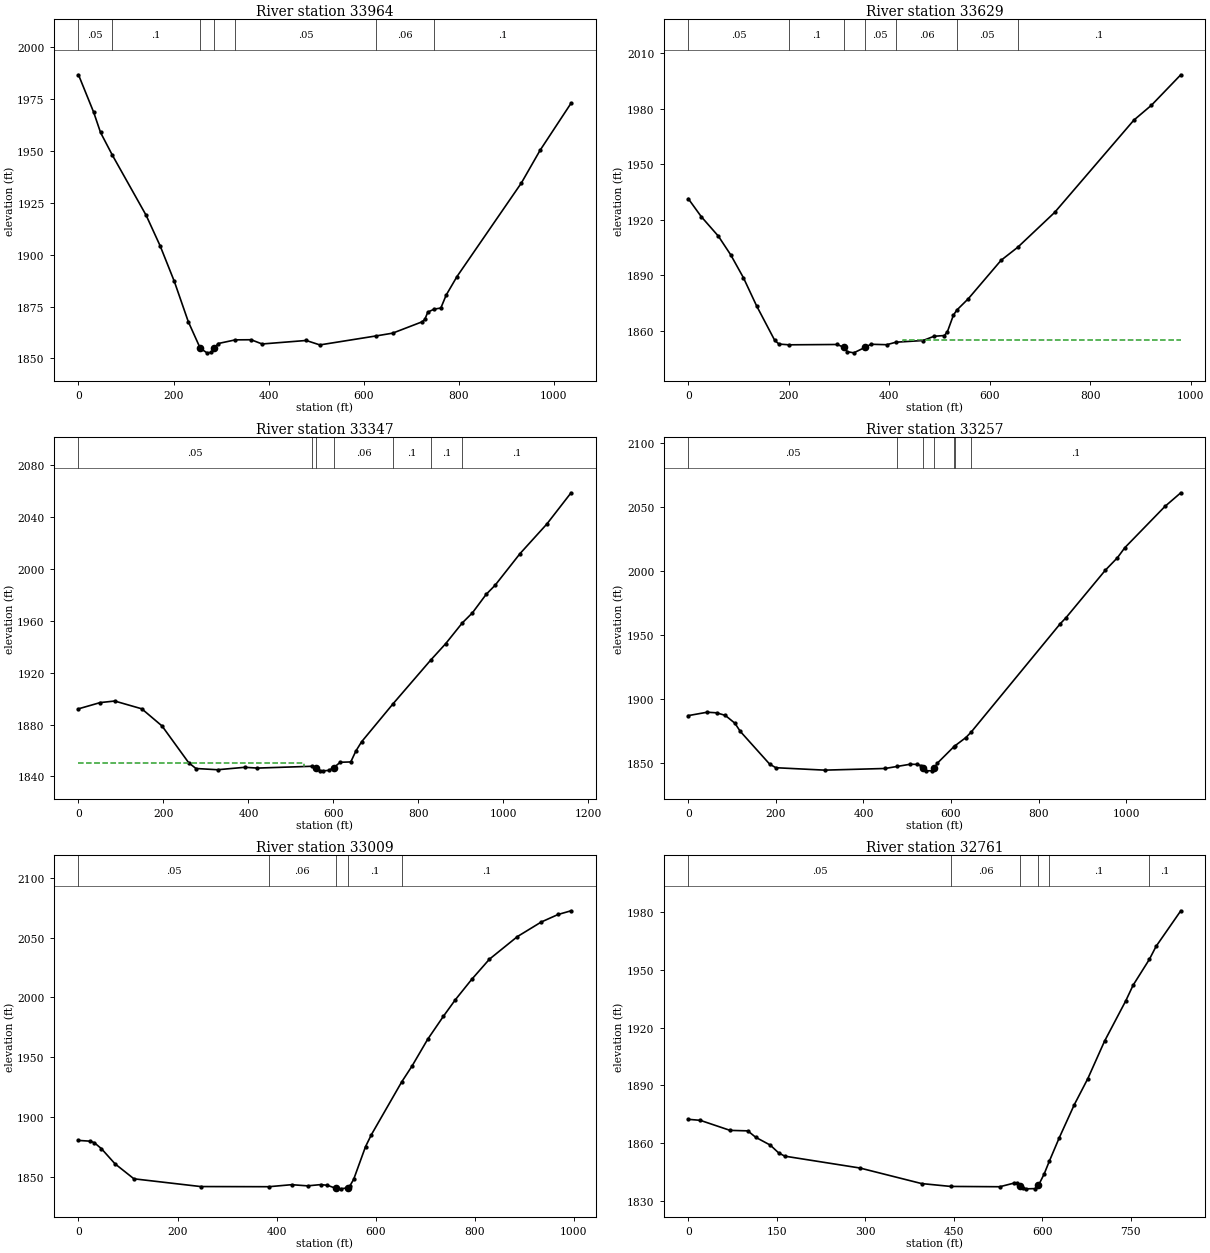
Type RM Length L Ch R = 1 ,33964   ,337.9,334.5,312.8
XS GIS Cut Line= 4
2440859.24318651639701.5251673452440984.05946229639513.510777251
2441187.87338096639165.9211485072441477.00475396638878.369728363
#Sta/Elev= 30
       0 1986.73      32 1968.64    46.4 1958.92   71.021948.101   142.4 1918.98
   171.8 1904.29   201.6 1887.17     231 1867.75   256.21854.925   270.3 1852.72
   279.7  1852.9   285.61854.883   294.2 1857.22  330.071858.975   363.2 1859.03
   386.4 1856.99   479.1 1858.68   507.8 1856.54  625.441860.842   660.9  1862.2
   723.3  1867.7   728.6 1868.81     735 1872.35  748.32 1873.78   762.4 1874.32
   773.7 1880.58   796.3 1889.46   931.7 1934.53   971.1  1950.3  1036.4 1973.03
#Mann= 7 ,-1 , 0
       0     .05       0   71.02      .1       0   256.2    .045       0
   285.6      .1       0  330.07     .05       0  625.44     .06       0
  748.32      .1       0
Bank Sta=256.2,285.6
XS Rating Curve= 0 ,0
Exp/Cntr(USF)=0,0
Exp/Cntr=0.3,0.1

Type RM Length L Ch R = 1 ,33629   ,289.1,282.7,270.9
XS GIS Cut Line= 4
2441127.83517239639802.6421502532441323.74932674639571.969032988
2441345.86866677 639513.510777252441630.63683924638968.108466849
#Sta/Elev= 30
       0 1931.45    25.9 1921.71    60.1 1911.11    84.8 1900.94   109.9 1888.65
   136.1 1873.44   172.2 1854.76   180.7 1852.76   200.5 1852.35     297 1852.53
   309.81850.899   316.6 1848.64   329.5 1848.01   351.51850.902   363.7 1852.65
   395.2 1852.41  413.461853.764   467.4 1854.67   489.3 1856.98     510 1857.37
     516 1859.51   527.8 1868.35  534.631871.138   557.5 1877.28   622.7 1898.07
  655.811905.098   729.4 1923.98     887 1973.89   922.1 1981.97   980.4 1998.42
#Mann= 7 ,-1 , 0
       0     .05       0   200.5      .1       0   309.8    .045       0
   351.5     .05       0  413.46     .06       0  534.63     .05       0
  655.81      .1       0
#XS Ineff= 2 , 0
                          427.24         1854.95
Permanent Ineff=
       F       F
Bank Sta=309.8,351.5
XS Rating Curve= 0 ,0
Exp/Cntr(USF)=0,0
Exp/Cntr=0.5,0.3

Type RM Length L Ch R = 1 ,33347   ,89,90,92.9
XS GIS Cut Line= 4
2441447.30350587 640191.025133522441612.24852905639732.026290938
2441580.30408457639613.2762909382441841.93602905639131.418652058
#Sta/Elev= 30
       0 1892.09    51.1  1896.9    85.2 1898.09   148.9  1892.1   196.7 1878.85
   259.4 1850.51   276.4 1846.11   327.4 1845.16   391.2 1847.04   420.9 1846.43
   549.5 1847.83   559.3 1846.42   567.6 1844.57   575.9 1844.31   588.3 1844.63
   600.5 1846.72   615.8 1850.91   640.7 1851.18   652.6 1859.53   666.1  1866.7
  740.631896.158  828.851929.678   863.8 1942.23     9031958.246     927 1966.09
   959.3 1980.31   980.1 1987.23  1038.8 2011.65    1102 2034.47    1159 2058.55
#Mann= 7 ,-1 , 0
       0     .05       0   549.5     .06       0   559.3    .045       0
   600.5     .06       0  740.63      .1       0  828.85      .1       0
     903      .1       0
#XS Ineff= 2 , 0
          529.96 1850.14     624            1850
Permanent Ineff=
       F       F
Bank Sta=559.3,600.5
XS Rating Curve= 0 ,0
Exp/Cntr(USF)=0,0
Exp/Cntr=0.5,0.3

Type RM Length L Ch R = 1 ,33257   ,238.6,248.1,258.3
XS GIS Cut Line= 4
2441519.01936239640195.6547631472441687.42214012639733.849207595
2441654.43602905639586.2797631472441883.60269567639162.668652043
#Sta/Elev= 30
       0  1886.7    43.4 1889.37    64.7  1888.9    84.6 1886.89   106.5 1880.78
   118.9 1874.36     186 1848.72   200.1 1845.94   311.6 1844.05   449.7 1845.35
  477.291846.963   506.9 1848.67   523.3 1848.55   531.5 1847.48   535.6 1845.66
   543.8  1843.5   556.1 1843.58  562.04 1845.73   568.5 1849.42  605.771862.157
   609.41863.198   633.9 1869.56     6461873.855   849.1 1958.55     862 1963.16
   952.4 2000.56   979.7 2010.22   996.7 2018.11  1088.2 2050.37  1124.4 2061.06
#Mann= 7 ,-1 , 0
       0     .05       0  477.29     .06       0   535.6    .045       0
  562.04     .06       0  605.77      .1       0   609.4     .06       0
     646      .1       0
Bank Sta=535.6,562.04
XS Rating Curve= 0 ,0
Exp/Cntr(USF)=0,0
Exp/Cntr=0.5,0.3

Type RM Length L Ch R = 1 ,33009   ,244.5,247.4,251
XS GIS Cut Line= 4
2441572.31797346640197.3908742822441836.90130681639853.640874267
2442059.81797346639576.5575409232442201.48464015639428.640874267
#Sta/Elev= 30
       0 1880.33    23.5 1879.71      32 1878.42    46.3 1873.44    73.8 1860.74
   111.9 1848.22   246.6 1841.74  384.351841.615   430.2  1843.3   462.3 1842.33
   488.7 1843.36   502.5  1842.8   519.31840.278   529.7 1839.83   543.7 1840.72
     548 1842.47   555.4 1847.75   579.3 1875.08   591.3 1885.24  652.491929.385
   673.2 1942.55   704.7  1964.9   736.6 1984.24   760.7 1998.08   793.6 2015.05
   829.4 2031.96     886 2050.91   934.1 2063.08   968.1 2069.38   994.2 2072.47
#Mann= 5 ,-1 , 0
       0     .05       0  384.35     .06       0   519.3    .045       0
   543.7      .1       0  652.49      .1       0
Bank Sta=519.3,543.7
XS Rating Curve= 0 ,0
Exp/Cntr(USF)=0,0
Exp/Cntr=0.3,0.1

Type RM Length L Ch R = 1 ,32761   ,286.7,288.9,287.6
XS GIS Cut Line= 4
2441557.58234972640287.6876776372442011.02881994639998.556304636
2442069.48707569639954.3176246142442243.28189006639813.701820258
#Sta/Elev= 30
       0 1872.49    20.4 1871.97    70.9 1866.77     101 1866.51   114.4 1863.18
     139 1859.15   153.2 1855.12   163.6 1853.42   290.8 1847.29   395.4 1839.23
  444.781837.745     528 1837.59   552.5 1839.51   557.3  1839.3   562.5 1838.05
   567.5 1836.73   572.5  1836.5   587.6 1836.62   593.41838.299     603 1844.11
  611.771850.746   628.6 1862.88   654.2 1880.08     677 1893.51   705.4 1912.94
   741.3 1933.79   753.8 1941.91  781.311955.282   792.8 1962.06   834.6 1980.45
#Mann= 6 ,-1 , 0
       0     .05       0  444.78     .06       0   562.5    .045       0
   593.4     .06       0  611.77      .1       0  781.31      .1       0
Bank Sta=562.5,593.4
XS Rating Curve= 0 ,0
Exp/Cntr(USF)=0,0
Exp/Cntr=0.3,0.1