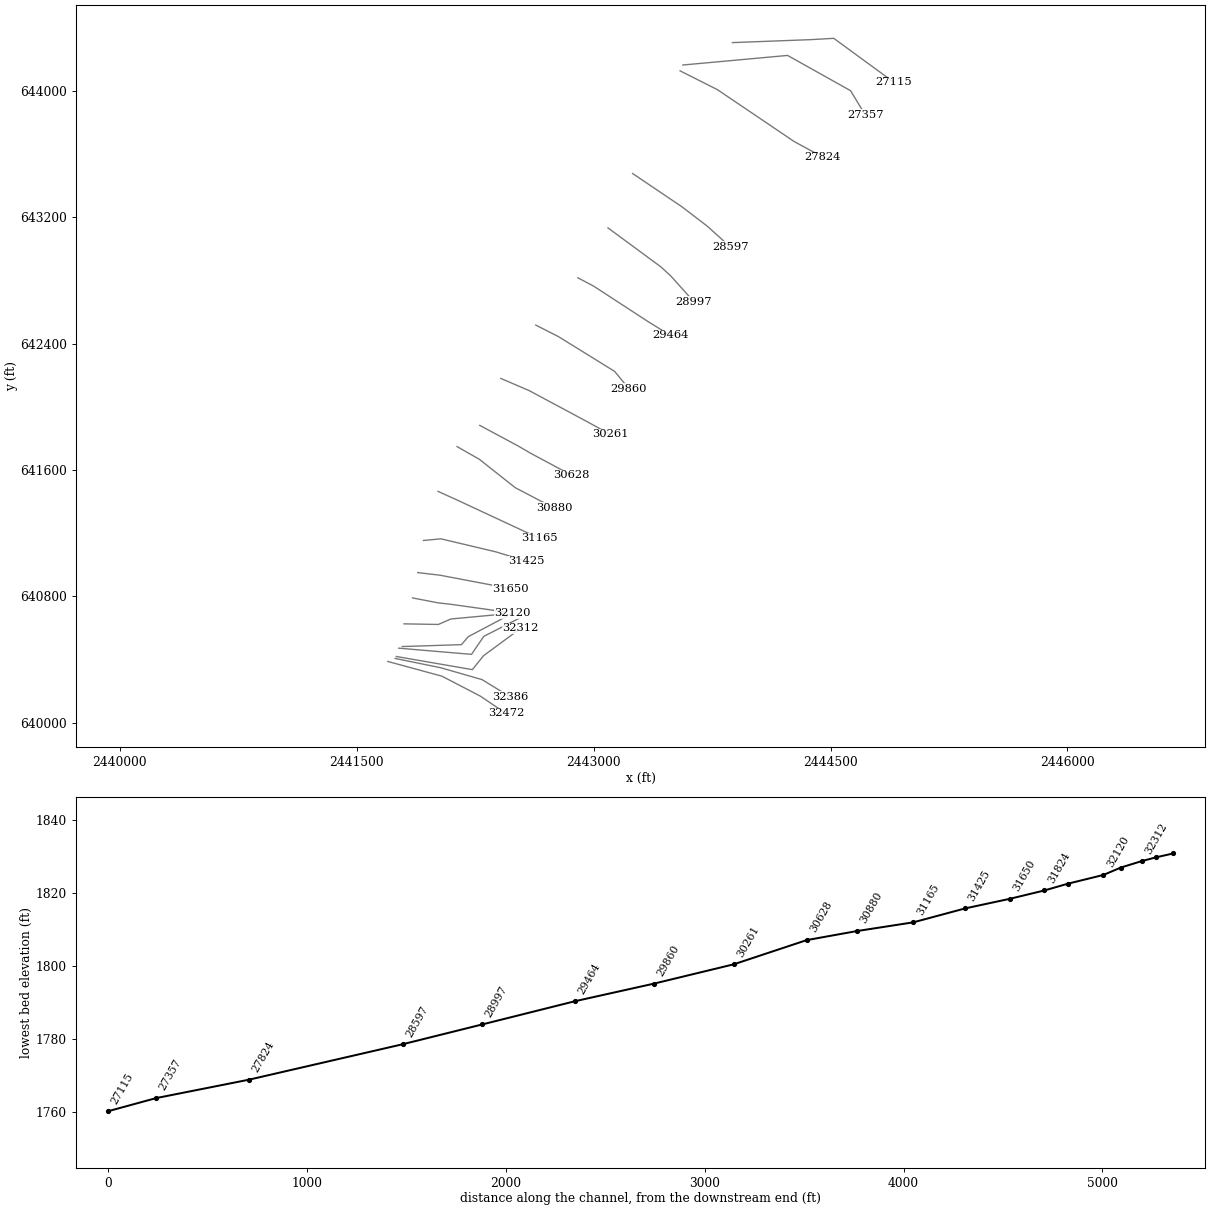
HEC-RAS study REEDSCK.prj: REEDSCK

--- REEDSCK.g01 (geometry) --- (continued)

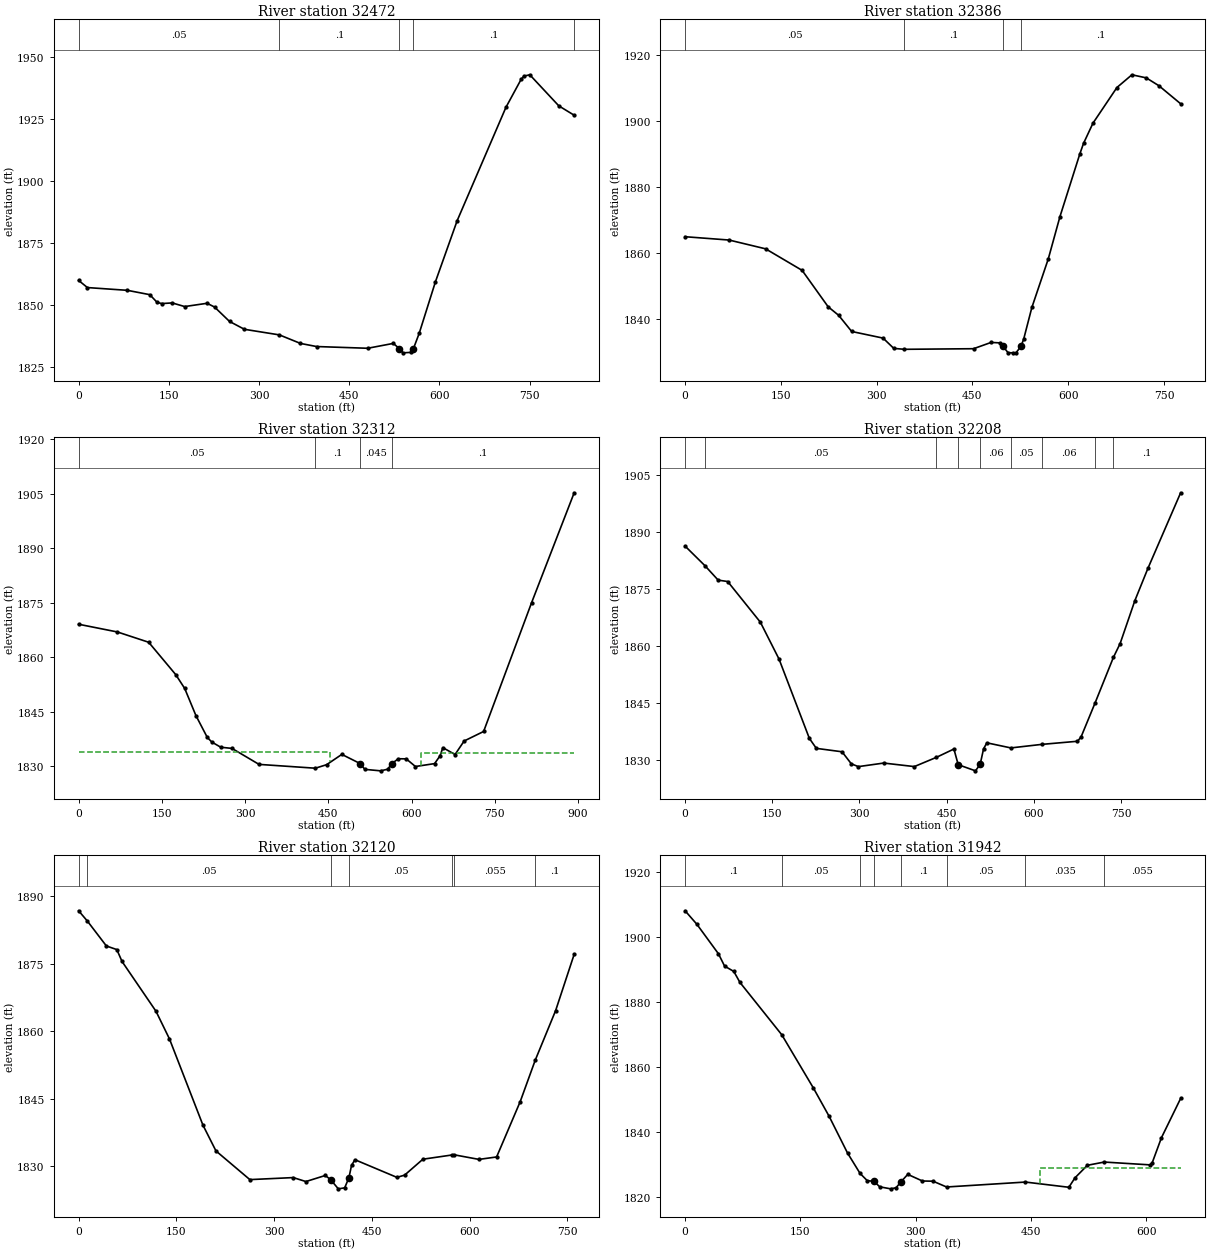
Type RM Length L Ch R = 1 ,32472   ,84.5,86.6,90.6
XS GIS Cut Line= 4
2441696.61820121640387.2247076872442039.46797139640294.007489069
2442282.78071151640167.6112604342442443.93590302640058.594513237
#Sta/Elev= 30
       0 1860.07    14.6 1857.19      81 1856.08   118.3 1854.33   130.7 1851.18
   138.5 1850.75   155.6 1851.01   176.3 1849.54   213.6 1850.86     226 1849.35
   250.9 1843.55   275.7 1840.38   333.8 1838.13   368.9 1834.69   395.6 1833.44
   480.7 1832.74   523.2  1834.7  533.34 1832.62   539.3  1830.9   552.8 1831.09
  556.77 1832.62   566.3 1838.75   593.4 1859.59   629.5 1884.18   710.6 1929.82
   735.7 1941.02   740.5 1942.36   750.2  1942.9   798.5 1930.37     824 1926.61
#Mann= 5 ,-1 , 0
       0     .05       0   333.8      .1       0  533.34    .045       0
  556.77      .1       0     824     .05       0
Bank Sta=533.34,556.77
XS Rating Curve= 0 ,0
Exp/Cntr(USF)=0,0
Exp/Cntr=0.3,0.1

Type RM Length L Ch R = 1 ,32386   ,63,73.7,112.3
XS GIS Cut Line= 4
 2441743.1686637640406.4587758592442033.01921542640347.171163006
2442293.88471198640272.0735200582442471.74755054640162.720811906
#Sta/Elev= 30
       0 1865.02      69 1864.01   126.1 1861.35   183.3 1854.82   224.1 1843.78
   240.5 1841.21   260.9 1836.31   310.1  1834.3   326.8 1831.19   343.4 1830.91
   451.7 1831.09   479.2 1832.99   493.3 1832.86   497.71831.875   505.8 1829.88
     514 1829.84   518.3 1829.87   525.9 1831.77   530.2 1833.94   543.1 1843.59
   568.8 1858.29   587.1 1871.12   618.2 1890.09     624 1893.29   638.8 1899.42
   676.3 1910.22   699.8 1914.08   722.3 1913.14   742.1 1910.76   776.1  1905.3
#Mann= 4 ,-1 , 0
       0     .05       0   343.4      .1       0   497.7    .045       0
   525.9      .1       0
Bank Sta=497.7,525.9
XS Rating Curve= 0 ,0
Exp/Cntr(USF)=0,0
Exp/Cntr=0.5,0.3

Type RM Length L Ch R = 1 ,32312   ,92.4,104.2,87.5
XS GIS Cut Line= 4
2441750.33659838640418.823764845  2442231.820219640335.524741947
 2442302.7241426640423.7981501872442537.45496157640596.378059091
#Sta/Elev= 30
       01869.091  69.9991866.964 126.2571864.139  174.97 1855.25 191.2071851.432
 211.5041843.949 231.8021838.001  239.921836.714 256.1581835.273 276.455 1834.95
 325.1681830.555 426.6541829.506 446.9511830.469 474.4111833.303 507.3371830.789
 515.8731829.187 544.3251828.781 557.1811829.231 564.241 1830.75 576.3431832.107
 590.4351832.076 607.0811829.974 641.6041830.768 651.5331832.938 656.4981835.161
 678.477 1833.27 694.8661836.986 729.9781839.606 816.4151875.003 893.2051905.244
#Mann= 4 ,-1 , 0
       0     .05       0 426.654      .1       0 507.337    .045       0
 564.241      .1       0
#XS Ineff= 2 , 0
          453.25 1833.86  616.59         1833.82
Permanent Ineff=
       F       F
Bank Sta=507.337,564.241
XS Rating Curve= 0 ,0
Exp/Cntr(USF)=0,0
Exp/Cntr=0.5,0.3

Type RM Length L Ch R = 1 ,32208   ,91,87.6,83.2
XS GIS Cut Line= 4
2441765.74903851640471.4466859012442226.62454188640432.262938652
2442304.05909001640546.0823949482442528.89916351640660.834797606
#Sta/Elev= 30
       0 1886.23   33.861881.116    56.9 1877.27    73.3  1876.9   129.5 1866.19
   161.6 1856.48   213.8 1835.58   225.8 1832.95     270 1832.05     286 1828.88
   298.1 1828.14   341.8 1829.08   394.4 1828.15  432.271830.577   462.5 1832.78
   469.9 1828.65   499.6 1827.03   507.7 1828.74   513.5 1832.82   519.2 1834.41
  560.471833.068  613.74    1834   675.1 1834.82   681.2 1835.93   705.4 1844.92
  736.891856.904   748.5 1860.57   773.9 1871.89   796.3 1880.37   852.6 1900.28
#Mann= 9 ,-1 , 0
       0      .1       0   33.86     .05       0  432.27     .06       0
   469.9    .045       0   507.7     .06       0  560.47     .05       0
  613.74     .06       0   705.4    .055       0  736.89      .1       0
Bank Sta=469.9,507.7
XS Rating Curve= 0 ,0
Exp/Cntr(USF)=0,0
Exp/Cntr=0.5,0.3

Type RM Length L Ch R = 1 ,32120   ,184.6,178.3,168
XS GIS Cut Line= 4
2441788.13975123640481.7090958952442163.18418919640493.837398615
2442206.09972189640544.2165022212442487.84952354640693.487920314
#Sta/Elev= 30
       0 1886.76   13.551884.451    42.6 1878.94    58.6 1878.14    66.6  1875.5
   118.7 1864.44   139.4 1858.29   190.7 1839.16   210.7 1833.42   262.7 1827.05
   329.3  1827.5   348.7 1826.62   378.5 1827.97   386.9    1827   398.4    1825
   408.2 1825.22   414.71827.475   418.7  1830.2   423.9 1831.47   488.3 1827.55
   500.1 1828.04   528.2 1831.58  572.671832.516  576.011832.563   614.2 1831.54
   641.3 1832.08   677.5 1844.37  700.571853.578   731.9 1864.61   760.3 1877.09
#Mann= 7 ,-1 , 0
       0      .1       0   13.55     .05       0   386.9    .045       0
   414.7     .05       0  572.67    .035       0  576.01    .055       0
  700.57      .1       0
#XS Ineff= 2 , 0
                          423.75         1831.43
Permanent Ineff=
       F       F
Bank Sta=386.9,414.7
XS Rating Curve= 0 ,0
Exp/Cntr(USF)=0,0
Exp/Cntr=0.3,0.1

Type RM Length L Ch R = 1 ,31942   ,125.8,118.2,95.9
XS GIS Cut Line= 4
2441799.33510758640625.3828358092442016.71161018640621.651050357
2442096.01205104640656.170065791 2442435.6045272640687.890242136
#Sta/Elev= 30
       0  1908.1    15.4 1903.93    43.4 1894.88    51.4 1891.09    63.4 1889.45
    71.4 1886.07  125.861869.972   167.1 1853.56   187.4 1844.94   211.4 1833.63
  227.761827.344   237.1 1825.13     2461824.913   253.3 1823.23   267.6 1822.61
   274.6 1822.94   280.6 1824.67   289.8 1827.06   308.9 1825.02   322.7 1824.96
  340.331823.179  442.941824.695   499.5 1823.09   507.5    1826   523.6 1829.85
  545.541830.845   605.2 1829.98   607.9 1830.56     620 1838.32     645  1850.4
#Mann= 8 ,-1 , 0
       0      .1       0  125.86     .05       0  227.76      .1       0
     246    .045       0   280.6      .1       0  340.33     .05       0
  442.94    .035       0  545.54    .055       0
#XS Ineff= 2 , 0
                          461.94         1829.04
Permanent Ineff=
       F       F
Bank Sta=246,280.6
XS Rating Curve= 0 ,0
Exp/Cntr(USF)=0,0
Exp/Cntr=0.3,0.1

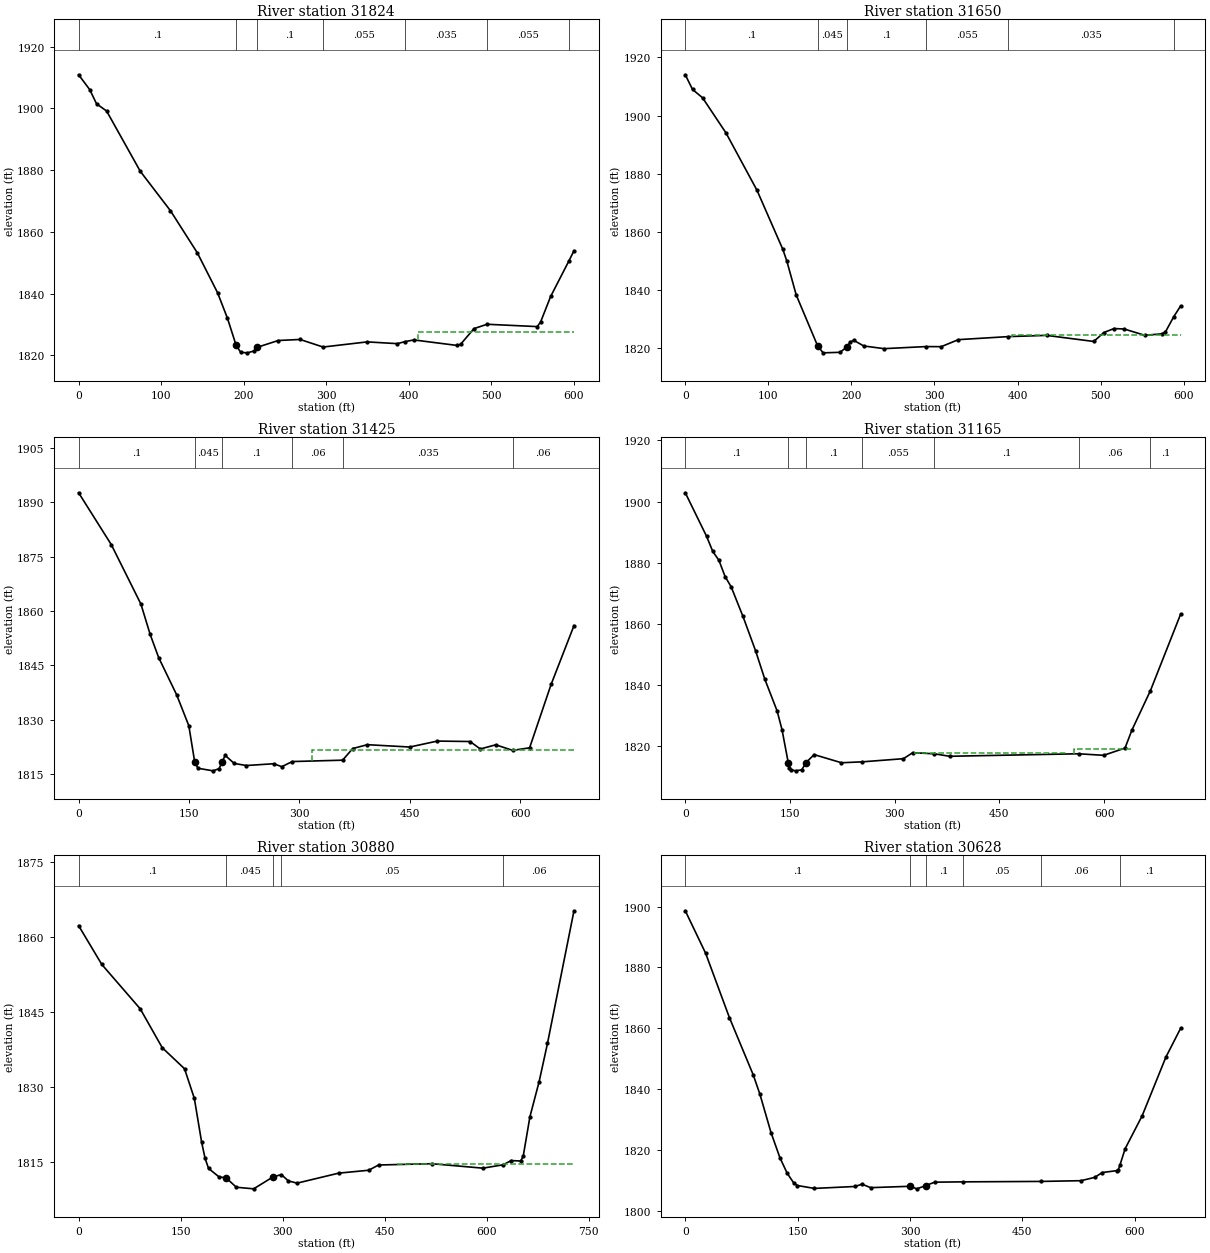
Type RM Length L Ch R = 1 ,31824   ,175.3,174,168.2
XS GIS Cut Line= 4
2441853.44599664640789.5813957112442017.64455654640757.861219367
2442087.61553378640750.3976484622442446.79988356640700.018544856
#Sta/Elev= 30
       0 1910.93    13.5  1906.1    21.7 1901.52    33.9 1899.18    74.7 1879.64
   111.3 1866.84   143.9 1853.17   168.3  1840.3   180.4 1831.95   190.91823.162
   196.5 1820.91   204.5 1820.76   212.6 1821.37   216.6 1822.57   241.9 1824.76
   268.3  1825.1  296.251822.642   349.7 1824.31   386.2 1823.74  395.591824.404
   406.4 1824.94   458.9 1823.15   463.1  1823.6   479.1 1828.61  494.931830.025
   555.8 1829.27   559.9  1830.8     572 1839.03  594.271850.629   600.3 1853.87
#Mann= 7 ,-1 , 0
       0      .1       0   190.9    .045       0   216.6      .1       0
  296.25    .055       0  395.59    .035       0  494.93    .055       0
  594.27      .1       0
#XS Ineff= 2 , 0
                          411.22         1827.55
Permanent Ineff=
       F       F
Bank Sta=190.9,216.6
XS Rating Curve= 0 ,0
Exp/Cntr(USF)=0,0
Exp/Cntr=0.3,0.1

Type RM Length L Ch R = 1 ,31650   ,225.5,224.7,225.2
XS GIS Cut Line= 4
2441886.09911935640950.0481701612442027.90696654640933.255135626
2442396.42077996640863.2841583952442472.92238173640845.558177496
#Sta/Elev= 30
       0 1914.04     8.7 1909.01    20.8 1906.13      49 1894.06    86.3 1874.36
   117.5    1854   122.3 1849.97   133.6 1838.33   159.51820.754     166 1818.47
   186.4 1818.65   194.5 1820.48   198.6 1822.19   202.7 1822.79   214.9 1820.83
   239.3 1819.91  289.691820.621   308.1 1820.59   328.9 1823.01  389.051824.051
   434.9 1824.47   491.8 1822.38     504 1825.46   516.2 1826.82   528.5 1826.66
   553.1  1824.5   573.7    1825   577.8 1825.49  587.881830.795   596.4 1834.59
#Mann= 6 ,-1 , 0
       0      .1       0   159.5    .045       0   194.5      .1       0
  289.69    .055       0  389.05    .035       0  587.88      .1       0
#XS Ineff= 2 , 0
                          392.86         1824.43
Permanent Ineff=
       F       F
Bank Sta=159.5,194.5
XS Rating Curve= 0 ,0
Exp/Cntr(USF)=0,0
Exp/Cntr=0.3,0.1

Type RM Length L Ch R = 1 ,31425   ,262.8,260.3,227.5
XS GIS Cut Line= 4
2441922.48402751641153.4304773122442033.50464472641163.692887306
2442379.62774542641081.5936073552442576.47942803641021.885040118
#Sta/Elev= 30
       0 1892.65    44.4 1878.32    84.6 1861.92    97.2 1853.51   108.7 1847.14
   133.1 1836.87   149.7  1828.3   157.71818.268   162.1 1816.55   182.7 1815.84
   190.9 1816.46     195 1818.38   199.1  1820.1   211.4 1817.88   227.9 1817.31
   264.9  1817.8     276 1816.99  290.161818.405  358.571818.786   372.4 1822.01
   392.3 1823.06   449.9 1822.42   487.2 1824.06   531.7 1823.94   545.7 1821.88
   566.6 1823.03  589.66 1821.49   612.6  1822.2   641.8  1839.7   672.9 1855.96
#Mann= 6 ,-1 , 0
       0      .1       0   157.7    .045       0     195      .1       0
  290.16     .06       0  358.57    .035       0  589.66     .06       0
#XS Ineff= 2 , 0
                          317.16         1821.65
Permanent Ineff=
       F       F
Bank Sta=157.7,195
XS Rating Curve= 0 ,0
Exp/Cntr(USF)=0,0
Exp/Cntr=0.3,0.1

Type RM Length L Ch R = 1 ,31165   ,287.6,284.7,238.6
XS GIS Cut Line= 4
2442014.84571746641464.101616218 2442132.3969592641410.923673522
2442558.75344713641212.2060981862442659.51165434641167.424672758
#Sta/Elev= 30
       0 1902.91    30.6 1888.64    39.4 1883.73    48.2 1880.84      57 1875.54
    65.7 1872.18    82.5 1862.58   100.6 1851.34     114 1841.95   131.6 1831.58
   138.6 1825.47   147.51814.728   149.3 1813.06   151.9 1812.35   158.1 1812.03
   166.9 1812.37     173 1814.74   184.6 1817.33   223.8 1814.67  253.87 1814.98
   312.5    1816   325.8 1817.95   356.6  1817.6   378.7 1816.79  563.491817.608
   599.4  1817.1     630 1819.47   639.8 1825.31  666.371838.226   709.7 1863.26
#Mann= 7 ,-1 , 0
       0      .1       0   147.5    .045       0     173      .1       0
  253.87    .055       0   356.6      .1       0  563.49     .06       0
  666.37      .1       0
#XS Ineff= 2 ,-1
  328.11  547.281817.792  557.41  638.46 1819.03
Permanent Ineff=
       F       F
Bank Sta=147.5,173
XS Rating Curve= 0 ,0
Exp/Cntr(USF)=0,0
Exp/Cntr=0.3,0.1

Type RM Length L Ch R = 1 ,30880   ,263,251.6,230.8
XS GIS Cut Line= 4
2442135.19579829641747.7173105942442276.07069912641667.483923369
2442503.70961171641487.4252752952442748.14155884641359.611623553
#Sta/Elev= 30
       0  1862.3      34 1854.55    90.6 1845.65   122.9 1837.88   155.7 1833.66
   170.1 1827.73   180.8 1818.98   185.9 1815.73     191 1813.72   206.3 1812.03
   216.9 1811.82   231.8 1809.95   257.3 1809.63   285.6    1812  298.021812.485
   308.3 1811.22   321.1 1810.77   382.3 1812.77   426.4 1813.35   440.9  1814.4
     519 1814.66   594.3 1813.77  624.281814.447   635.8 1815.29   649.9  1815.2
   653.6 1816.18   663.4 1824.04     677 1831.11   689.2 1838.72   728.2 1865.28
#Mann= 5 ,-1 , 0
       0      .1       0   216.9    .045       0   285.6      .1       0
  298.02     .05       0  624.28     .06       0
#XS Ineff= 2 , 0
                          469.62         1814.62
Permanent Ineff=
       F       F
Bank Sta=216.9,285.6
XS Rating Curve= 0 ,0
Exp/Cntr(USF)=0,0
Exp/Cntr=0.3,0.1

Type RM Length L Ch R = 1 ,30628   ,371.3,367,345.2
XS GIS Cut Line= 4
2442278.86953821641882.0615868772442520.50264625641752.382042409
2442600.73603347641705.7347242552442860.09512241641566.725716156
#Sta/Elev= 30
       0 1898.61    27.1 1884.67    58.9 1863.48    90.7 1844.65    99.7 1838.22
   114.5 1825.62   126.3 1817.42     136  1812.3   145.1 1808.98   149.7 1808.25
   172.4  1807.3   226.8 1807.94   235.9  1808.7   247.4 1807.55     300    1808
   309.1 1807.16   320.9 1808.22   332.9 1809.35  370.191809.457  475.221809.598
   528.2 1809.84   546.3 1810.91   556.8 1812.53   576.3 1813.15   578.1 1813.46
  580.241814.958   587.2 1820.36   609.9 1831.18   641.6 1850.48   661.3 1859.97
#Mann= 6 ,-1 , 0
       0      .1       0     300    .045       0   320.9      .1       0
  370.19     .05       0  475.22     .06       0  580.24      .1       0
Bank Sta=300,320.9
XS Rating Curve= 0 ,0
Exp/Cntr(USF)=0,0
Exp/Cntr=0.3,0.1

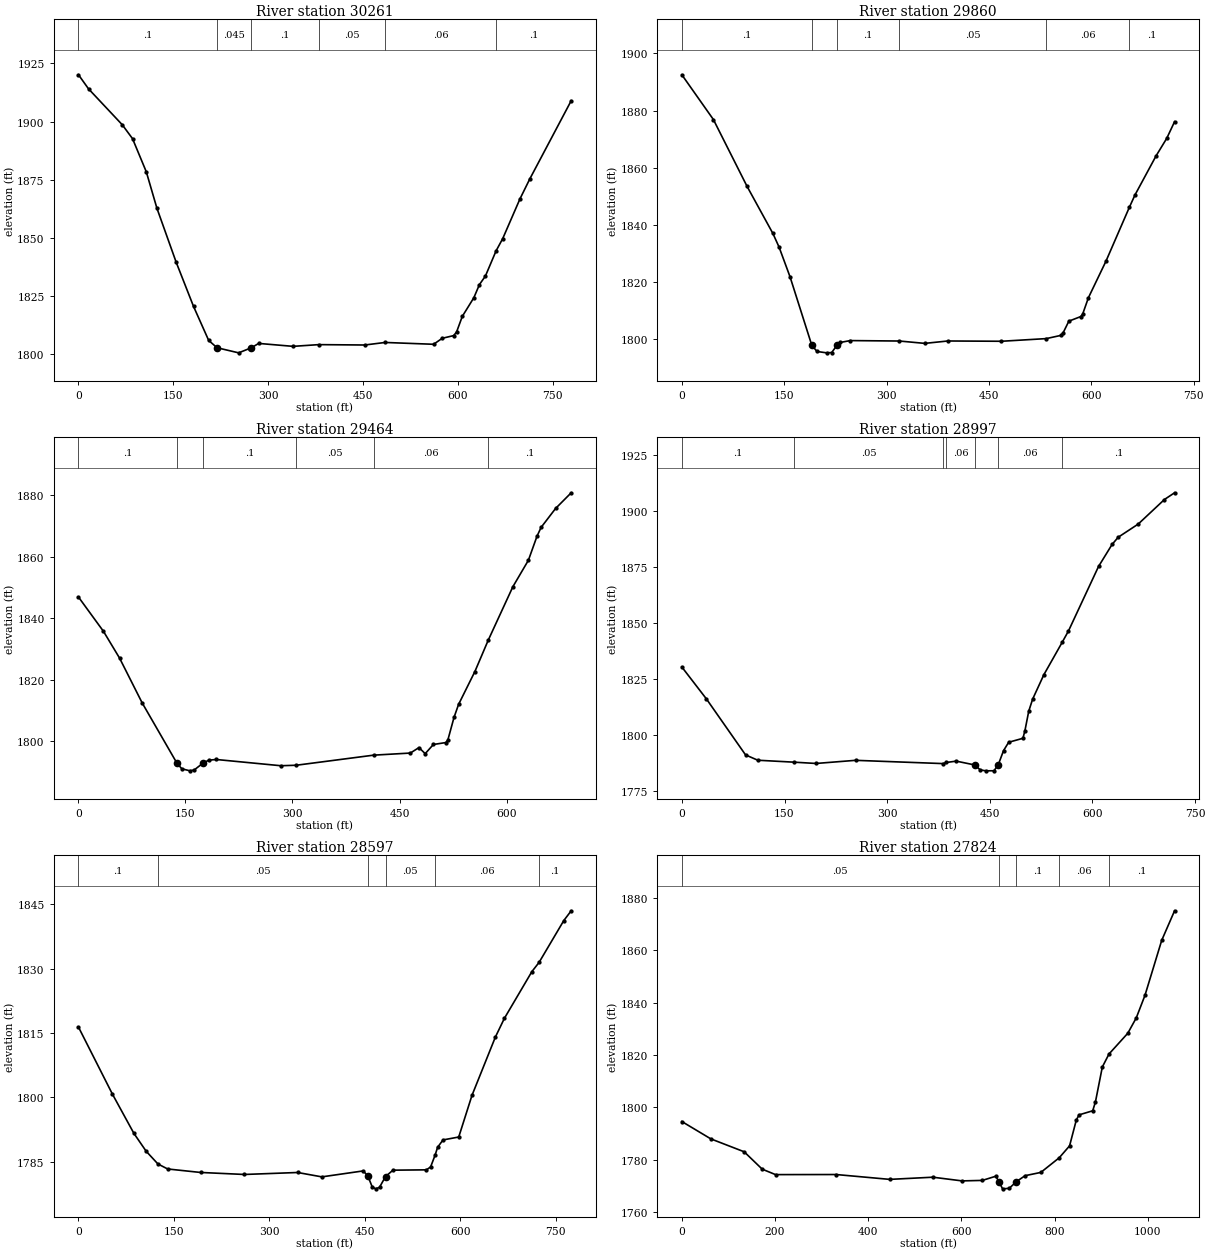
Type RM Length L Ch R = 1 ,30261   ,399.5,401.2,376
XS GIS Cut Line= 4
 2442412.1317481642179.2788149322442591.29840219642102.493106037
2442949.63171037641910.5288337982443105.76265179641824.784792198
#Sta/Elev= 30
       0 1920.12    15.9 1914.06    69.3 1898.61    85.5 1892.65   107.3 1878.38
   124.1 1862.71   154.6 1839.47     182 1820.51     206 1805.87   219.21802.723
   253.4 1800.53   273.51802.715   285.1 1804.58   339.5 1803.32  380.09 1804.06
     453  1803.9  485.111804.994   561.9 1804.21   575.5 1806.79   593.6 1807.94
   598.2 1809.48   607.3 1816.22   625.6 1824.26   634.4  1829.9   643.8 1833.53
   660.81844.432   671.2 1849.64   698.5 1866.73   713.9 1875.23   779.6 1908.97
#Mann= 6 ,-1 , 0
       0      .1       0   219.2    .045       0   273.5      .1       0
  380.09     .05       0  485.11     .06       0   660.8      .1       0
Bank Sta=219.2,273.5
XS Rating Curve= 0 ,0
Exp/Cntr(USF)=0,0
Exp/Cntr=0.3,0.1

Type RM Length L Ch R = 1 ,29860   ,395,396.7,386.6
XS GIS Cut Line= 4
2442633.53054209642517.1359340722442776.86386536642444.189510621
2443132.63764991642224.0704784552443223.50073877642114.010962371
#Sta/Elev= 30
       0 1892.55    46.2 1876.89    95.6 1853.47   133.4 1837.01   142.4 1832.27
   158.5 1821.85   190.41797.879     198 1795.72     212 1795.24   219.5 1795.35
   227.31797.868   231.7 1798.86   246.9 1799.53  318.831799.374   355.9 1798.55
   389.8 1799.39   468.3 1799.29  533.881800.221   555.4 1801.35   558.3 1802.09
     567 1806.33   584.4 1807.93   587.2 1808.76   595.7 1814.55   621.3 1827.27
  655.631846.156   663.9 1850.49   694.8 1864.17   710.4 1870.29   721.9 1876.13
#Mann= 6 ,-1 , 0
       0      .1       0   190.4    .045       0   227.3      .1       0
  318.83     .05       0  533.88     .06       0  655.63      .1       0
Bank Sta=190.4,227.3
XS Rating Curve= 0 ,0
Exp/Cntr(USF)=0,0
Exp/Cntr=0.3,0.1

Type RM Length L Ch R = 1 ,29464   ,465.8,466.4,357.7
XS GIS Cut Line= 4
2442899.72099959642816.6001987642442999.54242115642764.129964352
2443345.07811118642538.8918849262443485.85191083642451.868081511
#Sta/Elev= 30
       0 1846.92      35 1835.78    57.6 1827.07    89.3  1812.5   138.2 1792.84
   144.9 1791.09   156.4 1790.43   162.2 1790.71   173.9 1792.83   182.5 1793.89
     193 1794.12   283.7 1792.09  305.231792.249  413.851795.531   465.2 1796.21
   477.3 1797.99     486 1796.01   497.5    1799   514.9 1799.62   517.8 1800.47
   526.4 1807.78   532.8 1812.02   555.7 1822.72  574.391832.904   608.9 1850.27
   630.7 1858.89   642.7 1866.67   648.5 1869.57   668.8 1875.72   690.7 1880.82
#Mann= 6 ,-1 , 0
       0      .1       0   138.2    .045       0   173.9      .1       0
  305.23     .05       0  413.85     .06       0  574.39      .1       0
Bank Sta=138.2,173.9
XS Rating Curve= 0 ,0
Exp/Cntr(USF)=0,0
Exp/Cntr=0.3,0.1

Type RM Length L Ch R = 1 ,28997   ,394.6,399.7,399
XS GIS Cut Line= 4
2443090.40551001643132.7013670512443425.70310552 642885.70733677
2443488.41143446642828.1180550992443634.30428136642665.588304603
#Sta/Elev= 30
       0  1830.4    35.9 1816.16    93.1 1791.18     111  1788.8  163.281787.948
   196.1 1787.36   253.8 1788.76  381.991787.298  386.541787.804     401  1788.4
   427.81786.711   436.2 1784.46   444.7 1784.07   456.1 1784.11   462.31786.733
   470.1 1793.11   477.6 1796.82   498.4 1798.59   501.3 1801.93   506.9 1810.69
   512.6 1816.07     529 1826.96  555.821841.445     565 1846.51   608.9 1875.26
   628.7 1885.09   637.6  1888.3   666.8 1894.16   705.2 1905.14     720 1908.14
#Mann= 7 ,-1 , 0
       0      .1       0  163.28     .05       0  381.99      .1       0
  386.54     .06       0   427.8    .045       0   462.3     .06       0
  555.82      .1       0
Bank Sta=427.8,462.3
XS Rating Curve= 0 ,0
Exp/Cntr(USF)=0,0
Exp/Cntr=0.3,0.1

Type RM Length L Ch R = 1 ,28597   ,771.8,773.3,773.1
XS GIS Cut Line= 4
2443246.53645144643476.9572952652443561.35785791643264.516833988
2443720.04832296 643142.939461572443864.66140804643012.403756448
#Sta/Elev= 30
       0 1816.35    53.3 1800.74    87.1 1791.58   106.4 1787.41  124.871784.448
   140.2 1783.28   191.8 1782.47   260.8    1782   344.5 1782.46   382.5 1781.44
   447.6 1782.83   454.8 1781.65   461.8 1779.07   467.2 1778.65   473.2 1779.01
   482.61781.511   494.3    1783   546.9 1783.08   553.5 1783.76  560.551786.505
   564.5 1788.34     573 1790.05   597.7 1790.73   618.5 1800.43   655.3 1814.03
   669.4 1818.38   712.7 1829.29  724.081831.457   762.9  1841.2   774.5 1843.47
#Mann= 6 ,-1 , 0
       0      .1       0  124.87     .05       0   454.8    .045       0
   482.6     .05       0  560.55     .06       0  724.08      .1       0
Bank Sta=454.8,482.6
XS Rating Curve= 0 ,0
Exp/Cntr(USF)=0,0
Exp/Cntr=0.3,0.1

Type RM Length L Ch R = 1 ,27824   ,464.8,467.3,465.1
XS GIS Cut Line= 4
2443547.24679829644127.0542992742443783.48117622644007.853466371
2444271.12094719643678.4257099852444451.00584048643580.897755792
#Sta/Elev= 30
       0 1794.63    62.3    1788   133.8 1783.08   172.5 1776.45   201.1 1774.37
   331.3  1774.4   446.3 1772.55   538.9 1773.38   601.6 1771.97   645.1 1772.16
     674 1773.76   680.51771.705   688.5 1768.94   702.7 1769.13   718.21771.696
   736.8 1773.96   770.6 1775.21  810.061780.789   832.3 1785.34   846.7 1795.16
   852.6 1797.17     882 1798.73   887.9 1802.18   902.6 1815.43  916.931820.399
   957.3 1828.32   975.5 1834.19   994.1 1842.76  1030.1 1863.78  1057.7 1875.06
#Mann= 5 ,-1 , 0
       0     .05       0   680.5    .045       0   718.2      .1       0
  810.06     .06       0  916.93      .1       0
Bank Sta=680.5,718.2
XS Rating Curve= 0 ,0
Exp/Cntr(USF)=0,0
Exp/Cntr=0.3,0.1

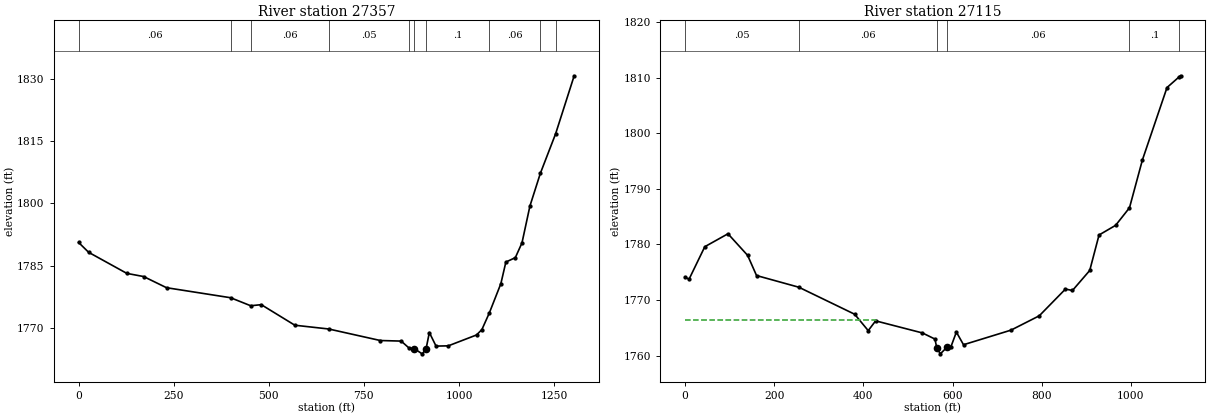
Type RM Length L Ch R = 1 ,27357   ,229.9,241.4,230.7
XS GIS Cut Line= 4
2443564.58510126644163.8981930812444227.77518977644224.582253468
2444626.55615803644001.3516027592444719.74953648 643847.47416392
#Sta/Elev= 30
       0 1790.63    26.3 1788.27   126.7 1783.21   170.9 1782.45   231.1 1779.77
   399.61777.362  452.421775.436   480.2  1775.7   568.5 1770.76  657.531769.857
   793.1 1767.09   848.1 1766.95  868.691765.284   882.3 1765.15   903.2 1763.89
   913.3 1764.99   922.1 1769.01   939.7 1765.75   971.9 1765.81  1046.1 1768.42
  1060.3 1769.72 1080.11 1773.77  1110.2 1780.76  1123.3 1785.93  1148.2 1786.99
  1165.7 1790.54  1186.6  1799.4 1214.051807.251 1254.091816.725  1302.9 1830.66
#Mann= 10 ,-1 , 0
       0     .06       0   399.6     .05       0  452.42     .06       0
  657.53     .05       0  868.69      .1       0   882.3    .045       0
   913.3      .1       0 1080.11     .06       0 1214.05      .1       0
 1254.09      .1       0
Bank Sta=882.3,913.3
XS Rating Curve= 0 ,0
Exp/Cntr(USF)=0,0
Exp/Cntr=0.5,0.3

Type RM Length L Ch R = 1 ,27115   ,64.3,62.7,70
XS GIS Cut Line= 4
2443878.56797346644305.7242075952444372.31797346 644324.47420761
2444520.23464012644332.8075409232444899.40130681 644055.72420761
#Sta/Elev= 30
       0 1774.06       9 1773.76    44.2 1779.59    96.2 1781.92   140.3 1778.03
   160.3  1774.4  255.231772.295   380.5 1767.43   410.9 1764.48   427.5 1766.24
   532.6 1764.06   560.6 1762.96   564.6 1761.41   572.7  1760.3   587.5 1761.48
   596.7 1761.62   608.7 1764.22   624.7 1761.94   731.3 1764.57   794.7 1767.15
   853.4 1771.96   869.2 1771.71   907.9 1775.31   928.8  1781.7     966 1783.44
  997.151786.604  1026.1 1795.21  1081.3 1808.25 1108.571810.177  1111.9 1810.37
#Mann= 6 ,-1 , 0
       0     .05       0  255.23     .06       0   564.6    .045       0
   587.5     .06       0  997.15      .1       0 1108.57     .12       0
#XS Ineff= 2 , 0
          427.36 1766.33     615         1761.88
Permanent Ineff=
       F       F
Bank Sta=564.6,587.5
XS Rating Curve= 0 ,0
Exp/Cntr(USF)=0,0
Exp/Cntr=0.5,0.3