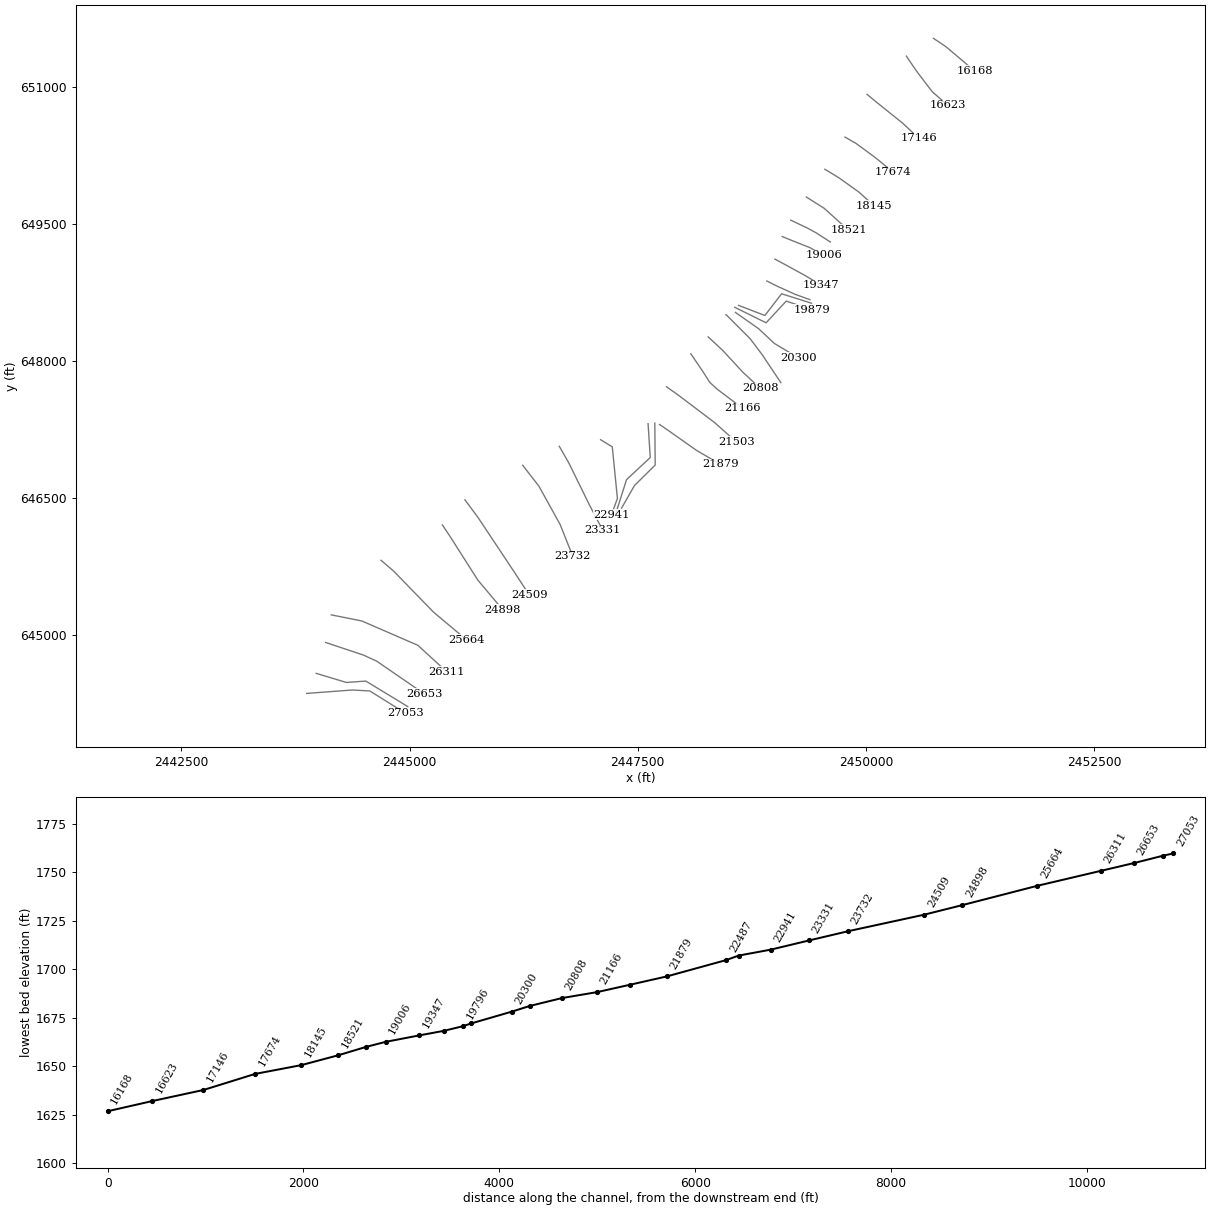
HEC-RAS study REEDSCK.prj: REEDSCK

--- REEDSCK.g01 (geometry) --- (continued)

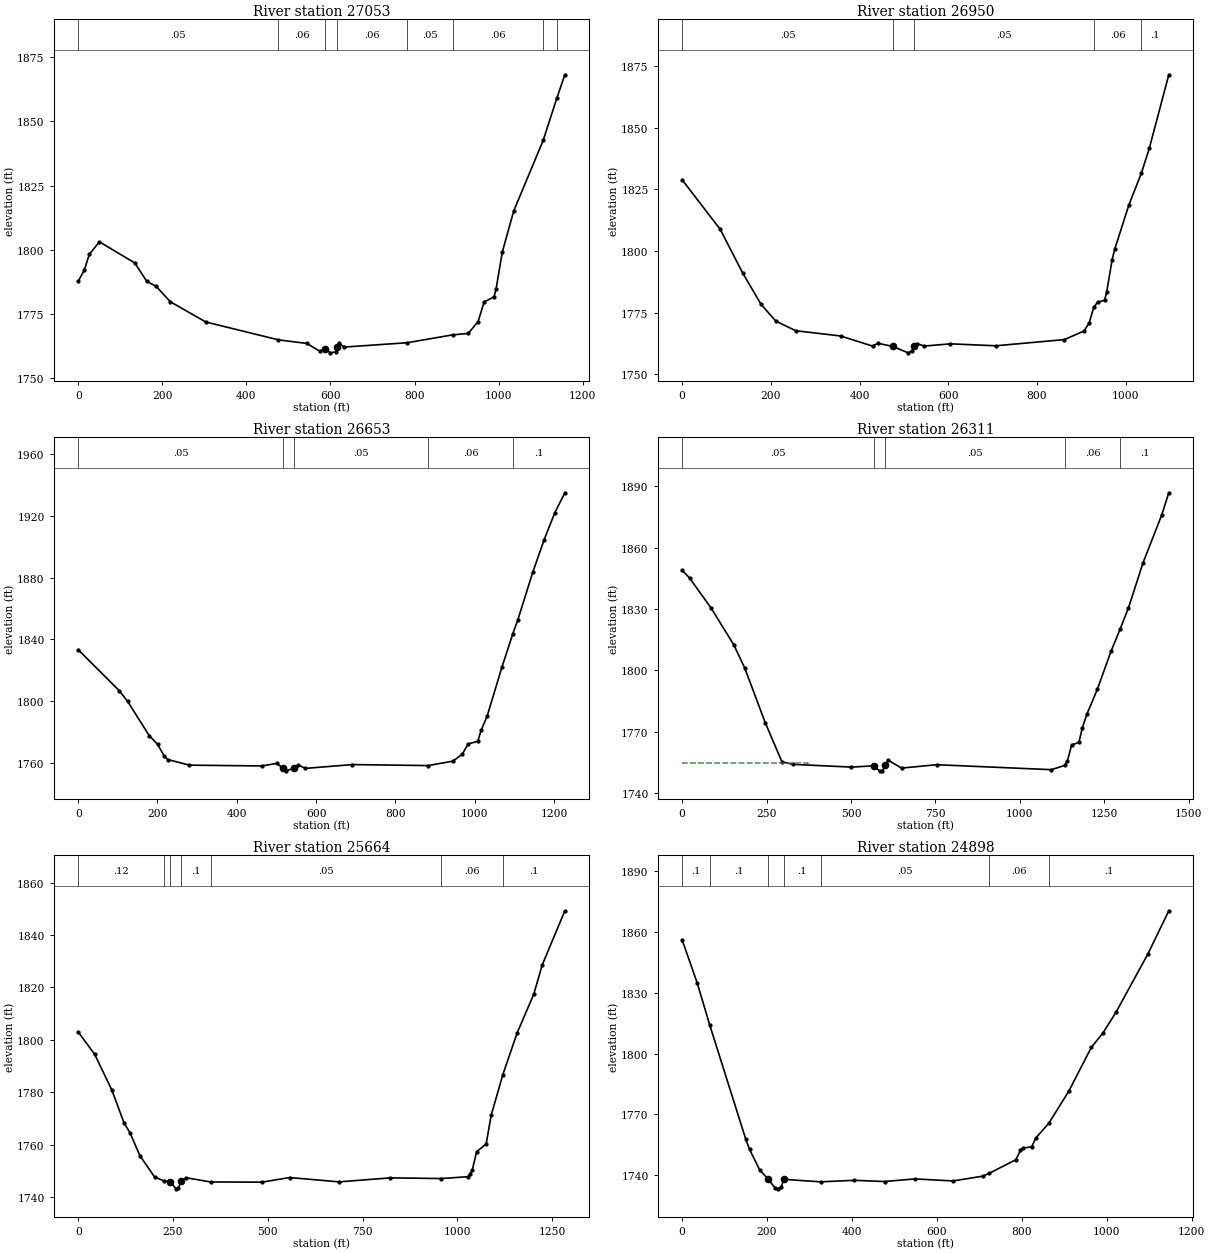
Type RM Length L Ch R = 1 ,27053   ,98.1,102.4,70.5
XS GIS Cut Line= 4
2443872.31797349644355.7242075952444372.31797346644393.224207595
2444563.98464012644382.8075409232444957.73464012644136.974207595
#Sta/Elev= 30
       0 1787.67    14.5 1792.06    26.5 1798.25    50.6 1803.08   134.8 1794.83
   162.9 1787.72   185.7 1785.69     219 1779.74   303.3 1771.85  476.171764.877
   543.9 1763.47   574.3 1760.48     588 1761.18     600 1759.81     612 1760.15
     616 1761.91   620.1 1763.59   632.8 1762.06  782.87 1763.75  890.731766.822
   927.7 1767.37   951.2 1772.01   965.4 1779.62     989 1781.63   993.7 1784.51
  1008.8 1799.17  1036.1  1815.2    11061842.634 1138.841859.288  1157.5 1868.19
#Mann= 8 ,-1 , 0
       0     .05       0  476.17     .06       0     588    .045       0
     616     .06       0  782.87     .05       0  890.73     .06       0
    1106      .1       0 1138.84     .12       0
Bank Sta=588,616
XS Rating Curve= 0 ,0
Exp/Cntr(USF)=0,0
Exp/Cntr=0.5,0.3

Type RM Length L Ch R = 1 ,26950   ,311.5,296.9,239.6
XS GIS Cut Line= 4
2443976.36979674644575.682888563  2444307.964841644475.987646499
2444520.35905235644491.1586615962444979.82408099644211.578526242
#Sta/Elev= 30
       0 1828.84      86 1808.72   136.1 1791.16   177.9 1778.34   211.3 1771.53
   256.2 1767.64   357.1 1765.52   429.2 1761.42   441.4 1762.56     4751761.262
   509.5 1758.68   517.5 1759.42   522.91761.286   529.5 1762.44   545.5 1761.42
   604.8 1762.33   707.1 1761.54   861.7 1764.05     906 1767.53   917.8 1770.94
  927.891777.175   936.6 1779.25   952.2 1779.94     957 1783.34   969.3 1796.43
   975.2 1800.75  1006.8 1818.52 1035.091831.474  1053.1 1841.62    1097 1871.41
#Mann= 5 ,-1 , 0
       0     .05       0     475    .045       0   522.9     .05       0
  927.89     .06       0 1035.09      .1       0
Bank Sta=475,522.9
XS Rating Curve= 0 ,0
Exp/Cntr(USF)=0,0
Exp/Cntr=0.3,0.1

Type RM Length L Ch R = 1 ,26653   ,341.6,342.8,373.7
XS GIS Cut Line= 4
2444080.65130678644914.0575409232444493.15130678644776.557540938
2444638.98464012644709.8908742822445159.81797349644351.557540938
#Sta/Elev= 30
       0 1833.29   103.4 1806.81   124.5 1799.88   179.3 1777.62   200.4 1771.99
   217.2 1764.35   225.7 1762.21   280.5 1758.56     463 1758.05   500.7  1759.7
   515.7 1756.73   524.8 1754.88   544.7 1756.65     555 1758.66   573.1 1756.46
   691.5 1758.93  882.231758.283   945.2 1761.15   968.7 1765.65   983.3 1772.26
  1007.6 1774.01  1016.8 1781.42  1031.5 1790.38  1068.9 1822.15 1096.151843.567
  1108.6 1852.42  1146.5 1883.44  1175.3 1904.57  1201.8 1921.79  1227.4 1934.85
#Mann= 5 ,-1 , 0
       0     .05       0   515.7    .045       0   544.7     .05       0
  882.23     .06       0 1096.15      .1       0
Bank Sta=515.7,544.7
XS Rating Curve= 0 ,0
Exp/Cntr(USF)=0,0
Exp/Cntr=0.3,0.1

Type RM Length L Ch R = 1 ,26311   ,651.5,646.9,440
XS GIS Cut Line= 4
2444141.08367493645217.2000983682444477.01329493645150.014174368
2445090.35576241 644883.437766242445406.77979157644593.021191531
#Sta/Elev= 30
       0 1848.93    22.1 1845.06      85  1830.6   152.6 1812.52   185.3 1801.09
   246.4 1774.22   295.4 1755.26     328 1753.97   501.3 1752.63   566.9 1753.25
   584.4  1750.8   593.1 1750.84   601.3 1753.47   610.5 1755.95   649.8 1752.15
   753.7 1753.79  1093.3 1751.37 1133.641753.513  1140.9 1755.75    1153 1763.37
  1174.8 1764.78  1184.7 1771.75  1198.9 1778.75  1229.1  1790.6  1269.6 1809.18
 1297.391820.359  1321.4 1830.48  1364.8 1852.65  1419.7 1875.84  1440.8 1886.76
#Mann= 5 ,-1 , 0
       0     .05       0   566.9    .045       0   601.3     .05       0
 1133.64     .06       0 1297.39      .1       0
#XS Ineff= 2 , 0
          371.74 1754.87
Permanent Ineff=
       F       F
Bank Sta=566.9,601.3
XS Rating Curve= 0 ,0
Exp/Cntr(USF)=0,0
Exp/Cntr=0.3,0.1

Type RM Length L Ch R = 1 ,25664   ,766.2,766.3,683.2
XS GIS Cut Line= 4
2444687.24021841645815.3715507532444825.94664216 645696.17071785
2445261.57150422645247.5421285612445625.67586654644941.954538756
#Sta/Elev= 30
       0 1803.02    43.7  1794.4      89 1780.75   120.7 1768.36   136.5 1764.54
   162.8 1755.79   201.3 1747.66  225.451746.179   241.5 1745.87   258.7 1743.12
   264.4 1743.51     272 1746.15     285 1747.36  349.211745.743   484.2 1745.67
   557.8 1747.43   687.9 1745.78   823.7 1747.31  957.511747.051    1027 1747.74
  1034.3 1748.78  1039.5 1750.32  1050.8 1757.26  1076.1 1760.25  1089.2 1771.18
 1119.891786.627  1157.7 1802.62  1201.4 1817.33    1224 1828.61  1283.6 1849.25
#Mann= 7 ,-1 , 0
       0     .12       0  225.45      .1       0   241.5    .045       0
     272      .1       0  349.21     .05       0  957.51     .06       0
 1119.89      .1       0
Bank Sta=241.5,272
XS Rating Curve= 0 ,0
Exp/Cntr(USF)=0,0
Exp/Cntr=0.3,0.1

Type RM Length L Ch R = 1 ,24898   ,385.4,388.5,381.2
XS GIS Cut Line= 4
2445359.09945841646203.3160796552445441.45639751 646079.78067101
2445749.21127519645596.4754757862446022.28954693645271.382295142
#Sta/Elev= 30
       0 1856.22    35.4 1834.96   64.951814.139   149.5 1757.92   158.7 1752.67
   182.7 1742.47     203 1737.87   217.9  1733.8   225.4 1733.15   232.8 1733.91
   239.6 1737.84  326.241736.617   405.6 1737.36   476.7 1736.77   547.9 1738.06
     638 1737.05   709.2 1739.46  722.341740.743     786 1747.55   796.6 1752.12
   801.9 1753.31     823 1753.86   833.2 1758.38  863.291765.513   910.4 1781.36
   963.8 1803.13   991.2 1810.24  1021.8 1820.47    1097 1849.32    1146 1870.57
#Mann= 7 ,-1 , 0
       0      .1       0   64.95      .1       0     203    .045       0
   239.6      .1       0  326.24     .05       0  722.34     .06       0
  863.29      .1       0
Bank Sta=203,239.6
XS Rating Curve= 0 ,0
Exp/Cntr(USF)=0,0
Exp/Cntr=0.3,0.1

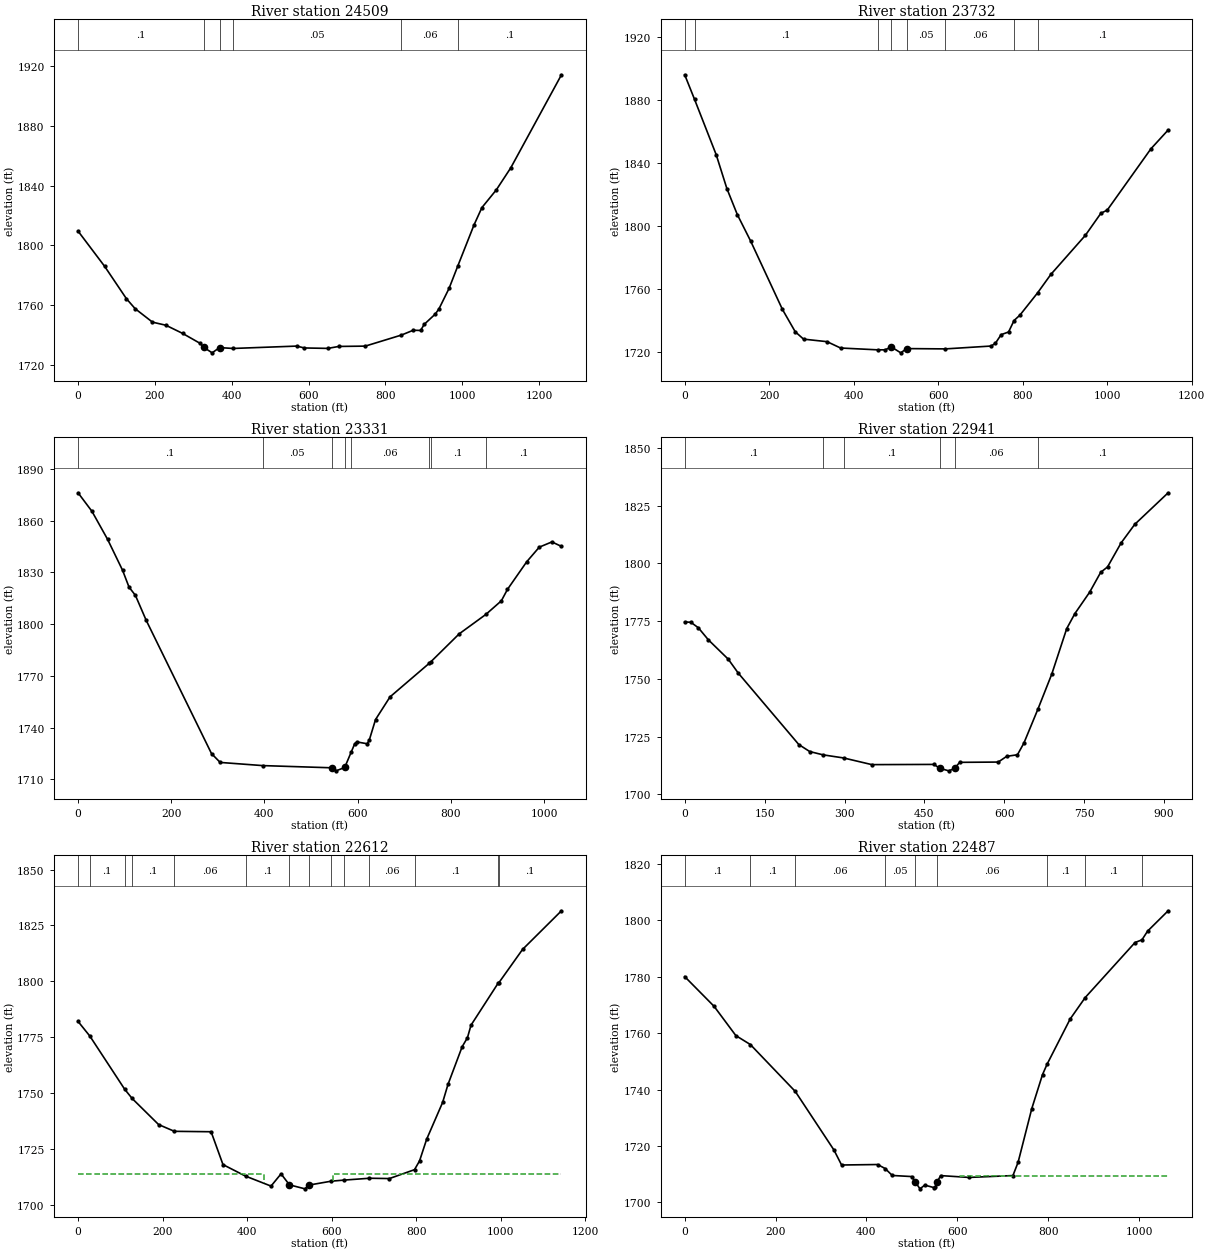
Type RM Length L Ch R = 1 ,24509   ,756.2,776.8,730.7
XS GIS Cut Line= 4
 2445606.1702757646478.5616392672445749.21127519646285.673018752
2446147.99224344645685.3342784962446310.53883376645436.096173335
#Sta/Elev= 30
       0  1809.6    69.3 1786.02     126 1764.39   148.7 1757.72   193.8 1748.73
   228.7 1746.66   272.1 1741.23   318.3 1734.48   327.21731.893   349.1 1728.22
   368.3 1731.73  403.471731.148   569.3 1732.73   589.2 1731.48   650.1 1731.19
   678.9  1732.5   747.7 1732.71  841.951740.114   872.5 1743.31   891.8 1743.19
   901.1 1747.25     930 1754.15   939.8 1757.74   965.9 1771.33  988.371786.138
  1030.6  1813.6  1051.3 1825.29  1088.9 1837.16  1126.5 1851.89  1258.4 1914.05
#Mann= 6 ,-1 , 0
       0      .1       0   327.2    .045       0   368.3      .1       0
  403.47     .05       0  841.95     .06       0  988.37      .1       0
Bank Sta=327.2,368.3
XS Rating Curve= 0 ,0
Exp/Cntr(USF)=0,0
Exp/Cntr=0.3,0.1

Type RM Length L Ch R = 1 ,23732   ,402.8,401.6,399.1
XS GIS Cut Line= 4
2446239.01833402646857.8370166862446416.73593944646628.104502364
2446648.63574163646209.8179432682446787.34216538645860.884596044
#Sta/Elev= 30
       0 1895.79   23.281880.206    74.5 1845.19    99.8 1823.73   124.5 1807.26
   155.9 1790.57   231.3 1747.18   261.6 1733.04   281.3 1728.38     337 1726.77
   368.8 1722.76  456.571721.602   474.8 1721.61   488.5 1723.51   511.4  1719.7
   525.1 1722.39  617.121722.198   725.3 1724.01   735.5 1725.82   748.9 1731.21
   766.5 1732.91   779.51740.176   793.4 1743.59  835.081757.649   866.6 1769.37
   948.2 1794.09   985.1 1808.12    1000 1810.07  1103.3 1848.88  1144.2 1860.82
#Mann= 8 ,-1 , 0
       0      .1       0   23.28      .1       0  456.57     .05       0
   488.5    .045       0   525.1     .05       0  617.12     .06       0
   779.5      .1       0  835.08      .1       0
Bank Sta=488.5,525.1
XS Rating Curve= 0 ,0
Exp/Cntr(USF)=0,0
Exp/Cntr=0.3,0.1

Type RM Length L Ch R = 1 ,23331   ,429.3,389.6,383
XS GIS Cut Line= 4
2446639.96659015647065.8966522982446743.99640796646883.844471137
2446969.39434654646424.3794424932447116.76992176646144.799307139
#Sta/Elev= 30
       0 1876.22    29.8  1865.5    63.4 1849.23    95.6 1831.26   109.4 1821.52
   123.2 1816.68   146.3 1802.22   286.5 1724.89   305.1 1719.78  395.931717.947
   544.9 1716.66   553.8  1714.9   572.31716.847   586.41725.863   593.9 1730.67
   598.4 1731.68   620.6 1730.61   625.1 1732.79   638.5 1744.67   669.6 1757.81
  753.631777.266  756.671778.031   818.1 1794.39  875.161805.627   908.5 1813.54
   921.6 1820.17   962.8 1836.15   989.9 1844.68    1017 1847.71  1037.5  1845.1
#Mann= 8 ,-1 , 0
       0      .1       0  395.93     .05       0   544.9    .045       0
   572.3     .05       0   586.4     .06       0  753.63      .1       0
  756.67      .1       0  875.16      .1       0
Bank Sta=544.9,572.3
XS Rating Curve= 0 ,0
Exp/Cntr(USF)=0,0
Exp/Cntr=0.3,0.1

Type RM Length L Ch R = 1 ,22941   ,312,329.1,314.9
XS GIS Cut Line= 4
2447092.92975518 647137.417152042447220.79973957647059.394788685
2447277.14922421646493.7326543642447212.13058808646316.015048945
#Sta/Elev= 30
       0 1774.67    11.5 1774.52    25.6 1772.14    44.3 1766.94    81.8 1758.52
   100.5 1752.51   214.2 1721.56   234.7 1718.53     2601717.094   298.3 1715.76
   351.3 1712.87   467.9 1712.96   478.6 1711.29   495.7 1710.18   506.6 1711.23
   516.1 1713.86   588.5 1713.98   604.5 1716.47   624.6 1717.14   636.7  1722.2
  663.011736.888     689 1752.05   717.1 1771.78   732.4 1778.28   760.2 1787.57
   780.9 1796.16   793.7 1798.48   819.2 1808.89   844.8 1816.92   907.5  1830.6
#Mann= 6 ,-1 , 0
       0      .1       0     260     .05       0   298.3      .1       0
   478.6    .045       0   506.6     .06       0  663.01      .1       0
Bank Sta=478.6,506.6
XS Rating Curve= 0 ,0
Exp/Cntr(USF)=0,0
Exp/Cntr=0.5,0.3

Type RM Length L Ch R = 1 ,22612   ,125.5,124.9,120.1
BEGIN DESCRIPTION:
Had to increase the ineffective flow a little bit to remove the crossing profile
END DESCRIPTION:
XS GIS Cut Line= 4
2447613.07884421647312.9674695872447636.91901079646942.361243653
2447376.84446628646699.6250021052447251.14176976646303.011321719
#Sta/Elev= 30
       0 1782.06      28 1775.47  110.291751.693   127.91747.566   190.5 1735.88
  227.811732.849   314.7 1732.66   342.8 1717.95   396.2 1712.79   456.4 1708.33
   480.1 1713.81   499.9 1708.89   536.7  1707.1   545.2 1708.76   598.9 1710.53
  628.641711.003  689.241711.844   736.3  1711.7  795.671715.681   807.6  1719.6
   824.4  1729.3   862.2  1745.8   874.8 1753.81   908.3  1770.7   920.9 1774.77
   929.3 1780.37  993.04 1799.05  994.85 1799.28  1051.2 1814.28  1143.2 1831.58
#Mann= 14 ,-1 , 0
       0      .1       0      28      .1       0  110.29      .1       0
   127.9      .1       0  227.81     .06       0   396.2      .1       0
   499.9    .045       0   545.2      .1       0   598.9     .06       0
  628.64      .1       0  689.24     .06       0  795.67      .1       0
  993.04      .1       0  994.85      .1       0
#XS Ineff= 2 , 0
          440.42 1713.71  603.54         1713.87
Permanent Ineff=
       F       F
Bank Sta=499.9,545.2
XS Rating Curve= 0 ,0
Exp/Cntr(USF)=0,0
Exp/Cntr=0.5,0.3

Type RM Length L Ch R = 1 ,22487   ,472.9,608,642.5
XS GIS Cut Line= 4
2447686.76663182  647319.46933322447691.10120757646860.004304557
2447463.53598112646634.606365977 2447322.6622695646387.535548687
#Sta/Elev= 30
       0 1780.05    64.6 1769.53   112.6 1759.14  144.531755.972  243.381739.349
   328.6 1718.56   345.3 1713.27   424.6 1713.44  441.09 1712.03   456.9 1709.56
   500.1 1709.17  507.82 1707.19   517.9 1704.82   528.4 1706.14   548.2 1705.28
     552 1705.64  555.28 1707.17   563.4 1709.51   625.9 1708.87   722.5 1709.52
   733.9 1714.24     764 1733.26   787.6 1745.31  797.761749.018   848.5 1765.03
  881.711772.648   991.3 1792.14 1006.521793.089  1018.9 1796.17  1064.2 1803.39
#Mann= 9 ,-1 , 0
       0      .1       0  144.53      .1       0  243.38     .06       0
  441.09     .05       0  507.82    .045       0  555.28     .06       0
  797.76      .1       0  881.71      .1       0 1006.52      .1       0
#XS Ineff= 2 , 0
                          605.07         1709.33
Permanent Ineff=
       F       F
Bank Sta=507.82,555.28
XS Rating Curve= 0 ,0
Exp/Cntr(USF)=0,0
Exp/Cntr=0.5,0.3

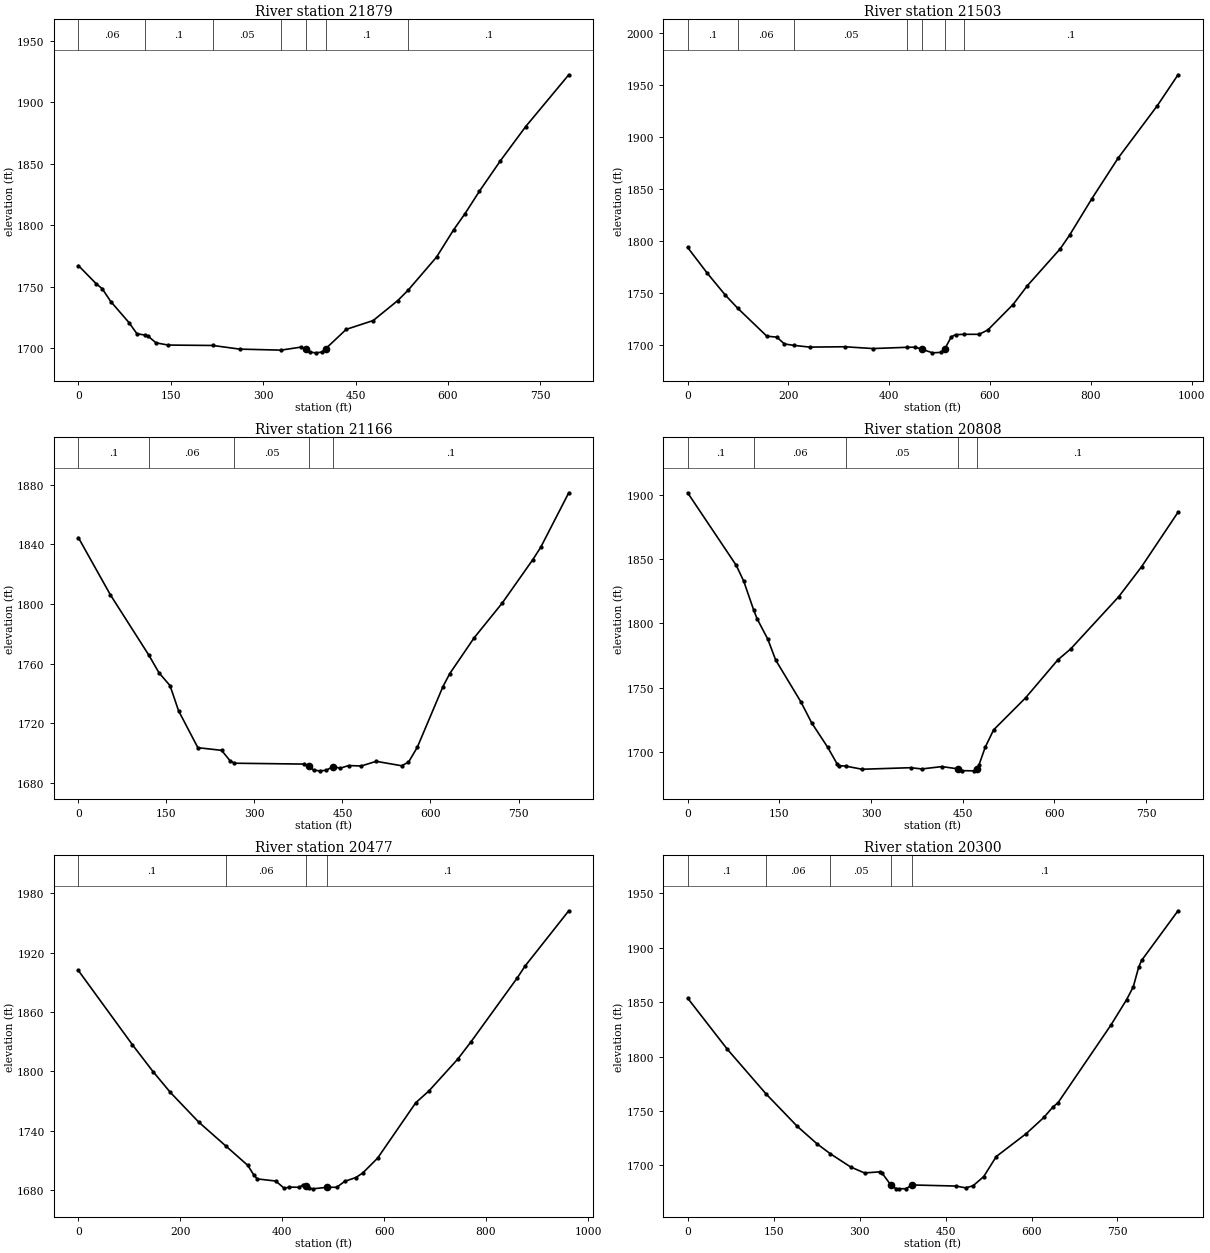
Type RM Length L Ch R = 1 ,21879   ,383.8,376.4,375
XS GIS Cut Line= 4
2447738.78154073647304.2983181042447812.46932834647254.450697072
 2448144.0643726647020.3836070082448404.13891711 646868.67345604
#Sta/Elev= 30
       0 1767.39    28.9 1752.58    38.6 1748.58    52.8 1737.95    82.1    1721
    95.1 1711.86  107.941710.847   113.2 1709.89     126  1704.5   145.6 1702.69
  218.441702.344   261.6 1699.39  328.951698.564     361    1701   368.7 1699.64
   375.7 1696.94   385.5 1696.36   395.3 1696.98   401.31699.686   434.7 1715.44
   478.5 1722.63   518.4 1738.89  535.34 1747.42   581.3 1774.24     609 1796.42
   627.6 1809.64   650.8 1827.77   685.1  1852.7     726  1880.4   795.9 1922.53
#Mann= 7 ,-1 , 0
       0     .06       0  107.94      .1       0  218.44     .05       0
  328.95      .1       0   368.7    .045       0   401.3      .1       0
  535.34      .1       0
Bank Sta=368.7,401.3
XS Rating Curve= 0 ,0
Exp/Cntr(USF)=0,0
Exp/Cntr=0.3,0.1

Type RM Length L Ch R = 1 ,21503   ,341.9,336.7,332.6
XS GIS Cut Line= 4
2447814.63661621647718.2503014572447949.00846421647622.889635135
2448341.28756886647325.9711968132448577.52194679 647115.74427333
#Sta/Elev= 30
       0 1793.47    39.4 1768.44    74.9 1747.58    99.3 1735.03   157.1 1708.09
     177 1707.18     192 1700.63  210.661699.246   242.2 1697.58   311.6 1697.91
   367.6 1696.19  435.451697.396   451.5 1697.49   465.41695.483   485.8 1692.06
   502.8 1692.52   509.81695.467   523.1 1707.46   531.5  1709.5  547.841709.897
   578.3 1709.88   595.6 1714.04   645.7 1738.58   674.1  1756.7   739.3 1792.24
   757.7 1805.22   801.6 1840.08   853.9 1879.32     932    1930     973 1959.67
#Mann= 7 ,-1 , 0
       0      .1       0    99.3     .06       0  210.66     .05       0
  435.45     .12       0   465.4    .045       0   509.8     .12       0
  547.84      .1       0
Bank Sta=465.4,509.8
XS Rating Curve= 0 ,0
Exp/Cntr(USF)=0,0
Exp/Cntr=0.3,0.1

Type RM Length L Ch R = 1 ,21166   ,337,358.2,352.3
XS GIS Cut Line= 5
2448081.21302434648080.1873759082448213.41758447647885.131467521
2448289.27265995647765.9306346182448369.46231118647692.242847006
2448649.04244653647482.015923523
#Sta/Elev= 30
       0 1844.55    54.7 1806.11  120.291765.638   137.4 1753.95   156.2 1745.34
   170.7 1728.54   203.6 1703.76     244 1701.99   258.5    1695  265.941693.356
   384.4 1692.78   392.21691.451   400.7 1688.74     411 1688.25   422.4 1688.59
   433.3 1691.08   446.4 1690.03   460.4 1691.79     482  1691.5   507.5 1694.62
   550.6 1691.67   562.5 1694.03   577.5 1704.04   621.2 1744.69   632.6 1753.29
   674.4 1777.42     722 1800.57   774.3 1829.77   787.7    1838   835.6  1874.6
#Mann= 5 ,-1 , 0
       0      .1       0  120.29     .06       0  265.94     .05       0
   392.2    .045       0   433.3      .1       0
Bank Sta=392.2,433.3
XS Rating Curve= 0 ,0
Exp/Cntr(USF)=0,0
Exp/Cntr=0.3,0.1

Type RM Length L Ch R = 1 ,20808   ,302.8,330.9,316.6
XS GIS Cut Line= 4
2448271.56970449648264.9531512812448430.26923668648117.589299959
2448653.20429381647875.7614413792448842.13230833647701.947668024
#Sta/Elev= 30
       0 1901.86    79.5 1845.33    91.7 1833.06     108 1810.57   113.5 1803.81
   131.1 1787.83   144.1 1771.46   185.3 1738.89   202.9 1722.58   229.1 1703.56
   244.3  1690.8   247.4 1689.25   258.4 1688.88   285.5 1686.43   364.8 1687.64
     383 1686.67   416.1  1688.5   441.5 1686.77   448.7 1685.33   467.9 1685.19
   473.6 1686.93   476.4 1689.52   486.8 1703.58   500.5 1717.11   552.7 1742.01
   605.8 1771.78   626.4 1780.08   705.2 1820.88   742.5 1844.18   802.2 1886.69
#Mann= 5 ,-1 , 0
       0      .1       0     108     .06       0   258.4     .05       0
   441.5    .045       0   473.6      .1       0
Bank Sta=441.5,473.6
XS Rating Curve= 0 ,0
Exp/Cntr(USF)=0,0
Exp/Cntr=0.3,0.1

Type RM Length L Ch R = 1 ,20477   ,170.9,177,178.5
XS GIS Cut Line= 4
2448466.48254986648510.0020830612448730.74566475648245.738968175
2448862.87722219648070.6646545632449067.68113623647763.458783508
#Sta/Elev= 30
       0 1901.91   106.2 1826.71   146.6 1799.61   180.6 1778.56   236.3 1748.53
  289.311724.446   332.5  1704.8   344.6 1694.82   351.1 1691.14   387.2 1688.98
   404.3 1681.52   413.6 1682.88   432.4 1682.65   441.4 1684.82   447.2 1683.58
   453.4 1681.54     460 1681.09   487.5 1682.63   507.1 1682.67   522.6 1688.66
   544.3 1692.49   557.7 1696.96   587.1 1712.09     662 1768.13     688 1780.16
   744.3  1812.2   770.7 1829.97   861.1 1894.32   876.4 1906.29   962.3  1962.3
#Mann= 4 ,-1 , 0
       0      .1       0  289.31     .06       0   447.2    .045       0
   487.5      .1       0
Bank Sta=447.2,487.5
XS Rating Curve= 0 ,0
Exp/Cntr(USF)=0,0
Exp/Cntr=0.3,0.1

Type RM Length L Ch R = 1 ,20300   ,375.1,420.9,446.9
XS GIS Cut Line= 4
2448570.07596742648533.2309318932448823.23950688648355.638598248
2448997.05328023648193.1605057652449261.55250055648034.460973572
#Sta/Elev= 30
       0 1853.72    69.2 1806.73   137.1 1765.42   191.4 1735.71   226.1 1719.51
   249.1  1710.5   284.2 1698.41   308.6 1692.87   335.9 1693.91   339.6 1692.45
   354.7 1681.71   363.2 1678.56   368.9 1678.25   380.6 1678.43   392.3 1681.81
   467.9 1680.82   484.9  1679.2   497.8 1680.99   516.6 1689.52   538.5 1707.98
   590.5 1728.94   621.6 1743.99   637.1 1753.43   646.3 1757.55   738.2 1828.68
   765.8 1852.24   777.5 1864.06     787 1882.36     792 1888.38   855.6 1934.09
#Mann= 5 ,-1 , 0
       0      .1       0   137.1     .06       0   249.1     .05       0
   354.7    .045       0   392.3      .1       0
Bank Sta=354.7,392.3
XS Rating Curve= 0 ,0
Exp/Cntr(USF)=0,0
Exp/Cntr=0.5,0.3

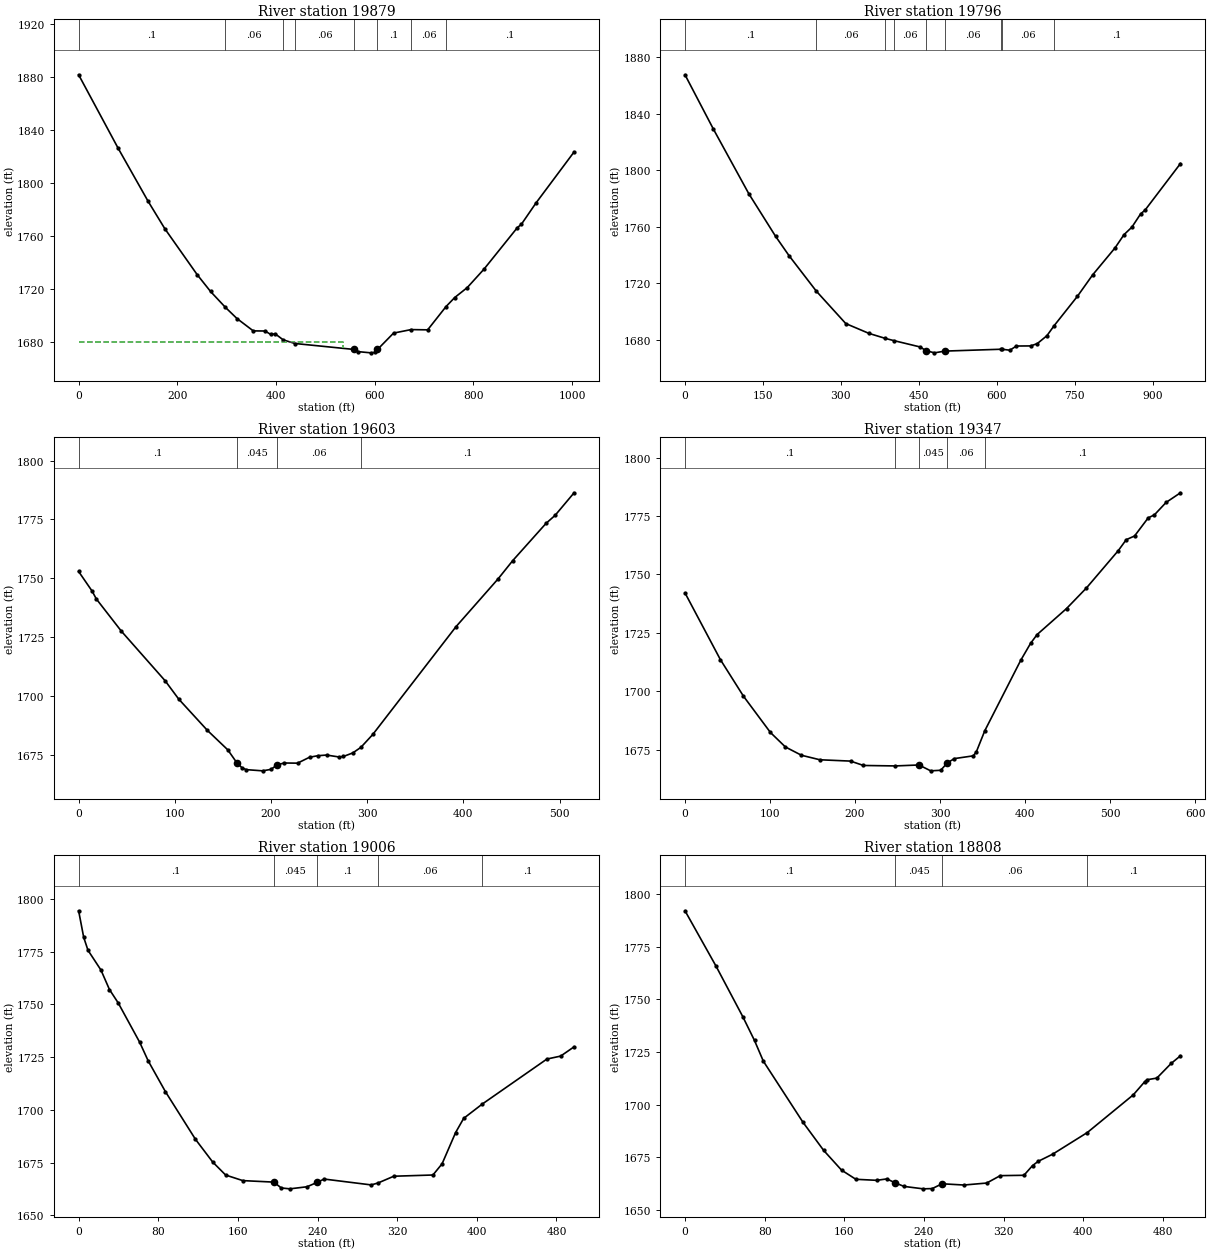
Type RM Length L Ch R = 1 ,19879   ,83.5,83.3,84.1
XS GIS Cut Line= 4
2448563.14503501648589.3402932122448906.44343377648419.641652916
2449126.85661025648657.6098611472449407.73711833648562.032466038
#Sta/Elev= 30
       0  1881.5    79.9 1826.28   140.9 1786.15   174.7 1765.55   240.2 1730.98
   267.3  1718.3  297.351706.364   320.8 1697.94   353.9 1688.61   377.8 1688.52
   389.3 1685.92   398.3  1686.4  414.581681.844  438.521679.104   558.71674.613
   566.6 1672.98   592.1 1672.08   600.6 1672.41   605.61674.599   638.2 1686.95
  673.751689.588   707.3  1689.4  744.481706.912   762.1 1713.72   787.5 1721.22
   821.3 1735.05   888.9 1766.31   897.3 1768.96   926.8 1784.94    1004 1823.39
#Mann= 8 ,-1 , 0
       0      .1       0  297.35     .06       0  414.58      .1       0
  438.52     .06       0   558.7    .045       0   605.6      .1       0
  673.75     .06       0  744.48      .1       0
#XS Ineff= 2 , 0
          536.64 1679.88  626.03         1679.94
Permanent Ineff=
       F       F
Bank Sta=558.7,605.6
XS Rating Curve= 0 ,0
Exp/Cntr(USF)=0,0
Exp/Cntr=0.5,0.3

Type RM Length L Ch R = 1 ,19796   ,207.3,192.4,167.7
XS GIS Cut Line= 4
2448604.10677577648610.7964431342448892.78952019648499.614575354
2449076.14207407648737.5827835862449403.83600016648634.203152141
#Sta/Elev= 30
       0 1867.49    54.6 1829.06   122.8 1783.29   174.3 1753.15     200 1739.56
   252.61714.382   309.4 1691.39   353.9 1684.46  385.441680.903  401.381679.382
   452.8 1674.81   463.3 1672.26   480.1 1670.68   500.3 1671.92  608.011673.227
  609.951673.229   625.1 1672.54   637.7  1675.5     665 1675.58   677.8 1677.19
   696.4  1682.8  710.321689.913   755.1 1710.69   784.5 1725.89   827.6 1745.01
   844.7  1754.3     860 1759.68   876.7    1769   885.4 1771.76   953.4 1804.66
#Mann= 9 ,-1 , 0
       0      .1       0   252.6     .06       0  385.44      .1       0
  401.38     .06       0   463.3    .045       0   500.3     .06       0
  608.01      .1       0  609.95     .06       0  710.32      .1       0
Bank Sta=463.3,500.3
XS Rating Curve= 0 ,0
Exp/Cntr(USF)=0,0
Exp/Cntr=0.5,0.3

Type RM Length L Ch R = 1 ,19603   ,258.1,255.9,253
XS GIS Cut Line= 4
2448914.24567011648878.0230376242449031.27921514648819.506265108
2449224.38456444648731.731106334 2449386.2809684648673.214333818
#Sta/Elev= 30
       0 1752.91      14 1744.59    18.4 1741.26    44.4 1727.59      90  1706.5
   104.1 1698.73   133.9 1685.46   155.1  1677.2   164.61671.654   169.8 1669.63
   174.2 1668.81   191.3  1668.3     200 1668.93   206.4 1670.84   213.7 1671.63
   227.6 1671.56   240.1 1674.08   248.9 1674.73   257.8    1675   270.9 1674.17
   275.3  1674.4     285  1675.9  293.461678.272   305.8 1683.73   392.3 1729.47
   436.1 1749.78   451.3 1757.52     486 1773.36   495.4 1776.75   515.1 1786.32
#Mann= 4 ,-1 , 0
       0      .1       0   164.6    .045       0   206.4     .06       0
  293.46      .1       0
Bank Sta=164.6,206.4
XS Rating Curve= 0 ,0
Exp/Cntr(USF)=0,0
Exp/Cntr=0.3,0.1

Type RM Length L Ch R = 1 ,19347   ,336.3,341,304.5
XS GIS Cut Line= 4
2449002.02082888 649117.941804942449093.69710582649069.177827843
2449339.46755039648934.5892510562449509.16619069648831.209619611
#Sta/Elev= 30
       0 1742.08    41.6 1713.53    68.8 1697.85   100.5 1682.32   118.1 1676.12
     137 1672.57   158.6 1670.64   194.7 1670.07   209.9  1668.2  247.31    1668
   275.2 1668.41     289  1665.9   300.8 1666.14   308.5 1669.28   316.8 1671.14
   339.1 1672.32   342.7 1674.04  352.671683.099   394.9 1713.22   406.5 1720.49
   414.2 1724.26   448.8 1735.39   472.2  1744.2   509.7 1760.21     519 1764.87
   528.8 1766.46   544.9 1774.24   552.1 1775.49   565.9 1780.83   582.8 1784.96
#Mann= 5 ,-1 , 0
       0      .1       0  247.31     .06       0   275.2    .045       0
   308.5     .06       0  352.67      .1       0
Bank Sta=275.2,308.5
XS Rating Curve= 0 ,0
Exp/Cntr(USF)=0,0
Exp/Cntr=0.3,0.1

Type RM Length L Ch R = 1 ,19006   ,196.4,197.7,186.8
XS GIS Cut Line= 4
2449081.99375132 649365.662808592449239.98903711649301.294358823
2449384.33040932649244.7281453912449534.52345878649160.854104785
#Sta/Elev= 30
       0 1794.43     5.1 1781.83     9.4  1775.7    22.4 1766.35      31 1757.06
    39.7 1750.79    61.3 1732.12    69.9 1723.25    87.2 1708.66   117.4 1686.05
   134.7 1675.29   147.7 1669.13   164.9 1666.49   196.11665.779   203.6    1663
   212.2 1662.59   229.4 1663.57   239.4 1665.61   246.6 1667.23   293.9 1664.45
  300.841665.383   316.6 1668.57   355.9 1669.15   365.1 1674.46   378.7 1689.29
   386.8 1696.01  405.521702.806   470.4 1724.13   484.2 1725.53   497.7 1729.92
#Mann= 5 ,-1 , 0
       0      .1       0   196.1    .045       0   239.4      .1       0
  300.84     .06       0  405.52      .1       0
Bank Sta=196.1,239.4
XS Rating Curve= 0 ,0
Exp/Cntr(USF)=0,0
Exp/Cntr=0.3,0.1

Type RM Length L Ch R = 1 ,18808   ,291.6,287.1,261.7
XS GIS Cut Line= 4
2449175.62058735649545.1142443062449353.12146398  649461.2402037
2449460.40221359649402.7234311842449610.59526305649305.195476991
#Sta/Elev= 30
       0 1791.98    31.1 1765.76    58.1 1741.67    69.8 1730.42    78.7 1720.59
   118.5  1691.6   139.2  1678.3   157.2 1668.91   171.6 1664.55   192.5 1664.06
   202.7 1664.73     211 1662.89   219.9 1661.18   239.2 1660.02   248.3 1660.14
   258.2 1662.42   280.2 1661.83     303 1662.77   316.6 1666.28   340.4 1666.45
     349 1671.03   354.7 1673.07   369.3 1676.48  404.081686.748   450.2 1704.62
   461.8  1710.9   464.4 1711.82   473.9 1712.58   488.2 1719.51   497.6 1723.16
#Mann= 4 ,-1 , 0
       0      .1       0     211    .045       0   258.2     .06       0
  404.08      .1       0
Bank Sta=211,258.2
XS Rating Curve= 0 ,0
Exp/Cntr(USF)=0,0
Exp/Cntr=0.3,0.1

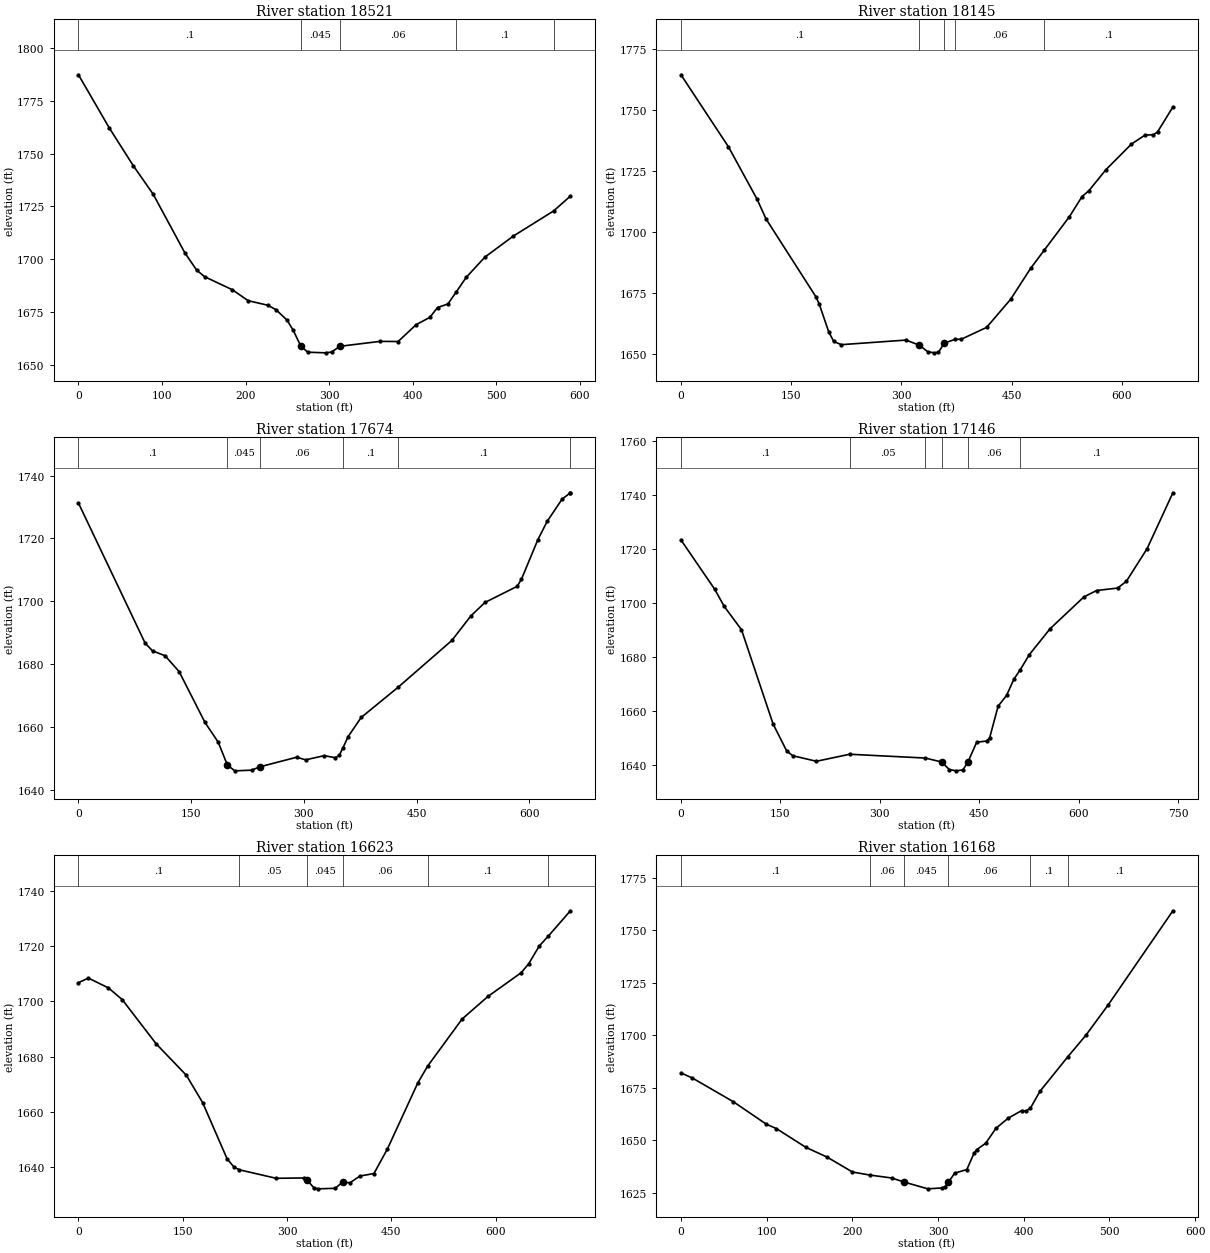
Type RM Length L Ch R = 1 ,18521   ,376.7,376.1,383.3
XS GIS Cut Line= 4
2449347.26978673649798.686925209 2449544.2762542649673.851143841
2449715.92545358649517.8064171322449811.50284869649439.784053777
#Sta/Elev= 30
       0  1787.3      37 1762.06    65.7  1744.2    89.4 1730.77   127.2 1703.07
   141.4 1694.83   150.9 1691.71   184.1 1685.54     203 1680.36   226.7 1678.18
   236.6 1676.01   249.5 1671.18   256.9 1666.38   266.11658.781   274.4 1655.96
     296 1655.66     303 1656.07   312.81658.754   360.9 1661.09   382.5 1661.02
   404.1 1669.03   420.4 1672.44   429.6  1677.1     442 1678.79  452.321684.635
   463.8 1691.33   486.3 1700.98   520.5 1710.98  568.47 1722.82   588.6 1729.87
#Mann= 5 ,-1 , 0
       0      .1       0   266.1    .045       0   312.8     .06       0
  452.32      .1       0  568.47      .1       0
Bank Sta=266.1,312.8
XS Rating Curve= 0 ,0
Exp/Cntr(USF)=0,0
Exp/Cntr=0.3,0.1

Type RM Length L Ch R = 1 ,18145   ,422,471.7,415.1
XS GIS Cut Line= 4
2449550.12793145650102.9741422922449704.22209907650009.347306266
2449922.68471647649853.3025795572450086.53167951649705.060089183
#Sta/Elev= 30
       0 1764.52    64.6 1735.03   103.7 1713.49   115.7 1705.51   183.9 1673.46
   188.3 1670.53   201.1 1659.22     208 1655.25   218.3 1653.94   306.3 1655.82
   324.4 1653.74   335.8 1651.09   344.5 1650.59   350.5 1650.77   358.41654.563
  373.15 1656.12   381.7 1656.17   416.1 1661.02   448.9 1672.57     476  1685.2
  494.441692.612   528.8 1706.37     546 1714.62   555.3 1717.01   578.3 1725.56
   613.3 1736.14   631.8 1739.81   643.2 1739.97   648.8 1741.13   669.7 1751.33
#Mann= 5 ,-1 , 0
       0      .1       0   324.4    .045       0   358.4      .1       0
  373.15     .06       0  494.44      .1       0
Bank Sta=324.4,358.4
XS Rating Curve= 0 ,0
Exp/Cntr(USF)=0,0
Exp/Cntr=0.3,0.1

Type RM Length L Ch R = 1 ,17674   ,491.4,527.2,489.9
XS GIS Cut Line= 4
2449770.54110793650456.0253364712449889.52521204650387.755768536
2450086.53167951 650243.414396332450299.14261965 650071.76519695
#Sta/Elev= 30
       0 1731.25    88.9 1686.61    98.7 1684.22   115.3 1682.67     134 1677.63
   168.4 1661.45     186 1655.18   198.2  1647.9   208.1 1646.06   230.3 1646.27
   241.7 1647.36   290.4 1650.39   302.3 1649.56   327.1 1650.89     342 1650.23
     347 1650.94  352.081653.432     359 1656.98   376.2 1663.03  425.551672.676
   496.9 1687.53   522.3 1695.36     541 1699.63   583.9 1704.76   589.6 1707.05
   611.5 1719.64   623.7 1725.39   643.6 1732.48  654.241734.451   654.7 1734.52
#Mann= 6 ,-1 , 0
       0      .1       0   198.2    .045       0   241.7     .06       0
  352.08      .1       0  425.55      .1       0  654.24      .1       0
Bank Sta=198.2,241.7
XS Rating Curve= 0 ,0
Exp/Cntr(USF)=0,0
Exp/Cntr=0.3,0.1

Type RM Length L Ch R = 1 ,17146   ,516.5,523,516
XS GIS Cut Line= 4
2450012.41043433650924.1595165992450113.83950669650840.285475993
 2450402.5222511650608.1689450132450578.07256865650444.321981968
#Sta/Elev= 30
       0 1723.25    50.9    1705    65.3 1698.64    91.3 1690.02   138.9 1655.18
   159.4 1645.19   168.7 1643.37   204.4 1641.32  254.56 1643.92  368.781642.513
   393.3 1641.05   404.8 1638.27   415.1 1637.78   425.3 1638.12   432.91641.015
   446.2  1648.4   461.3 1648.81   465.8 1650.08   478.5 1661.72   491.3 1665.72
   502.3 1671.71  511.471675.054   525.7 1680.82   556.9 1690.38   607.8 1702.14
     627 1704.53   658.8 1705.44     672 1707.94   703.2 1720.01   742.2 1740.71
#Mann= 6 ,-1 , 0
       0      .1       0  254.56     .05       0  368.78     .06       0
   393.3    .045       0   432.9     .06       0  511.47      .1       0
Bank Sta=393.3,432.9
XS Rating Curve= 0 ,0
Exp/Cntr(USF)=0,0
Exp/Cntr=0.3,0.1

Type RM Length L Ch R = 1 ,16623   ,453,455.7,459.2
XS GIS Cut Line= 4
2450443.48399186 651343.529719632450552.71530056651181.633315669
2450726.31505902650953.4179028572450896.01369932650805.175412483
#Sta/Elev= 30
       0 1706.75    14.3 1708.42    43.1 1704.87      63 1700.61   111.8 1684.59
   155.2  1673.2   178.6 1663.29   213.8  1642.9   223.9 1639.91  231.531638.955
   284.2 1635.88   324.4    1636   329.1 1635.16   338.6 1632.41     344 1632.06
   369.6 1632.26   379.7 1634.56   390.3 1634.24   404.8 1636.69   424.9 1637.61
   444.2 1646.46   487.9 1670.39  502.09 1676.52   551.7  1693.6   589.2 1701.84
   636.6 1710.36   647.3 1713.56   662.7 1720.07  675.771723.662   707.4 1732.81
#Mann= 6 ,-1 , 0
       0      .1       0  231.53     .05       0   329.1    .045       0
   379.7     .06       0  502.09      .1       0  675.77      .1       0
Bank Sta=329.1,379.7
XS Rating Curve= 0 ,0
Exp/Cntr(USF)=0,0
Exp/Cntr=0.3,0.1

Type RM Length L Ch R = 1 ,16168   ,368,374.3,375.2
XS GIS Cut Line= 4
2450739.96897261651538.5856280172450876.50810848651446.909351075
2451036.45395335651312.320774288 2451188.5975619651181.633315669
#Sta/Elev= 30
       0 1682.06    13.3 1679.64    61.2 1668.31    99.7  1657.6   111.3 1655.55
   145.9 1646.55   170.7 1641.91   200.1 1634.83  220.421633.379   245.8 1631.99
   260.81629.999   288.1 1626.81   305.2 1627.25   308.5 1627.91   312.21629.975
   319.4 1634.29   333.6    1636   342.1 1643.86   345.1 1645.48   355.6 1648.54
   367.6 1655.66   381.8 1660.47   397.6 1664.11   402.9 1663.93  407.861665.299
   418.9 1673.26  451.171689.618   472.6 1700.05   498.5 1714.45   574.1 1759.35
#Mann= 6 ,-1 , 0
       0      .1       0  220.42     .06       0   260.8    .045       0
   312.2     .06       0  407.86      .1       0  451.17      .1       0
Bank Sta=260.8,312.2
XS Rating Curve= 0 ,0
Exp/Cntr(USF)=0,0
Exp/Cntr=0.3,0.1