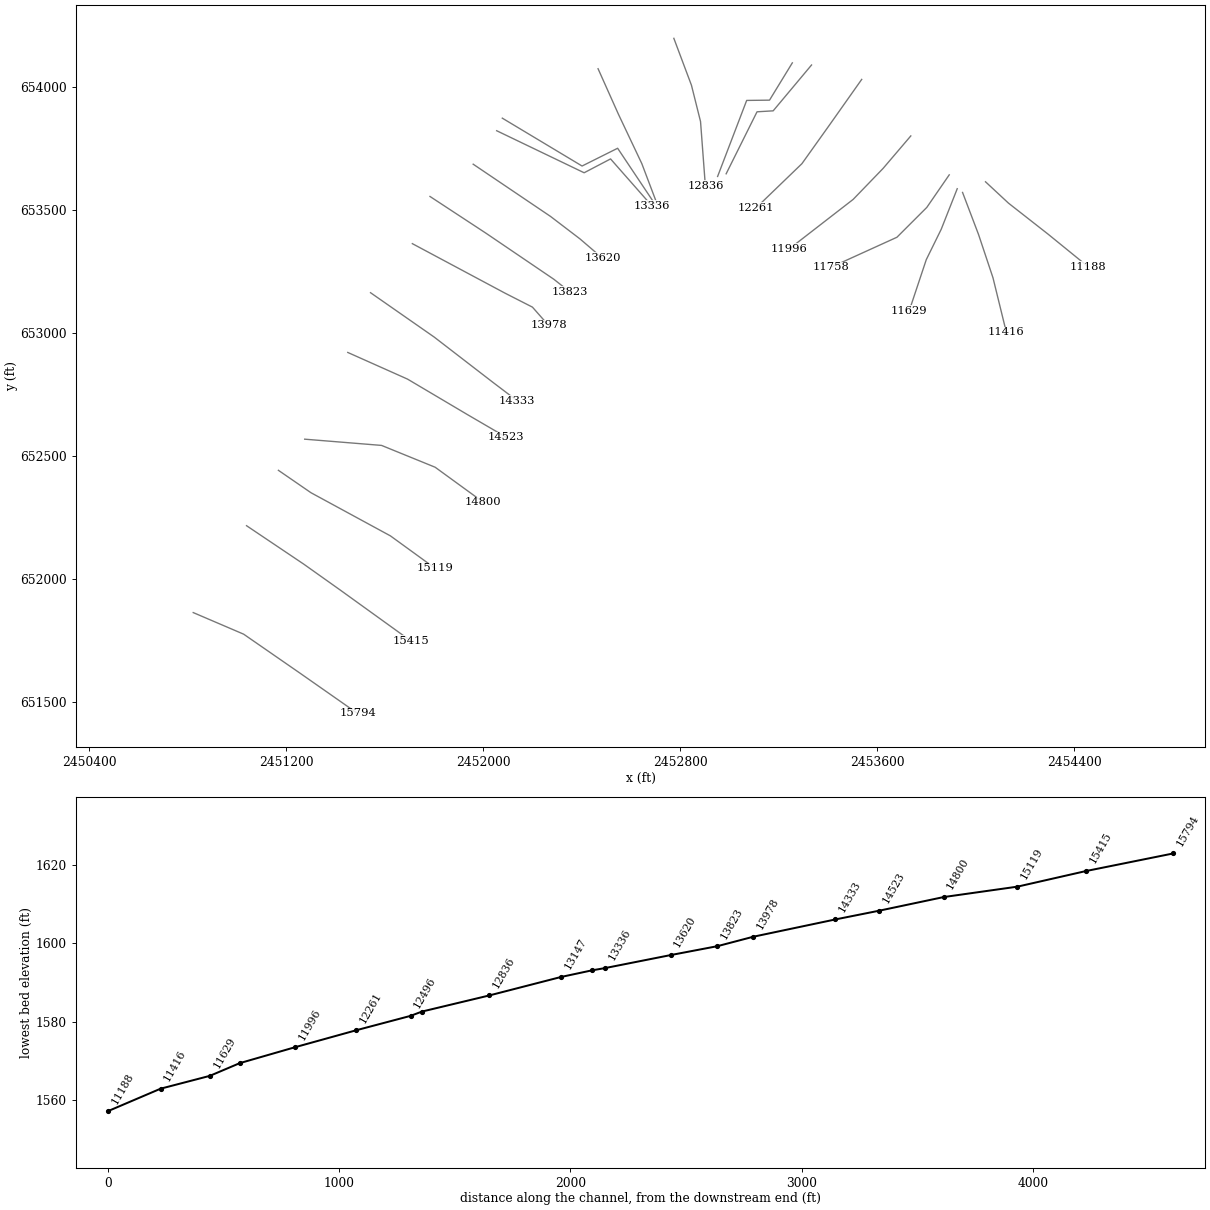
HEC-RAS study REEDSCK.prj: REEDSCK

--- REEDSCK.g01 (geometry) --- (continued)

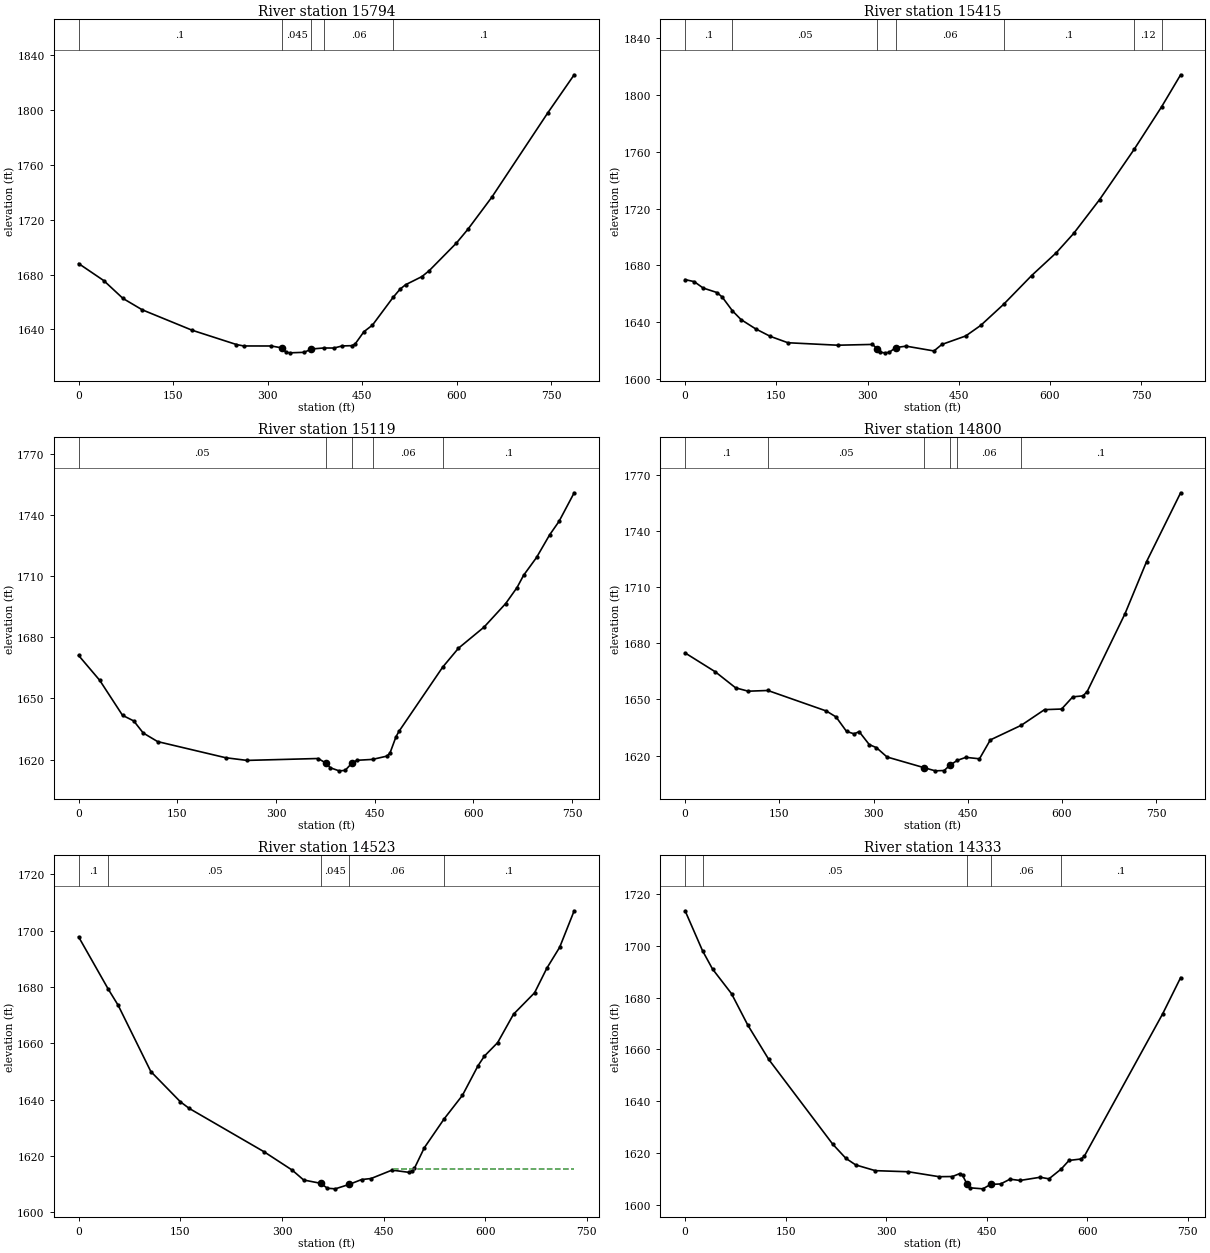
Type RM Length L Ch R = 1 ,15794   ,377.6,378.6,377.9
XS GIS Cut Line= 4
2450821.89245413651862.3784359382451026.70115794651774.603277164
2451254.91657075651616.6079913712451488.98366081651452.761028326
#Sta/Elev= 30
       0 1688.11    39.9 1675.67    70.3 1662.67   100.8 1654.37     180 1639.45
   250.4    1629   261.8 1627.96   305.6 1627.94   322.11626.589     329 1623.42
   334.8 1622.94   357.8 1623.32   369.3 1625.74  388.851626.487     405 1626.45
   418.1 1627.98   433.1 1628.17   438.3 1629.19   452.6 1638.39   466.1 1643.17
  498.87 1663.45   510.1 1669.52   518.7 1672.67   544.6 1678.61   556.1 1682.91
   599.2 1703.04   617.4 1713.08   655.5 1736.58   744.3 1798.17   786.1 1825.92
#Mann= 5 ,-1 , 0
       0      .1       0   322.1    .045       0   369.3      .1       0
  388.85     .06       0  498.87      .1       0
Bank Sta=322.1,369.3
XS Rating Curve= 0 ,0
Exp/Cntr(USF)=0,0
Exp/Cntr=0.3,0.1

Type RM Length L Ch R = 1 ,15415   ,271.2,295.8,296
XS GIS Cut Line= 4
2451038.40451244652215.4296301182451270.52104342652059.384903409
2451418.76353379 651954.054712882451705.49571912 651747.29544999
#Sta/Elev= 30
       0 1670.02      15 1668.59    29.6  1664.1    52.5  1660.9    61.2 1657.65
   77.861648.032      92 1641.86   115.9 1635.36   140.2 1630.03   169.1 1625.55
     251 1623.81   308.2 1624.37   315.51621.492   320.4 1618.79     329 1618.44
   335.8  1618.8   346.2 1622.11   363.4 1623.16   409.3 1619.77   422.3 1624.35
   461.5 1630.32   486.2 1637.76   523.71652.546     570  1672.9   610.6 1688.99
   639.1 1702.56   681.6 1726.31  738.791761.909  783.781791.799     815 1814.28
#Mann= 7 ,-1 , 0
       0      .1       0   77.86     .05       0   315.5    .045       0
   346.2     .06       0   523.7      .1       0  738.79     .12       0
  783.78      .1       0
Bank Sta=315.5,346.2
XS Rating Curve= 0 ,0
Exp/Cntr(USF)=0,0
Exp/Cntr=0.3,0.1

Type RM Length L Ch R = 1 ,15119   ,313,318.7,320
XS GIS Cut Line= 4
2451167.78968895 652440.533246672451299.99424908 652349.50715609
2451622.92014186652173.9568385422451804.97232302652041.752278413
#Sta/Elev= 30
       0 1671.06    32.1 1658.85    66.7 1641.71    83.8 1638.94    98.2 1633.02
   120.1 1628.81   223.5  1620.9   255.9 1619.59     364 1620.52   375.71618.289
   382.7 1615.96   395.8 1614.47   404.9 1614.67   415.51618.288   423.2 1619.65
  446.681620.076   468.7 1621.71   473.2 1623.21   482.3 1631.18   486.9 1633.87
  553.291665.348   577.3 1674.63   616.1 1684.96     649 1696.53   666.3 1704.39
   676.2 1710.37   695.9 1719.12   715.7 1730.17   730.1 1736.84   753.1 1750.86
#Mann= 5 ,-1 , 0
       0     .05       0   375.7    .045       0   415.5     .05       0
  446.68     .06       0  553.29      .1       0
Bank Sta=375.7,415.5
XS Rating Curve= 0 ,0
Exp/Cntr(USF)=0,0
Exp/Cntr=0.3,0.1

Type RM Length L Ch R = 1 ,14800   ,281.1,277.6,271.8
XS GIS Cut Line= 4
2451274.53956574652567.071603876 2451586.6734724652541.732319941
2451804.36095712652453.0448261662451999.01272917652311.375193254
#Sta/Elev= 30
       0  1674.8    48.1 1664.71    80.5 1656.14   100.5 1654.36  131.791654.741
   224.9 1643.78   240.3 1640.62     257  1632.9   269.1 1631.57   277.1 1632.78
   293.2 1625.85   304.7 1624.19   321.5 1619.22   379.8 1613.57   398.3 1611.82
   412.6    1612   421.31614.736  433.371617.416   447.1 1619.03   468.7 1618.25
     486 1628.34  535.281636.152   572.3 1644.51   599.5 1644.83   617.3 1651.35
   633.5 1651.86   640.2 1654.16   700.4 1695.72   734.7 1723.55     789 1760.34
#Mann= 6 ,-1 , 0
       0      .1       0  131.79     .05       0   379.8    .045       0
   421.3     .05       0  433.37     .06       0  535.28      .1       0
Bank Sta=379.8,421.3
XS Rating Curve= 0 ,0
Exp/Cntr(USF)=0,0
Exp/Cntr=0.3,0.1

Type RM Length L Ch R = 1 ,14523   ,193.5,190.4,178.6
XS GIS Cut Line= 4
2451449.53711218652919.5038661532451692.27335373652811.139472605
2451937.17688315652665.9311852512452093.22160986 652574.90509467
#Sta/Elev= 30
       0 1697.73   43.981679.091    58.3 1673.49   106.5 1649.98   150.3  1639.2
   163.4 1636.86   273.4 1621.54   315.2 1614.99     332  1611.5   357.1 1610.32
   367.1 1608.57   378.7 1608.36   398.9 1609.91   417.5 1611.65   431.5 1612.02
   462.4    1615   486.8 1614.23   492.6 1614.76   495.5 1615.65   510.1 1622.94
  539.451633.218   566.3 1641.52   589.4 1652.06   598.7 1655.44   618.3 1660.24
   641.7 1670.31   672.8 1677.92   690.9 1686.65   709.8 1694.05   731.2    1707
#Mann= 5 ,-1 , 0
       0      .1       0   43.98     .05       0   357.1    .045       0
   398.9     .06       0  539.45      .1       0
#XS Ineff= 2 , 0
                           464.9         1615.38
Permanent Ineff=
       F       F
Bank Sta=357.1,398.9
XS Rating Curve= 0 ,0
Exp/Cntr(USF)=0,0
Exp/Cntr=0.3,0.1

Type RM Length L Ch R = 1 ,14333   ,316.6,354.4,338.2
XS GIS Cut Line= 4
 2451541.9428921653162.3089762672451800.39641596652982.071650419
2452038.44571425652798.4336203092452137.06613782652723.618126561
#Sta/Elev= 30
       0 1713.63      26 1698.19    40.9 1691.12    69.3 1681.57    93.6 1669.41
   124.9 1656.13   220.4 1623.36   239.9 1617.92   254.6 1615.37   283.8 1613.15
   333.3 1612.72   378.9 1610.82   398.9 1610.88  409.84 1612.01     414 1611.35
     421 1607.83   425.1 1606.52   444.4 1606.12   455.9 1607.84   470.9 1608.01
   484.8 1609.85   499.9 1609.36   529.9  1610.6     543 1609.99   561.4 1613.81
   572.9  1617.1   590.9 1617.66   595.7 1618.71   712.7  1673.8   739.5 1687.79
#Mann= 5 ,-1 , 0
       0      .1       0      26     .05       0     421    .045       0
   455.9     .06       0   561.4      .1       0
#XS Ineff= 2 , 0
          409.84 1611.96
Permanent Ineff=
       F       F
Bank Sta=421,455.9
XS Rating Curve= 0 ,0
Exp/Cntr(USF)=0,0
Exp/Cntr=0.3,0.1

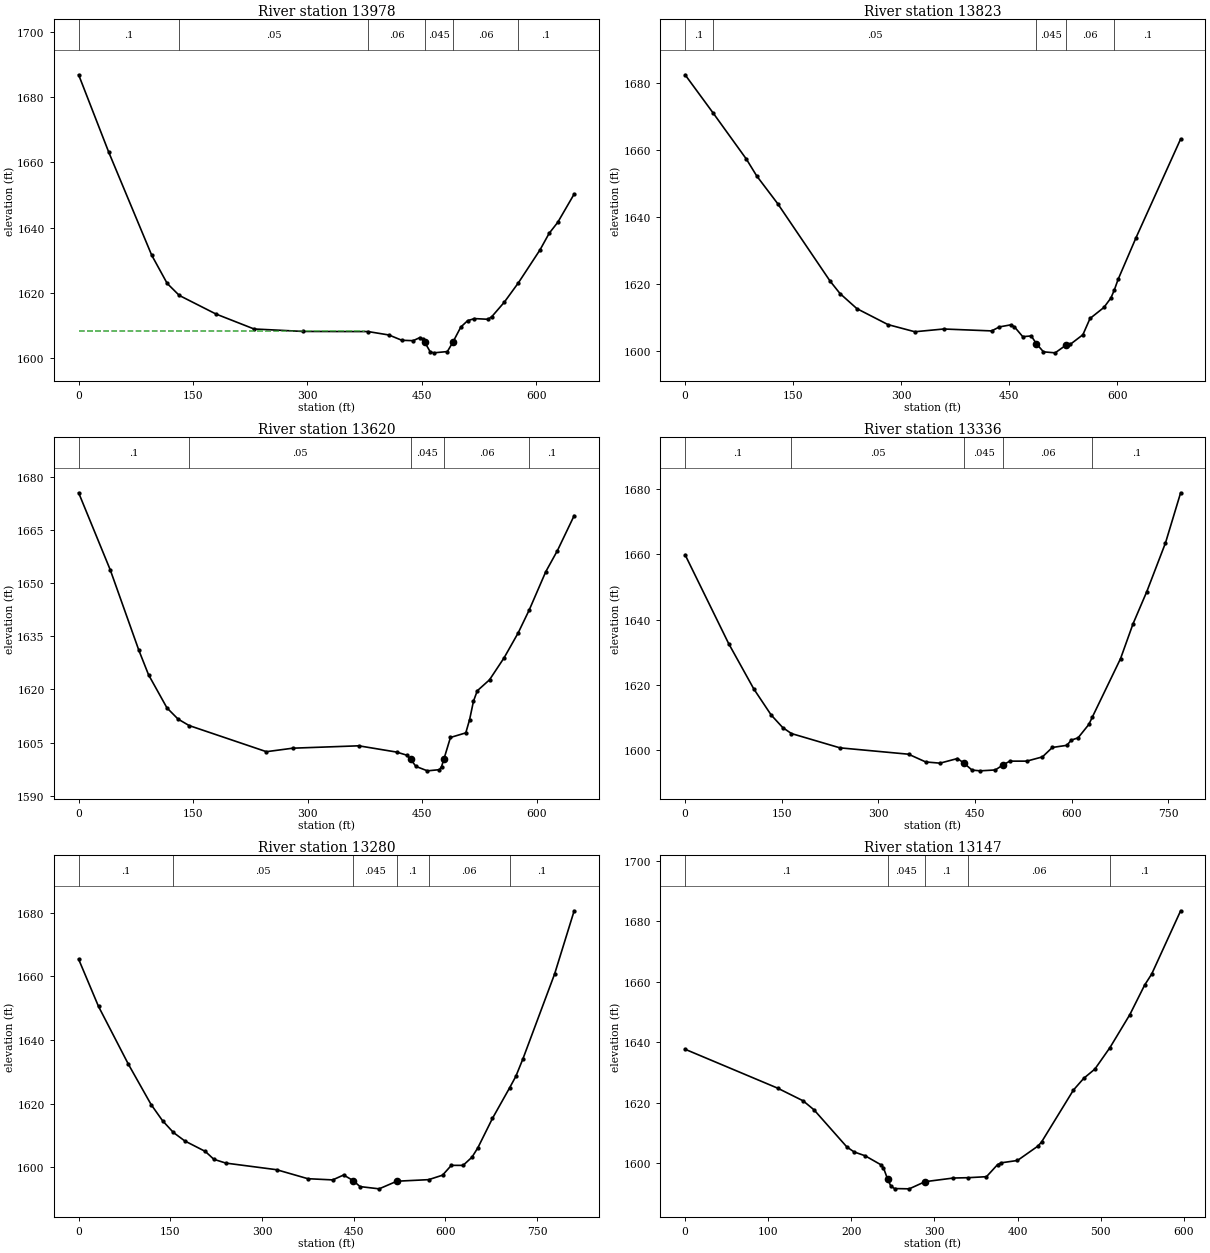
Type RM Length L Ch R = 1 ,13978   ,160.3,155.5,150.5
XS GIS Cut Line= 4
2451711.77894457653361.6305918292452088.88703411 653160.07281983
2452199.41871553653103.7233351852452264.43735166653030.035547572
#Sta/Elev= 30
       0  1686.8    39.6 1663.05    95.8 1631.61   116.1 1622.97     1321619.285
   180.2 1613.59   230.1 1609.02   294.3 1608.27   379.6 1608.23     407 1607.18
   423.9 1605.56   438.7 1605.44   447.7 1606.41   452.1 1605.83   454.11604.898
   461.1 1602.03   465.6 1601.72   483.6 1602.11   490.71604.926   501.2  1609.6
   510.1 1611.55   519.1  1612.2   536.9 1611.99   541.9  1612.8   558.1 1617.17
  576.811623.167   605.1 1633.23   617.1  1638.3   628.3 1641.63   649.9 1650.31
#Mann= 6 ,-1 , 0
       0      .1       0     132     .05       0   379.6     .06       0
   454.1    .045       0   490.7     .06       0  576.81      .1       0
#XS Ineff= 2 , 0
          373.92 1608.31
Permanent Ineff=
       F       F
Bank Sta=454.1,490.7
XS Rating Curve= 0 ,0
Exp/Cntr(USF)=0,0
Exp/Cntr=0.3,0.1

Type RM Length L Ch R = 1 ,13823   ,202.7,202.3,198.9
XS GIS Cut Line= 4
2451783.39289465653553.3899663142452011.24008016653403.758978818
2452286.69712532653216.7202444472452351.31050628653165.709680528
#Sta/Elev= 30
       0 1682.36    38.9 1670.95    85.1 1657.16    99.5 1652.12   128.4 1643.91
   201.3 1620.73   215.1 1617.01   238.5 1612.51   281.7 1607.74   318.9 1605.61
     359 1606.43   425.5 1605.86   436.4 1607.06   452.1 1607.67   457.2 1607.07
   468.7 1604.15   480.6 1604.35   487.8 1601.98   497.5 1599.61   513.7 1599.31
   529.1 1601.66   534.9 1601.88   552.2 1604.72   562.1 1609.57   581.4 1612.87
   591.1 1615.69   595.9 1618.12   601.1 1621.25     626 1633.72   687.9 1663.18
#Mann= 5 ,-1 , 0
       0      .1       0    38.9     .05       0   487.8    .045       0
   529.1     .06       0   595.9      .1       0
#XS Ineff= 2 , 0
          433.71 1606.09
Permanent Ineff=
       F       F
Bank Sta=487.8,529.1
XS Rating Curve= 0 ,0
Exp/Cntr(USF)=0,0
Exp/Cntr=0.3,0.1

Type RM Length L Ch R = 1 ,13620   ,228.2,284,329.3
XS GIS Cut Line= 4
2451958.84976186653684.5564846032452273.10650314653472.162273248
2452392.30733605653381.1361826682452483.33342663653303.113819313
#Sta/Elev= 30
       0 1675.47    41.5 1653.68    78.9 1631.04    91.6 1624.13   115.7  1614.8
   130.2 1611.65  144.691609.821     246 1602.44   280.6 1603.43     367  1604.1
   416.6 1602.33   429.9 1601.46   435.11600.287   441.8  1598.3   456.9 1597.04
   472.7 1597.37   475.5 1598.26   478.4 1600.25   487.1 1606.45   507.2 1607.75
   512.2 1611.48   517.3  1616.7   522.3 1619.63   538.3 1622.72   557.3 1628.89
   575.8 1635.93  590.361642.439     612 1653.21   627.3 1659.18   649.2 1669.03
#Mann= 5 ,-1 , 0
       0      .1       0  144.69     .05       0   435.1    .045       0
   478.4     .06       0  590.36      .1       0
#XS Ineff= 2 , 0
           366.9 1604.07
Permanent Ineff=
       F       F
Bank Sta=435.1,478.4
XS Rating Curve= 0 ,0
Exp/Cntr(USF)=0,0
Exp/Cntr=0.5,0.3

Type RM Length L Ch R = 1 ,13336   ,57,56,46.2
XS GIS Cut Line= 4
2452054.19297349653820.5853187292452409.40130681653649.751985371
2452516.69297349653706.0019853862452684.40130684653515.376985371
#Sta/Elev= 30
       0 1659.85    67.6 1632.67   106.6  1618.8   133.6 1610.81   151.5 1606.97
  165.051605.132   240.3 1600.76   346.8 1598.81   373.5 1596.44   395.7 1596.07
   422.8 1597.49   432.6 1596.12   445.4 1593.95   458.2 1593.72   481.5 1593.99
   493.8 1595.57   504.1 1596.69   530.3 1596.69   554.7 1597.99     570 1600.87
   592.6 1601.53   599.4 1603.12     610 1603.82   626.7 1607.92  631.931610.092
   675.9 1628.05   695.3 1638.72   716.6 1648.54   745.7 1663.49   769.2 1678.82
#Mann= 5 ,-1 , 0
       0      .1       0  165.05     .05       0   432.6    .045       0
   493.8     .06       0  631.93      .1       0
#XS Ineff= 2 , 0
             410 1594.39   515.8         1594.39
Permanent Ineff=
       F       F
Bank Sta=432.6,493.8
XS Rating Curve= 0 ,0
Exp/Cntr(USF)=0,0
Exp/Cntr=0.5,0.3

Type RM Length L Ch R = 1 ,13280   ,197,133.1,63.4
XS GIS Cut Line= 4
2452077.10964012653871.6269853862452401.03151512653677.128721491
2452545.47595957653749.3509437142452696.03151515653523.795388162
#Sta/Elev= 30
       0  1665.4    32.5 1650.55    81.2 1632.42   118.5 1619.68   137.2  1614.6
  154.871610.903   173.7 1608.21   207.2 1604.92   221.2 1602.44   240.8 1601.25
   323.8 1599.17   374.9 1596.34   415.5 1595.96   433.4  1597.5     449 1595.75
   460.2 1593.86   491.5 1593.15   520.5 1595.55  572.481596.039   595.2 1597.45
   609.6 1600.54   628.8 1600.53   643.3  1603.1   652.9 1606.04   676.9 1615.34
  704.881624.922   715.1 1628.55   726.6 1634.01   778.5 1660.75   810.5 1680.64
#Mann= 6 ,-1 , 0
       0      .1       0  154.87     .05       0     449    .045       0
   520.5      .1       0  572.48     .06       0  704.88      .1       0
Bank Sta=449,520.5
XS Rating Curve= 0 ,0
Exp/Cntr(USF)=0,0
Exp/Cntr=0.5,0.3

Type RM Length L Ch R = 1 ,13147   ,316.7,311.1,301.3
XS GIS Cut Line= 4
2452465.99512366654072.5010135052452548.35206276653888.281544473
2452643.71272908653686.7237724742452704.39678947653526.344470022
#Sta/Elev= 30
       0 1637.67   111.3  1624.8     142  1620.6   155.1 1617.62   194.6 1605.34
   203.3 1603.69   216.6 1602.41   235.4 1599.47   238.7 1598.41   243.7 1594.63
   247.6 1592.36     252 1591.56   269.7 1591.47   288.7 1593.84   322.8 1595.05
  340.421595.158   362.6 1595.49   375.9 1599.48   380.3 1600.08   399.9 1600.86
   424.6 1605.64   428.9 1606.99   467.2 1624.16   479.7 1628.07     493  1631.1
  511.161638.221   535.1 1649.14   552.9 1658.91   561.4 1662.58   596.2  1683.5
#Mann= 5 ,-1 , 0
       0      .1       0   243.7    .045       0   288.7      .1       0
  340.42     .06       0  511.16      .1       0
Bank Sta=243.7,288.7
XS Rating Curve= 0 ,0
Exp/Cntr(USF)=0,0
Exp/Cntr=0.3,0.1

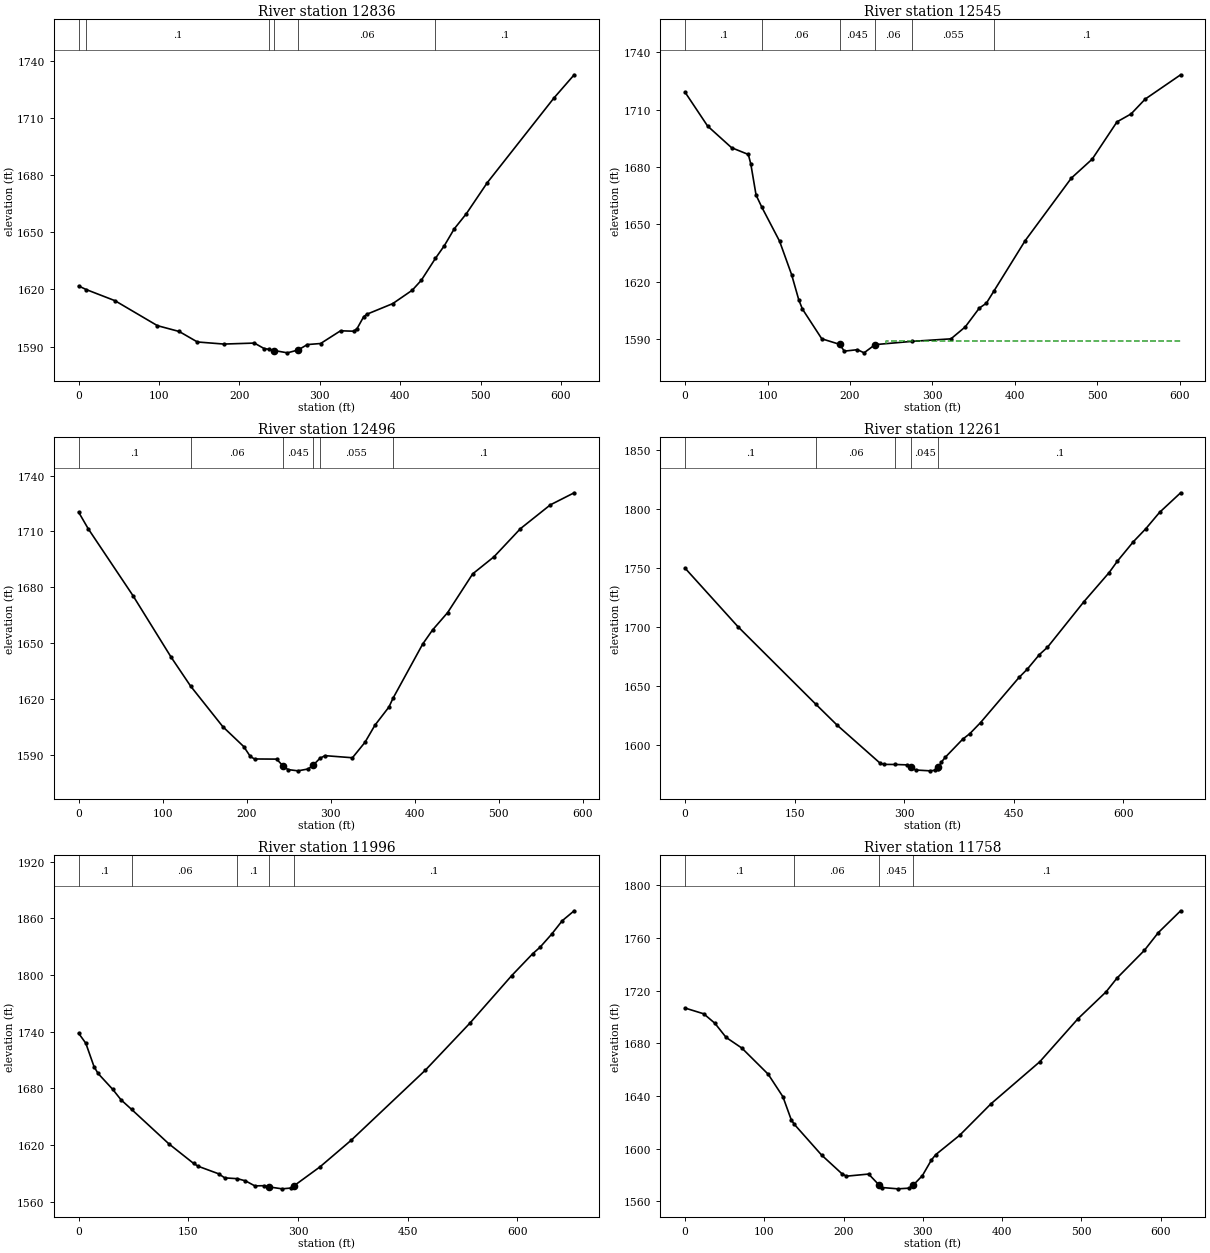
Type RM Length L Ch R = 1 ,12836   ,317.7,290.6,243.3
XS GIS Cut Line= 4
2452773.75000134 654196.036422152452845.27050108654005.315089505
2452882.11439489 653857.939514282452901.61998572653597.864969764
#Sta/Elev= 30
       0 1621.82    9.381619.934    45.2 1614.09      98    1601   125.1 1597.94
   147.7 1592.45   180.6 1591.35   218.6 1591.87   230.9 1588.95  237.071588.616
   243.3 1587.96   259.7 1586.75   272.9 1588.23   284.5 1591.09     301 1591.64
   325.8 1598.31   342.3 1598.09   346.4  1599.5   354.6 1605.72   358.7 1607.02
   390.7 1612.55     415 1619.59   426.2 1624.76  443.76 1636.24   454.9 1642.93
   467.2 1651.74   482.2 1659.64   508.3 1675.95   591.3 1720.38   616.4 1732.52
#Mann= 6 ,-1 , 0
       0      .1       0    9.38      .1       0  237.07     .06       0
   243.3    .045       0   272.9     .06       0  443.76      .1       0
Bank Sta=243.3,272.9
XS Rating Curve= 0 ,0
Exp/Cntr(USF)=0,0
Exp/Cntr=0.5,0.3

Type RM Length L Ch R = 1 ,12545   ,48.6,49.5,58.8
XS GIS Cut Line= 4
2453254.88790873654096.341180101 2453162.2722559653944.823165953
2453069.49447811653943.7120548342452951.46760675653634.708863571
#Sta/Elev= 30
       0 1719.08    27.3  1701.4    56.4 1690.05    76.7 1686.52    79.7 1681.54
    86.1 1665.23   93.211658.796   114.6 1641.11   129.2  1623.6   137.9 1610.39
   142.3 1605.59   165.8    1590   187.41587.112   193.1 1583.54   209.1  1584.3
   217.1 1582.65   230.4 1586.95  274.771588.636   322.5 1589.98   339.8 1596.22
   356.9 1606.08   365.4 1608.62  374.511614.934   412.5 1641.38   468.6 1674.18
   493.9 1684.11   523.9 1703.59     541 1707.75   558.1 1715.51   601.1 1728.24
#Mann= 6 ,-1 , 0
       0      .1       0   93.21     .06       0   187.4    .045       0
   230.4     .06       0  274.77    .055       0  374.51      .1       0
#XS Ineff= 2 , 0
             173  1588.7     244          1588.7
Permanent Ineff=
       F       F
Bank Sta=187.4,230.4
XS Rating Curve= 0 ,0
Exp/Cntr(USF)=0,0
Exp/Cntr=0.5,0.3

Type RM Length L Ch R = 1 ,12496   ,224.5,234.6,249.7
XS GIS Cut Line= 4
2453332.91027203654087.6720286012453177.08707067653901.378721505
2453111.53151515653897.4898325952452986.14421269653645.545302927
#Sta/Elev= 30
       0 1720.32    11.4 1711.44    64.6 1675.61     110 1642.61  133.311627.013
   171.7 1605.23   196.6 1594.56   204.4 1589.26   209.4 1587.92   235.7 1587.84
   242.9 1584.41   249.2 1582.23   261.2 1581.55   273.3 1582.56   279.61584.745
  287.321588.289   293.3  1589.7     326 1588.57   340.9 1596.84   352.8 1606.04
   369.5 1615.82  374.251620.443   409.7 1649.61   421.4 1657.14   439.3 1666.43
   469.2 1687.24   494.6 1696.42     526 1711.47   561.6 1724.24     590 1730.73
#Mann= 6 ,-1 , 0
       0      .1       0  133.31     .06       0   242.9    .045       0
   279.6     .06       0  287.32    .055       0  374.25      .1       0
Bank Sta=242.9,279.6
XS Rating Curve= 0 ,0
Exp/Cntr(USF)=0,0
Exp/Cntr=0.5,0.3

Type RM Length L Ch R = 1 ,12261   ,268.1,265.5,262.7
XS GIS Cut Line= 4
2453536.63533192654029.1552560862453406.59805966653844.935787054
2453293.89909037653686.7237724742453107.51233347653506.838879184
#Sta/Elev= 30
       0 1749.98    72.6  1700.2   179.1 1634.45   208.4 1616.61     267 1584.46
   272.2 1583.36  288.111583.294   304.3 1582.95   309.5 1581.01   315.8  1578.6
   335.5 1577.89   342.4 1578.37   345.9  1579.6   347.11580.937   350.8  1585.1
   356.2 1589.27   380.2 1604.73   390.1  1609.5   404.7 1618.86   457.5 1657.25
   468.6 1664.14   485.3  1676.6   496.4 1682.84   546.4 1721.61   580.8 1746.23
   592.3 1756.08   614.2 1772.59   631.2  1783.6   649.9 1797.38   678.8 1814.04
#Mann= 5 ,-1 , 0
       0      .1       0   179.1     .06       0  288.11      .1       0
   309.5    .045       0   347.1      .1       0
Bank Sta=309.5,347.1
XS Rating Curve= 0 ,0
Exp/Cntr(USF)=0,0
Exp/Cntr=0.3,0.1

Type RM Length L Ch R = 1 ,11996   ,238.3,238,237.4
XS GIS Cut Line= 4
2453736.02581604653799.4227417642453623.32684675653667.218181635
2453501.95872598653541.5154851192453241.88418147 653339.95771312
#Sta/Elev= 30
       0 1738.19     9.8 1727.67    21.1 1702.81    26.6 1695.64    46.7 1678.77
      58 1667.75    72.31657.709   123.3 1621.23   157.3 1600.39   163.6 1597.39
   191.3  1589.5   199.8 1585.15  217.12 1584.29   228.1    1582   240.9 1576.68
   253.6 1576.88   260.9 1575.52   278.2 1573.55   290.3  1574.4   294.71576.901
     330 1596.82   372.6 1624.96     474 1699.13   535.1 1749.07   592.1 1799.25
   620.6 1822.27   630.9 1829.32   646.6    1843   661.2 1857.33   677.5 1867.86
#Mann= 5 ,-1 , 0
       0      .1       0    72.3     .06       0  217.12      .1       0
   260.9    .045       0   294.7      .1       0
Bank Sta=260.9,294.7
XS Rating Curve= 0 ,0
Exp/Cntr(USF)=0,0
Exp/Cntr=0.3,0.1

Type RM Length L Ch R = 1 ,11758   ,121.1,129.4,136.3
XS GIS Cut Line= 4
2453892.07054275653641.2107271842453801.04445217653509.006167055
 2453679.6763314653387.6380462812453413.09992327653266.269925507
#Sta/Elev= 30
       0 1706.82    23.5 1702.45    37.6 1695.26    51.7 1684.54    71.6 1676.43
   104.8 1656.58   123.4 1639.46   133.9 1621.96  137.921618.413   172.1 1595.22
   197.6 1581.12   203.4 1579.12   231.5 1580.74   245.11572.157   248.6 1570.51
   268.3 1569.51   282.3 1570.01   287.41572.101   299.3 1579.52   310.7  1591.4
   316.2  1595.5   346.4 1610.22   385.9 1634.13   447.4 1666.02   495.8 1698.85
     531  1719.1   544.8 1729.57   579.3  1750.6   596.9  1764.1   625.1 1780.71
#Mann= 4 ,-1 , 0
       0      .1       0  137.92     .06       0   245.1    .045       0
   287.4      .1       0
Bank Sta=245.1,287.4
XS Rating Curve= 0 ,0
Exp/Cntr(USF)=0,0
Exp/Cntr=0.3,0.1

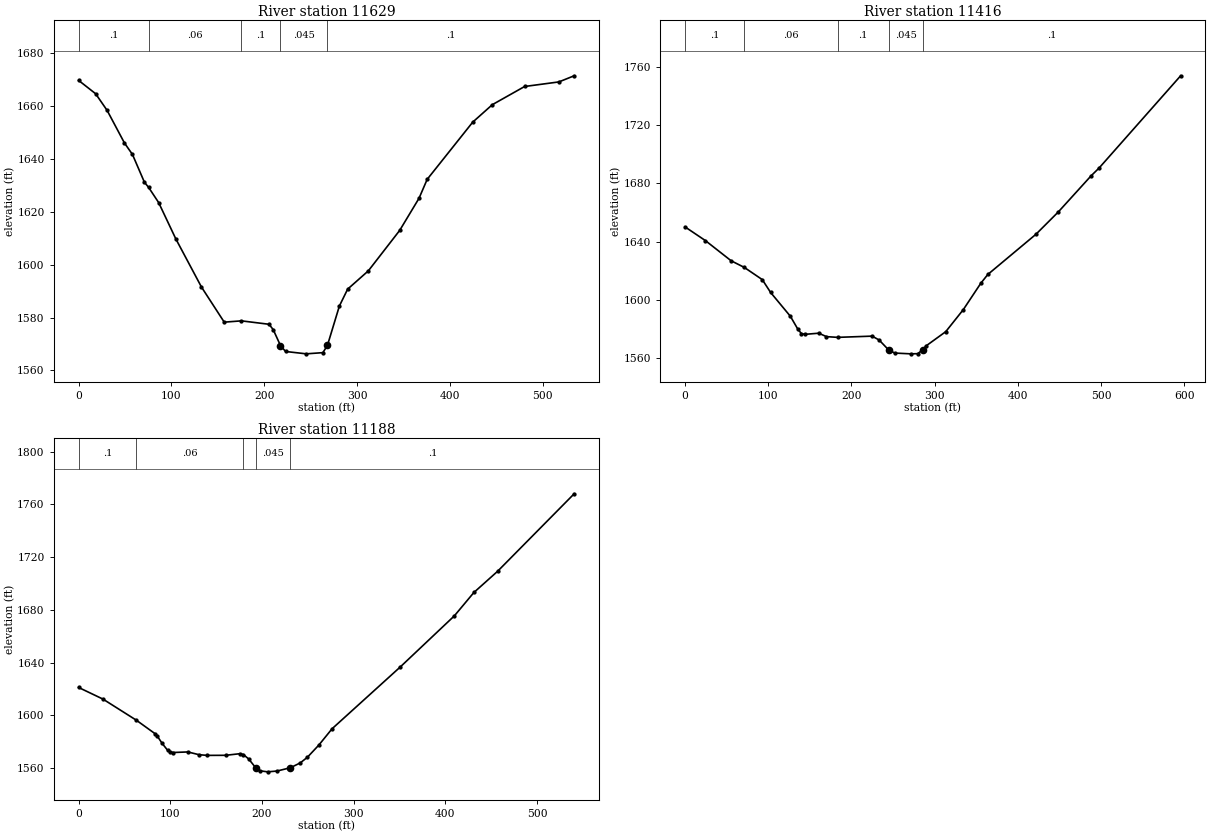
Type RM Length L Ch R = 1 ,11629   ,195.5,212.8,229.5
XS GIS Cut Line= 4
2453924.57986082653584.8612425382453859.56122469653420.147364345
 2453798.8771643653296.6119557012453729.52395243653088.552320088
#Sta/Elev= 30
       0 1669.58    18.3 1664.55    30.7 1658.25    49.4 1645.92      58 1641.61
    70.9  1631.1   75.411629.162    86.2 1623.44   104.7 1609.72   132.4 1591.49
   156.9 1578.24   175.41578.732   205.2 1577.44   209.7 1575.41   217.51569.407
     223 1567.16   245.3 1566.27   263.2 1566.72   268.1 1569.44     281 1584.35
   289.9 1590.72   312.2 1597.63     346 1612.92   366.8 1625.04   375.6  1632.2
   424.7 1653.82   445.8 1660.41   480.6 1667.28   517.5 1669.01     534 1671.33
#Mann= 5 ,-1 , 0
       0      .1       0   75.41     .06       0   175.4      .1       0
   217.5    .045       0   268.1      .1       0
Bank Sta=217.5,268.1
XS Rating Curve= 0 ,0
Exp/Cntr(USF)=0,0
Exp/Cntr=0.3,0.1

Type RM Length L Ch R = 1 ,11416   ,215.8,228.2,238.6
XS GIS Cut Line= 4
2453946.25273953653569.6902274422454011.27137566653398.474485636
2454069.78814817653222.9241680882454123.97034495 653001.86080525
#Sta/Elev= 30
       0 1650.12    24.4 1640.75    55.3 1626.91   71.211622.324    92.8 1613.96
   102.8 1605.15   126.6 1588.77   135.6 1579.88   139.9 1576.88   144.2 1576.39
   160.7 1577.17     170 1574.81   183.41574.312   224.9 1575.16   233.3 1572.48
   244.61565.762     252 1563.54   271.3    1563   279.7 1563.11   285.51565.721
   289.9 1568.52   313.4 1578.23   334.5 1593.36   355.6  1611.5     364 1617.51
   421.8 1645.07   448.8 1660.47   488.1 1685.19   497.9 1690.67   595.8  1753.9
#Mann= 5 ,-1 , 0
       0      .1       0   71.21     .06       0   183.4      .1       0
   244.6    .045       0   285.5      .1       0
Bank Sta=244.6,285.5
XS Rating Curve= 0 ,0
Exp/Cntr(USF)=0,0
Exp/Cntr=0.3,0.1

Type RM Length L Ch R = 1 ,11188   ,201.6,221.1,255.8
XS GIS Cut Line= 4
2454039.44611798653613.0359848612454132.63949643653526.344470022
2454293.01879888653400.641773507 2454455.5653892653268.437213378
#Sta/Elev= 30
       0  1621.2    26.5 1612.41   62.991596.384    83.1 1586.31    85.4 1584.75
    91.2 1578.74    97.1 1573.58   100.1 1572.41   102.8 1571.91   119.2 1572.34
   131.2 1570.27   140.1 1569.73   160.4 1569.79   175.7 1570.99  179.631570.396
   185.4  1567.1   193.11560.416   197.7 1558.05   206.2 1557.26   216.4 1557.86
   231.11560.388   241.8 1564.04   249.6 1568.33   262.1 1577.59   276.5 1589.92
   350.6 1636.56   409.9 1675.49   431.2  1693.2     457 1709.22   540.6 1768.01
#Mann= 5 ,-1 , 0
       0      .1       0   62.99     .06       0  179.63      .1       0
   193.1    .045       0   231.1      .1       0
Bank Sta=193.1,231.1
XS Rating Curve= 0 ,0
Exp/Cntr(USF)=0,0
Exp/Cntr=0.5,0.3