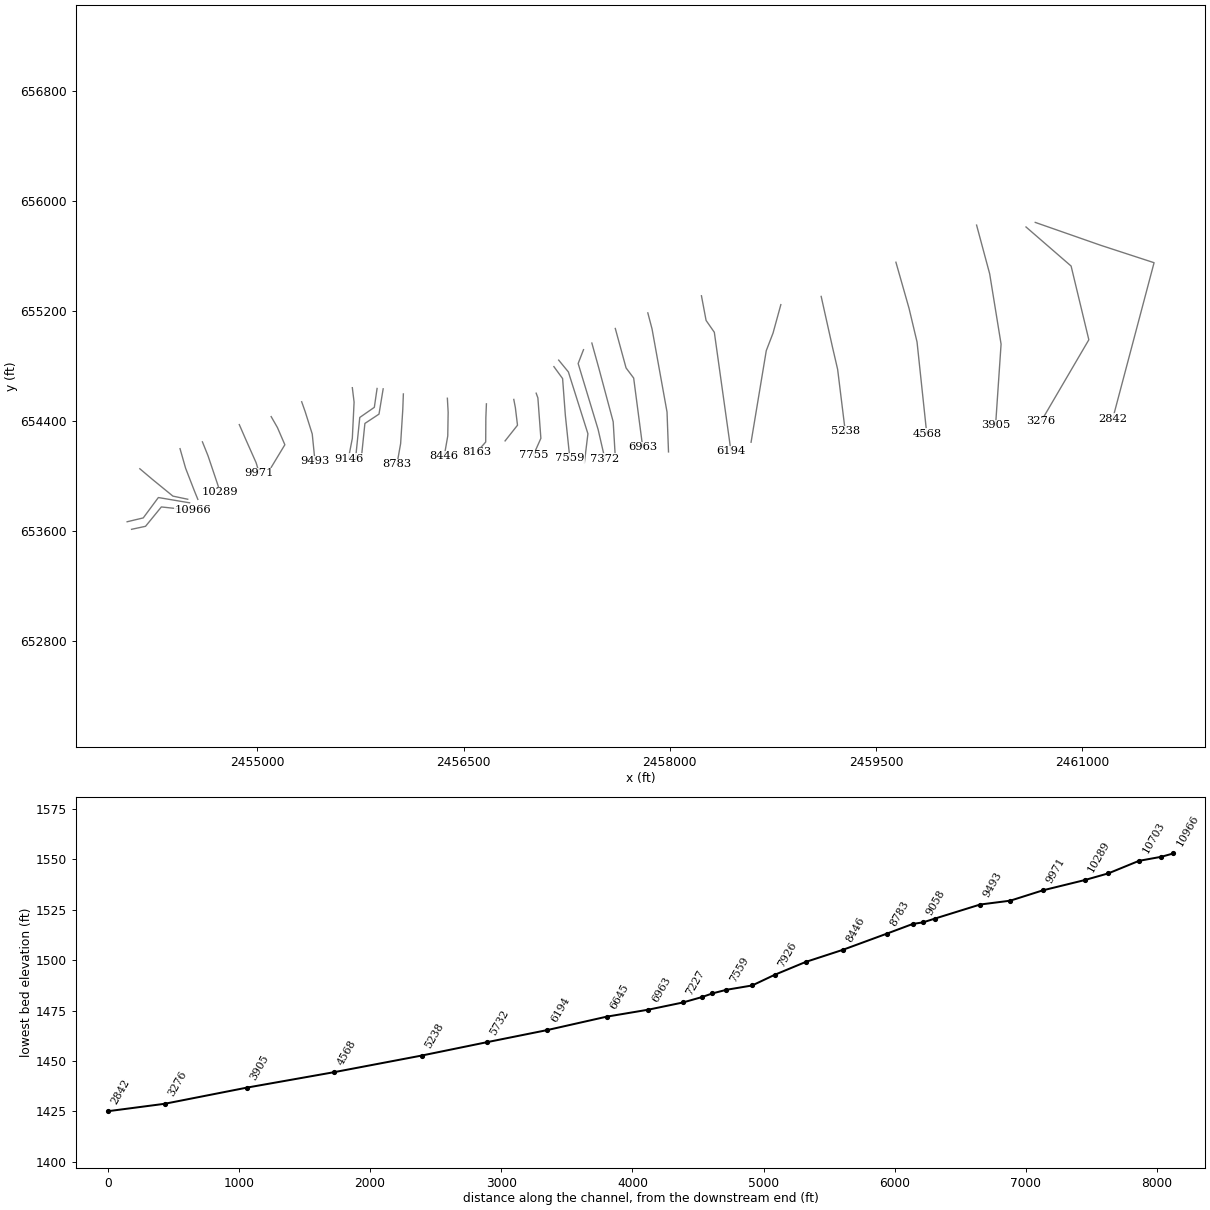
HEC-RAS study REEDSCK.prj: REEDSCK

--- REEDSCK.g01 (geometry) --- (continued)

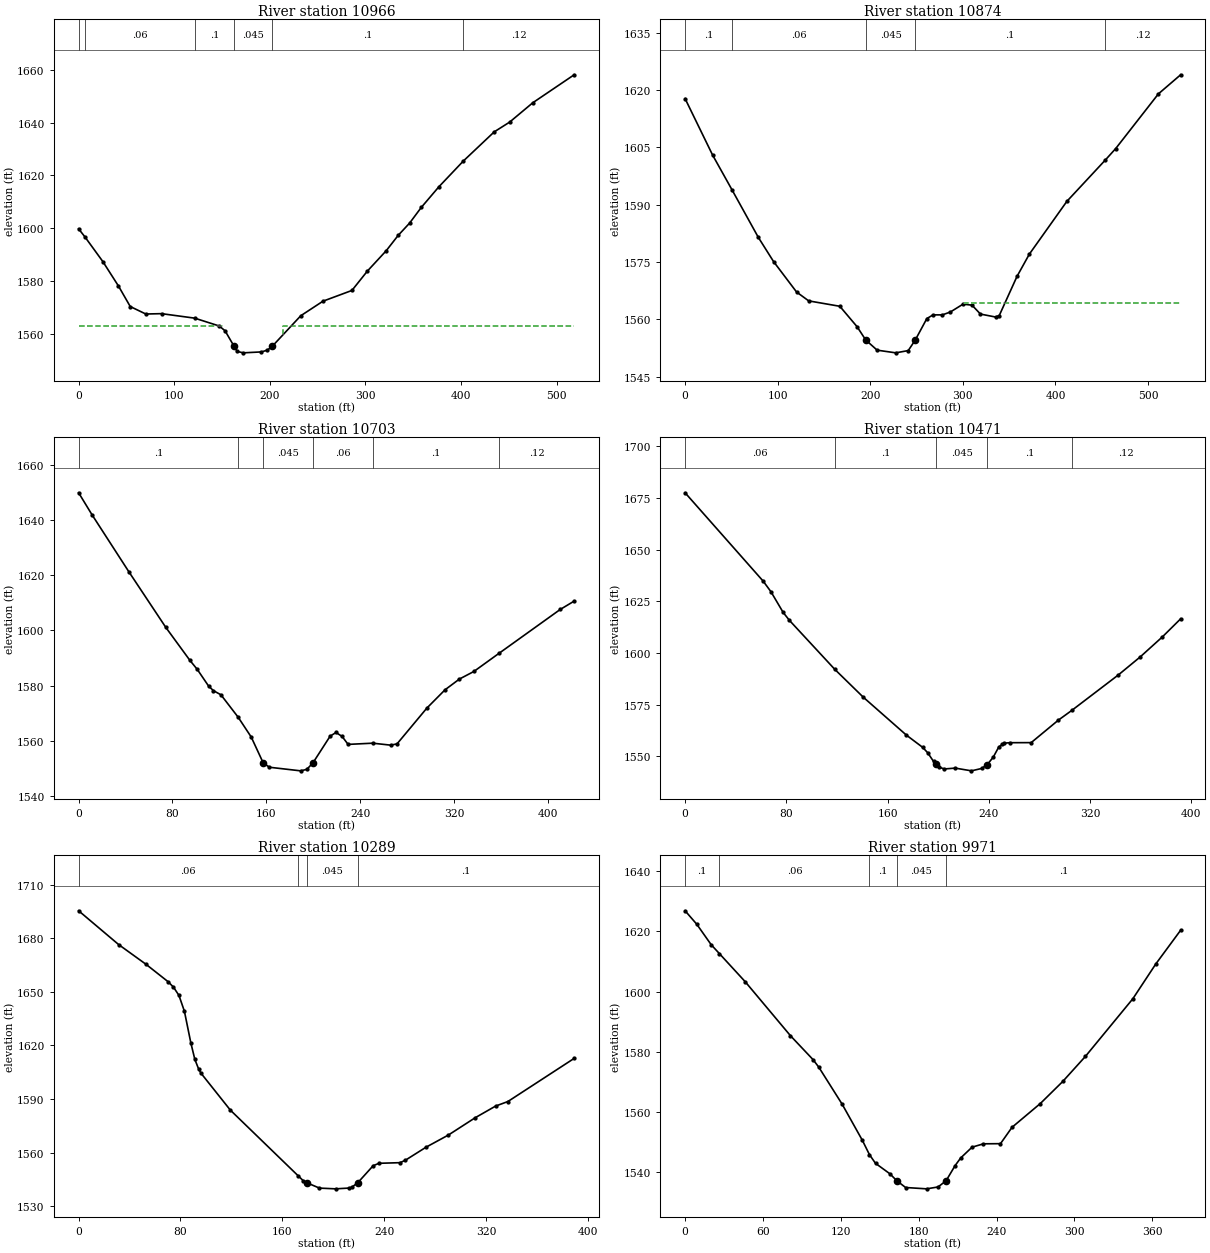
Type RM Length L Ch R = 1 ,10966   ,76.3,92.3,87.7
XS GIS Cut Line= 4
2454085.96748138 653611.553930132454187.55497425653633.322678602
2454302.61835903653774.3012401342454533.78173566653749.422670452
#Sta/Elev= 30
       0 1599.79    6.691596.707    25.3 1587.43    41.7 1578.15      54  1570.4
    70.3 1567.57    86.7 1567.71  121.391566.008   147.1 1563.04   153.2 1561.22
   162.5 1555.43   165.9 1553.42   172.2 1552.88   191.2 1553.23   197.5 1553.91
   202.71555.416   232.4 1566.92   255.6 1572.42   285.9 1576.49   302.1 1583.83
   321.8 1591.53   334.3 1597.33   346.3    1602   358.4 1607.88   376.8 1615.69
   402.41625.444   434.8 1636.51   450.9 1640.19   475.1 1647.51   518.4  1658.1
#Mann= 6 ,-1 , 0
       0      .1       0    6.69     .06       0  121.39      .1       0
   162.5    .045       0   202.7      .1       0   402.4     .12       0
#XS Ineff= 2 , 0
             150 1562.91     214         1562.91
Permanent Ineff=
       F       F
Bank Sta=162.5,202.7
XS Rating Curve= 0 ,0
Exp/Cntr(USF)=0,0
Exp/Cntr=0.5,0.3

Type RM Length L Ch R = 1 ,10874   ,211.4,171.1,143.7
XS GIS Cut Line= 4
2454053.83266221653666.4941048452454170.96926113653694.482495737
2454280.84961056 653842.717306762454507.86655891653804.362845166
#Sta/Elev= 30
       0 1617.71    29.7 1602.95   50.65 1593.86    79.1 1581.41    95.5  1575.1
   120.4 1567.12   133.5  1564.8   167.1 1563.39   185.7 1558.06   195.11554.572
   207.4 1551.91   227.5 1551.21     241  1551.8   248.61554.564   261.1 1560.18
   267.8 1561.14   277.8 1561.14   286.4 1561.88   300.2 1563.95   309.9 1563.68
     319 1561.35   335.3 1560.58   339.3 1560.97   358.5 1571.22   371.8 1577.03
   412.3 1590.83  453.761601.622   465.1 1604.66   511.2 1618.96   535.2 1623.95
#Mann= 5 ,-1 , 0
       0      .1       0   50.65     .06       0   195.1    .045       0
   248.6      .1       0  453.76     .12       0
#XS Ineff= 2 , 0
                          301.19         1564.27
Permanent Ineff=
       F       F
Bank Sta=195.1,248.6
XS Rating Curve= 0 ,0
Exp/Cntr(USF)=0,0
Exp/Cntr=0.5,0.3

Type RM Length L Ch R = 1 ,10703   ,246.8,231.8,225.3
XS GIS Cut Line= 4
2454146.09069145654052.1119349182454239.38532776653973.329797591
2454386.58353171653853.083377461  2454494.390667653830.278021919
#Sta/Elev= 30
       0 1649.81    11.3 1641.93    42.7  1621.3    74.2 1601.16    94.9 1589.13
   101.1 1585.91   110.8 1579.85   114.9  1578.2   121.3  1576.7  135.971568.592
   147.1 1561.43   157.31552.087   162.6 1550.48   189.2 1549.18   194.5 1549.71
   199.71552.039   214.4 1561.74   219.4 1563.06   224.6 1561.62   229.7 1558.75
   250.7 1559.19   265.9 1558.48   271.4 1558.93   296.8 1571.87   312.3  1578.5
   324.6  1582.4   336.9 1585.14  358.321591.703   410.5 1607.58   422.4 1610.61
#Mann= 6 ,-1 , 0
       0      .1       0  135.97     .06       0   157.3    .045       0
   199.7     .06       0   250.7      .1       0  358.32     .12       0
Bank Sta=157.3,199.7
XS Rating Curve= 0 ,0
Exp/Cntr(USF)=0,0
Exp/Cntr=0.3,0.1

Type RM Length L Ch R = 1 ,10471   ,182.5,182.4,180.9
XS GIS Cut Line= 4
2454438.41388521  654198.27353182454478.84156095654056.258363198
2454543.11119929653890.4012319842454567.98976897653829.241414849
#Sta/Elev= 30
       0 1677.53    61.7 1634.78    67.8  1629.7    77.5 1619.64    82.5 1615.77
  118.281592.116   140.8 1578.64   174.9 1560.28   187.7 1554.39   191.7 1551.77
   196.3 1547.59   198.6 1546.08   200.6  1544.8   204.9 1543.92   213.5 1544.33
   226.3 1543.01   234.3 1544.15   238.81546.057   243.5 1549.61   247.8 1554.45
   250.7 1555.85   252.1 1556.39   256.4 1556.62   273.5 1556.66     295 1567.55
   305.6 1572.25   342.3 1589.37   359.5 1598.04   377.1 1607.77   391.6 1616.55
#Mann= 5 ,-1 , 0
       0     .06       0  118.28      .1       0   198.6    .045       0
   238.8      .1       0   305.6     .12       0
Bank Sta=198.6,238.8
XS Rating Curve= 0 ,0
Exp/Cntr(USF)=0,0
Exp/Cntr=0.3,0.1

Type RM Length L Ch R = 1 ,10289   ,311.6,318,317.1
XS GIS Cut Line= 4
2454601.16119522654248.0306711652454641.58887095654147.479785366
2454708.96833051653947.4146208392454730.73707898653881.071768353
#Sta/Elev= 30
       0 1695.43    31.4 1676.52      53 1665.41    70.2 1655.74    74.5 1652.66
    78.8 1648.03    83.1 1639.13    88.2 1621.26    91.3 1612.15    94.3 1606.74
    96.1 1604.45   119.2 1583.74  172.391546.993   176.5 1544.16   179.6 1542.95
   189.2 1540.05   201.9 1539.64   212.3 1540.07   214.5 1540.53   219.21542.987
   231.4 1552.61     236 1553.95   252.5  1554.3   256.7 1555.67   272.9 1562.96
   290.5 1569.79   311.6  1579.5   327.6 1586.02   337.2 1588.55   389.3 1612.73
#Mann= 4 ,-1 , 0
       0     .06       0  172.39      .1       0   179.6    .045       0
   219.2      .1       0
Bank Sta=179.6,219.2
XS Rating Curve= 0 ,0
Exp/Cntr(USF)=0,0
Exp/Cntr=0.3,0.1

Type RM Length L Ch R = 1 ,9971    ,247.1,248.7,247.8
XS GIS Cut Line= 4
2454869.36514464654373.320774804 2454917.7117021654262.408084177
2454991.65349585654096.039048237  2455014.404817654020.675296913
#Sta/Elev= 30
       0 1626.84       9 1622.37    20.1 1615.58   26.441612.619    46.3 1603.31
    81.2 1585.37    98.6 1577.44     103 1574.95     121 1562.66   136.6 1550.65
  142.031545.925   146.7 1543.04   157.8 1539.56   163.11537.267   169.9 1535.01
   186.1 1534.57   194.9 1535.19   201.11537.261     208 1542.26   212.3  1544.8
   221.1  1548.4   229.9 1549.51     243 1549.56   251.9 1554.99   273.7 1562.88
     291 1570.21   308.4  1578.5     345 1597.66   362.7 1609.22   381.8 1620.38
#Mann= 5 ,-1 , 0
       0      .1       0   26.44     .06       0  142.03      .1       0
   163.1    .045       0   201.1      .1       0
Bank Sta=163.1,201.1
XS Rating Curve= 0 ,0
Exp/Cntr(USF)=0,0
Exp/Cntr=0.3,0.1

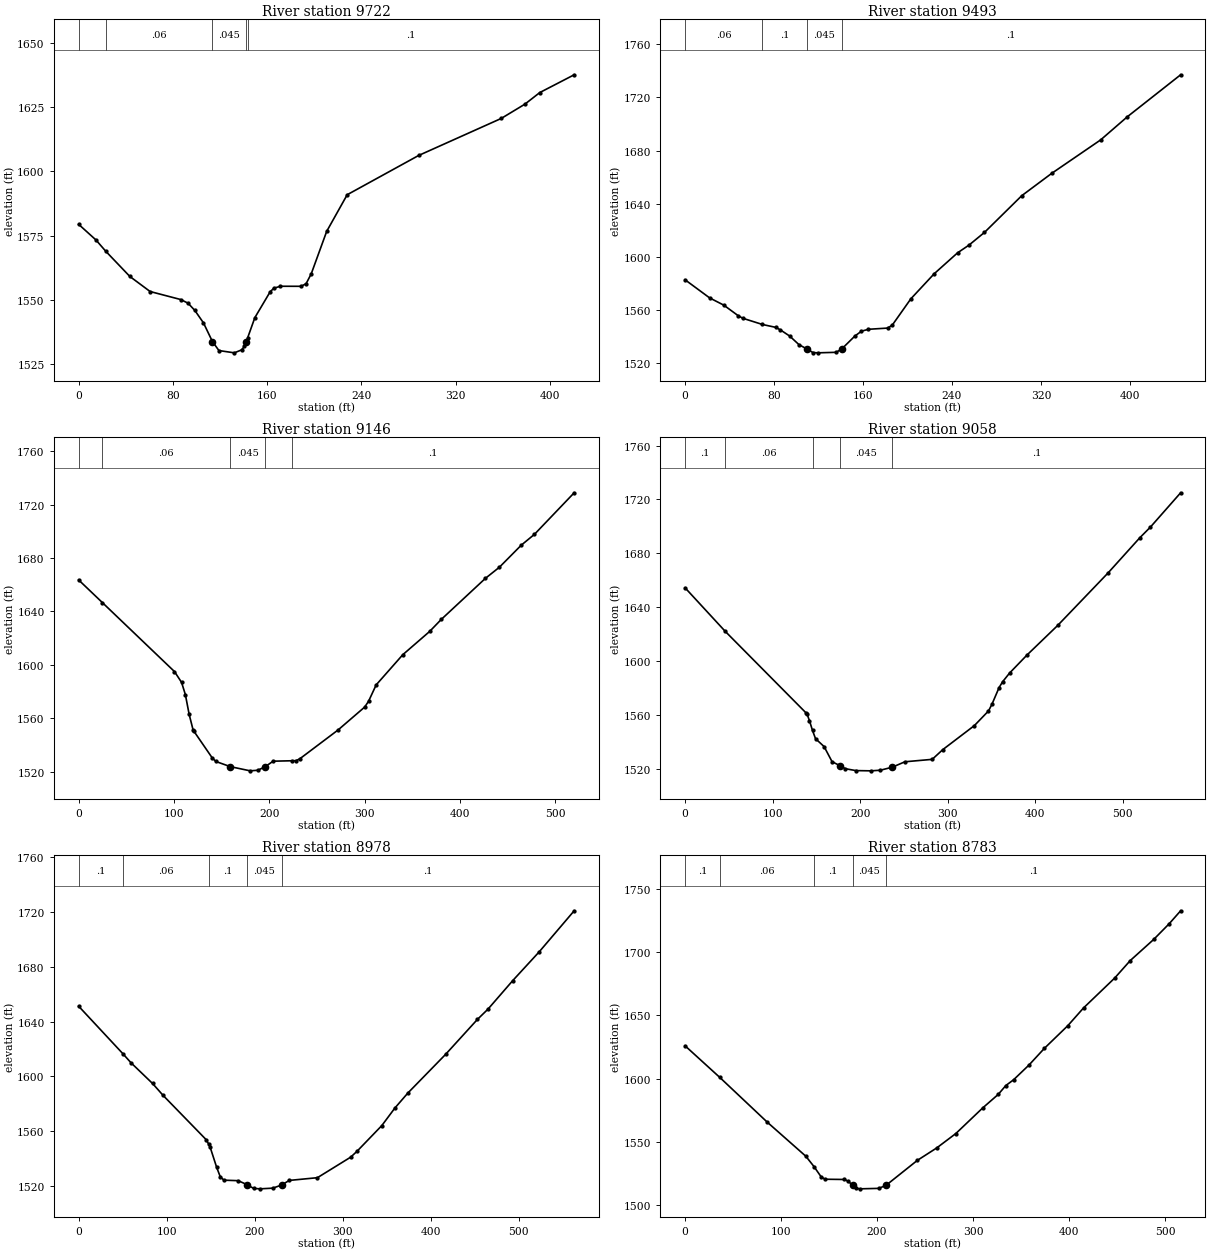
Type RM Length L Ch R = 1 ,9722    ,229.2,229.2,225.9
XS GIS Cut Line= 4
 2455101.1442289654431.6210352612455146.64687121654351.991411222
2455200.68125895654226.859144873 2455101.1442289654061.912066505
#Sta/Elev= 30
       0 1579.43    14.7 1573.35      231568.972    43.5 1559.14    60.7 1553.29
    86.7 1550.17    92.9 1548.75    98.7 1545.91     106 1541.08   113.61533.823
   119.1 1530.33   132.2 1529.44   138.3 1530.58   140.8 1531.93   142.31533.731
  143.481535.264   149.6 1543.13   162.6 1553.19   165.7 1554.57   171.3 1555.34
   188.8 1555.32   193.1 1556.33   197.5  1560.2   210.6  1576.7     228 1590.94
   288.7 1606.22   358.8 1620.62   378.9 1626.18   391.5 1630.68   420.7  1637.6
#Mann= 5 ,-1 , 0
       0      .1       0      23     .06       0   113.6    .045       0
   142.3     .06       0  143.48      .1       0
Bank Sta=113.6,142.3
XS Rating Curve= 0 ,0
Exp/Cntr(USF)=0,0
Exp/Cntr=0.3,0.1

Type RM Length L Ch R = 1 ,9493    ,351.4,346.5,339.4
XS GIS Cut Line= 4
2455322.96961016654539.6898107442455348.56484645654467.169974565
2455399.75531905654305.0668113412455419.66272506654107.414708814
#Sta/Elev= 30
       0 1582.59    22.1 1568.92    34.8 1563.49    47.5 1555.68    51.7 1553.65
   69.581548.906    81.4 1546.76    85.6 1544.88      94 1540.22   102.4 1533.71
   109.21530.605   114.9 1527.78   119.1 1527.54   135.9 1527.94     1411530.574
   152.7 1540.22   158.6 1543.86   164.9 1545.29   182.1  1546.2   186.3 1548.44
     203 1568.26     224 1587.16     245 1602.91   255.3 1608.75   269.2  1618.3
   302.7 1645.96   329.5 1662.71   373.7 1688.05   397.8 1705.56   445.6 1737.11
#Mann= 4 ,-1 , 0
       0     .06       0   69.58      .1       0   109.2    .045       0
     141      .1       0
Bank Sta=109.2,141
XS Rating Curve= 0 ,0
Exp/Cntr(USF)=0,0
Exp/Cntr=0.3,0.1

Type RM Length L Ch R = 1 ,9146    ,112.9,88,66
XS GIS Cut Line= 4
2455691.25662134654642.0707559382455704.05423949654536.845895599
2455691.25662134654273.783744754 2455662.8174699654125.900157251
#Sta/Elev= 30
       0  1663.6   24.841646.673   100.6 1594.91     108 1586.85     112  1577.7
     116 1562.79     120 1551.49   120.6  1550.6     140 1530.43     144 1527.56
   159.21523.678     180 1520.54   188.1 1520.99   195.91523.698   204.1 1527.77
  223.611528.093   228.1 1528.15   232.1 1529.57   272.2 1551.14   300.1 1568.29
   304.2 1572.61   312.2 1584.93   340.2  1607.6   368.3 1624.97   380.5 1633.98
   426.9 1664.81   441.6 1673.16   464.5 1689.66   478.3 1697.76     520 1728.91
#Mann= 5 ,-1 , 0
       0      .1       0   24.84     .06       0   159.2    .045       0
   195.9     .06       0  223.61      .1       0
Bank Sta=159.2,195.9
XS Rating Curve= 0 ,0
Exp/Cntr(USF)=0,0
Exp/Cntr=0.5,0.3

Type RM Length L Ch R = 1 ,9058    ,72.7,80.1,83.1
XS GIS Cut Line= 4
2455871.25373739654636.3463141022455851.28845957654499.193536311
2455745.38568181654425.4088140882455715.00373736654128.533814102
#Sta/Elev= 30
       0 1654.45   45.871622.151   138.6  1561.4   139.3 1560.87   142.1 1555.83
  145.571548.652     149 1542.57   158.8 1536.69   167.9 1525.49   176.6 1522.65
   183.1 1520.29   195.1 1518.89   212.4 1518.71   223.1 1519.17   236.8 1521.44
   251.1 1525.43   282.3 1527.23   294.3  1534.4   330.5 1552.29   346.6 1563.13
   350.6 1568.17   358.7 1580.48   362.7 1584.76   370.7 1591.25   390.8 1604.75
   425.6 1626.52   483.3 1665.57   519.5 1691.62   531.6 1699.52   566.1 1724.95
#Mann= 5 ,-1 , 0
       0      .1       0   45.87     .06       0  145.57      .1       0
   176.6    .045       0   236.8      .1       0
#XS Ineff= 2 , 0
             146 1523.92     276         1523.92
Permanent Ineff=
       F       F
Bank Sta=176.6,236.8
XS Rating Curve= 0 ,0
Exp/Cntr(USF)=0,0
Exp/Cntr=0.5,0.3

Type RM Length L Ch R = 1 ,8978    ,177.9,195.2,213.2
XS GIS Cut Line= 4
 2455915.5245707654633.7421474162455885.14262629 654449.71436964
 2455782.7120707654382.0060362962455756.67040405654129.401869655
#Sta/Elev= 30
       0 1651.26    50.11616.696    59.6  1609.9      84 1594.84    96.1 1586.05
   144.8  1553.9  147.641550.733   149.3 1548.65   156.9 1533.54     161 1526.67
   165.1 1524.22   181.3 1523.85   191.61520.902   198.9 1518.19   206.1 1517.89
   220.7 1518.39   230.7 1520.69   239.4 1524.04   271.4 1526.03   309.3 1541.07
   316.5 1545.39   344.6  1564.1   359.5 1576.95   374.1 1587.79     417 1616.04
   453.2 1641.59   465.3 1649.15   493.4 1669.97   523.6 1691.07   563.2 1720.94
#Mann= 5 ,-1 , 0
       0      .1       0    50.1     .06       0  147.64      .1       0
   191.6    .045       0   230.7      .1       0
Bank Sta=191.6,230.7
XS Rating Curve= 0 ,0
Exp/Cntr(USF)=0,0
Exp/Cntr=0.5,0.3

Type RM Length L Ch R = 1 ,8783    ,336.4,337.5,337.3
XS GIS Cut Line= 4
2456062.38754767654596.5681136292456058.12167495654482.811507858
2456042.48014166654235.3908903062456015.46294779654083.241430087
#Sta/Elev= 30
       0 1626.02   36.151601.081    85.7  1565.7   125.8 1538.87   134.31530.703
   141.8 1522.54   145.8 1520.72   165.9 1520.53   169.9 1519.15   174.51515.946
   177.9  1513.6   181.9 1513.14   201.9 1513.51   209.41515.941     242 1535.62
   262.1 1545.39   282.1  1556.8   310.1 1577.02   326.2 1587.64   334.2  1594.7
   342.2 1599.19   358.3 1610.86   374.4 1624.08   398.8 1641.96   415.1  1655.9
   447.6 1679.52   463.8 1693.32   488.2 1709.97   504.4  1722.4   516.3 1732.61
#Mann= 5 ,-1 , 0
       0      .1       0   36.15     .06       0   134.3      .1       0
   174.5    .045       0   209.4      .1       0
Bank Sta=174.5,209.4
XS Rating Curve= 0 ,0
Exp/Cntr(USF)=0,0
Exp/Cntr=0.3,0.1

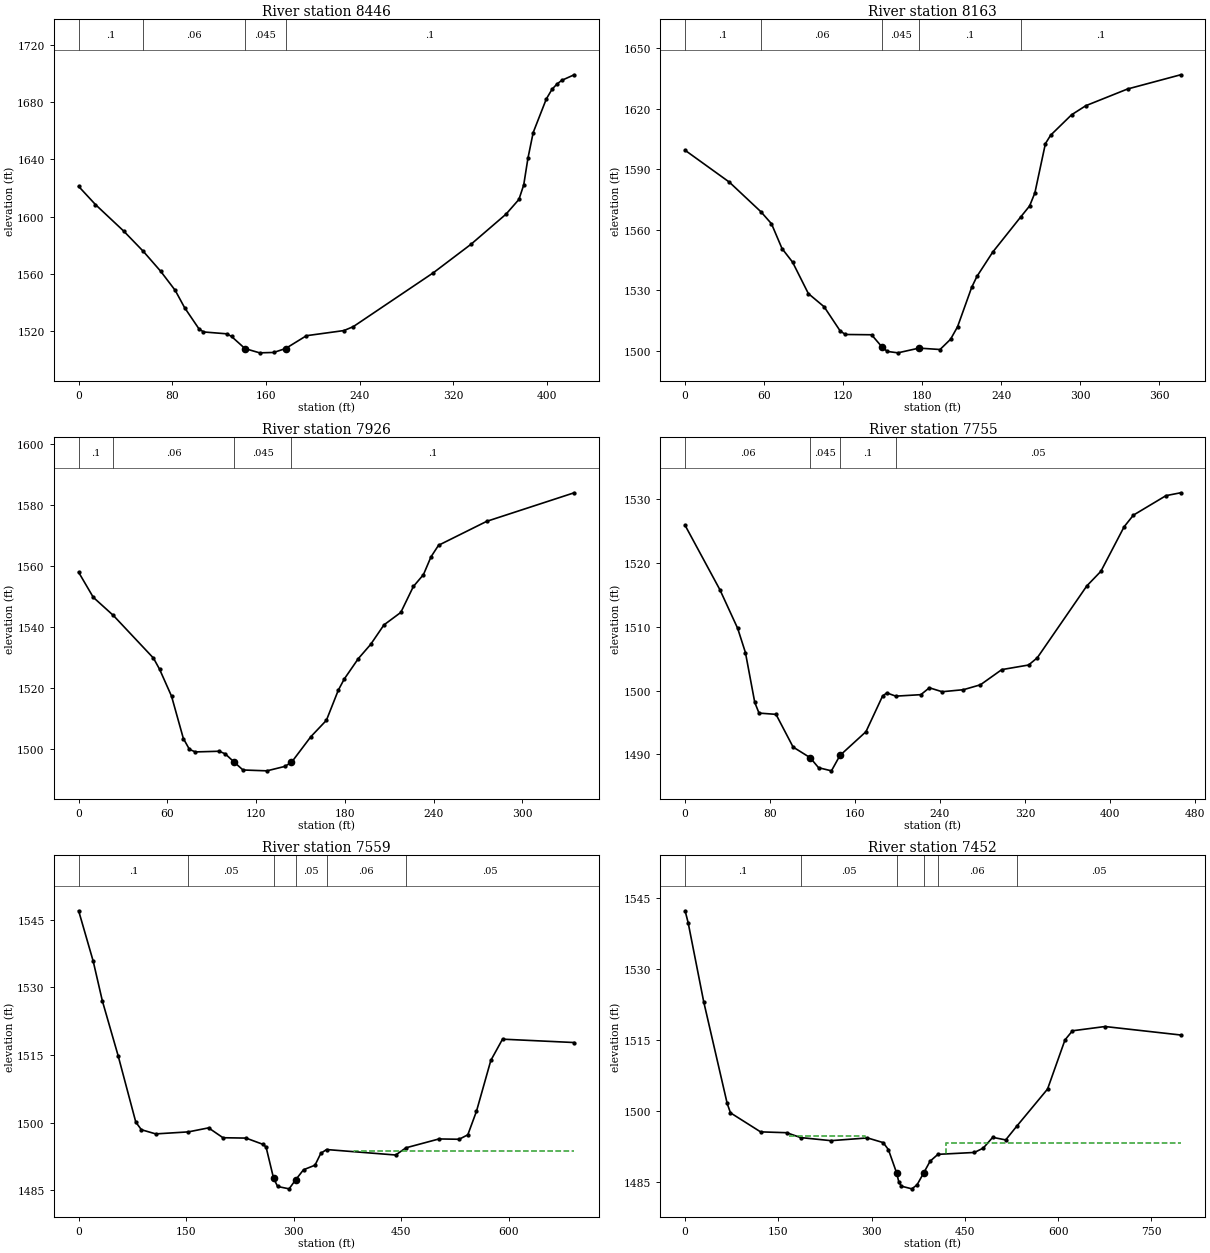
Type RM Length L Ch R = 1 ,8446    ,282.2,282.9,285
XS GIS Cut Line= 4
 2456382.3280014654565.2850470422456388.01583169654462.904101848
2456385.17191654 654290.847235622456359.57668025654144.385605689
#Sta/Elev= 30
       0 1621.12    14.4 1608.42    38.5 1589.96   55.311575.771      70 1562.02
    82.5 1548.62    90.5 1536.59   102.6 1522.02   106.6 1519.64   126.6 1518.33
   130.6 1516.49   142.11508.046   154.6 1505.07   166.6 1505.33   176.81508.075
   194.6 1517.02   226.6  1520.6   234.6 1523.32     303  1560.9   335.2 1580.78
   365.1 1601.77   376.1 1612.01   380.2 1622.12   383.8 1640.72   388.3 1658.68
   399.5 1682.06   404.4 1688.84   408.6 1692.45   412.6 1695.01   423.3 1698.93
#Mann= 4 ,-1 , 0
       0      .1       0   55.31     .06       0   142.1    .045       0
   176.8      .1       0
Bank Sta=142.1,176.8
XS Rating Curve= 0 ,0
Exp/Cntr(USF)=0,0
Exp/Cntr=0.3,0.1

Type RM Length L Ch R = 1 ,8163    ,235.6,236.4,243.7
XS GIS Cut Line= 4
2456666.25029827 654524.435645712456662.10386999654422.848152841
2456661.06726292654246.624950926 2456595.7610175 654173.02584895
#Sta/Elev= 30
       0 1599.38    33.6 1583.61   57.681568.871    65.6 1562.99    73.6 1550.71
    81.6    1544    93.6 1528.41   105.6 1521.87   117.6 1510.07   121.6 1508.16
   141.6 1508.02   149.6 1501.92   153.6 1499.77   161.6 1499.07   177.6 1501.41
   193.6 1500.72   201.6 1505.81   206.9 1511.99   217.6 1531.46   221.6  1536.9
   233.6 1548.95  254.711566.243   261.6 1571.81   265.6 1578.25   273.6 1602.66
   277.6 1606.86   293.5 1616.97   304.3 1621.46     336 1629.73   376.3 1636.77
#Mann= 5 ,-1 , 0
       0      .1       0   57.68     .06       0   149.6    .045       0
   177.6      .1       0  254.71      .1       0
Bank Sta=149.6,177.6
XS Rating Curve= 0 ,0
Exp/Cntr(USF)=0,0
Exp/Cntr=0.3,0.1

Type RM Length L Ch R = 1 ,7926    ,172.3,171.4,170.2
XS GIS Cut Line= 4
2456865.27885572654556.570464883 2456876.6815335654497.483861888
2456892.23063955654368.9445851972456802.04582445654254.917807487
#Sta/Elev= 30
       0 1557.88     9.9 1549.66   23.461543.712    50.6 1529.69    54.7 1526.06
    62.8 1517.21    70.8  1503.3    74.9 1499.74    78.9  1498.9      95 1499.12
    99.1 1498.27   105.31495.485   111.1 1492.97   127.3 1492.69   139.3 1494.13
   143.91495.478     157 1503.91   167.5 1509.28   175.6 1519.23   179.6 1522.86
   189.1 1529.55   197.4 1534.19   206.4  1540.6   217.8  1544.7   226.3 1553.22
   233.1  1557.1   238.2 1562.94   243.3 1566.74   275.9 1574.61     335 1583.98
#Mann= 4 ,-1 , 0
       0      .1       0   23.46     .06       0   105.3    .045       0
   143.9      .1       0
Bank Sta=105.3,143.9
XS Rating Curve= 0 ,0
Exp/Cntr(USF)=0,0
Exp/Cntr=0.3,0.1

Type RM Length L Ch R = 1 ,7755    ,194.4,196,195.3
XS GIS Cut Line= 4
2457028.02616573654602.1811759672457040.46545057654567.973142654
2457062.23419904654273.5767347492457007.29402433654150.220493408
#Sta/Elev= 30
       0 1525.92    32.8 1515.81    49.5 1509.76    56.8 1505.97    65.6 1498.14
    69.6 1496.47    85.6 1496.27   101.7 1491.14   117.7 1489.48   125.7  1487.9
   137.8 1487.41   145.8 1489.82   170.3 1493.55   185.9 1499.13   189.9 1499.64
  198.361499.127     222 1499.36     230 1500.44     242 1499.82   262.1 1500.14
   278.1 1500.91   298.2 1503.29   323.4 1504.01   331.6 1505.14   378.3 1516.43
   391.5 1518.71   413.4  1525.7   422.1 1527.52   452.8 1530.58   466.6 1531.03
#Mann= 4 ,-1 , 0
       0     .06       0   117.7    .045       0   145.8      .1       0
  198.36     .05       0
Bank Sta=117.7,145.8
XS Rating Curve= 0 ,0
Exp/Cntr(USF)=0,0
Exp/Cntr=0.3,0.1

Type RM Length L Ch R = 1 ,7559    ,102.3,106.9,112.7
XS GIS Cut Line= 4
2457156.96418725654795.3478265132457220.20430763654708.392660994
2457239.96684524654443.5746569162457272.90440794654127.374055032
#Sta/Elev= 30
       0 1547.02    20.3 1535.83    33.1 1526.99      55 1514.88    79.7 1500.09
    87.5  1498.4   107.5 1497.47   153.1 1497.92   181.2 1498.81   201.3 1496.62
   233.4 1496.54   257.4 1495.13   261.4 1494.53   271.8 1487.64   277.5 1485.79
   293.5 1485.27   302.51487.253   313.6 1489.51   329.6 1490.52   337.7 1493.15
   345.7    1494   442.1 1492.78   456.4 1494.38   502.5 1496.35   530.6 1496.28
   542.7 1497.27   554.8 1502.51   574.8  1513.8   591.1 1518.51     691 1517.76
#Mann= 6 ,-1 , 0
       0      .1       0   153.1     .05       0   271.8    .045       0
   302.5     .05       0   345.7     .06       0   456.4     .05       0
#XS Ineff= 2 , 0
                          384.48          1493.7
Permanent Ineff=
       F       F
Bank Sta=271.8,302.5
XS Rating Curve= 0 ,0
Exp/Cntr(USF)=0,0
Exp/Cntr=0.5,0.3

Type RM Length L Ch R = 1 ,7452    ,82.2,80.1,77.8
XS GIS Cut Line= 4
 2457191.8100828654842.6740162282457262.29936357 654756.63562941
2457404.31453217654306.7481609922457378.39935542654094.243711623
#Sta/Elev= 30
       0 1542.24     4.9 1539.73    29.9 1523.04    67.7 1501.52      73 1499.54
   121.4 1495.52   163.4 1495.34  185.851494.312   234.7 1493.66   293.4 1494.24
   318.6 1493.25     327 1491.78   340.4 1486.79   343.8 1484.92     348 1484.04
   364.7 1483.48   373.1 1484.32   383.61486.799   394.1 1489.32  406.671490.768
   465.4 1491.17   479.6 1492.09   494.8 1494.36   515.7 1493.82  533.321496.691
     583 1504.56   611.1 1514.96   623.1 1516.88   675.5 1517.78   797.1 1515.99
#Mann= 6 ,-1 , 0
       0      .1       0  185.85     .05       0   340.4    .045       0
   383.6     .05       0  406.67     .06       0  533.32     .05       0
#XS Ineff= 3 ,-1
  166.48  289.311494.715  290.96   303.5 1493.15     419   797.1 1493.12
Permanent Ineff=
       F       F       F
Bank Sta=340.4,383.6
XS Rating Curve= 0 ,0
Exp/Cntr(USF)=0,0
Exp/Cntr=0.5,0.3

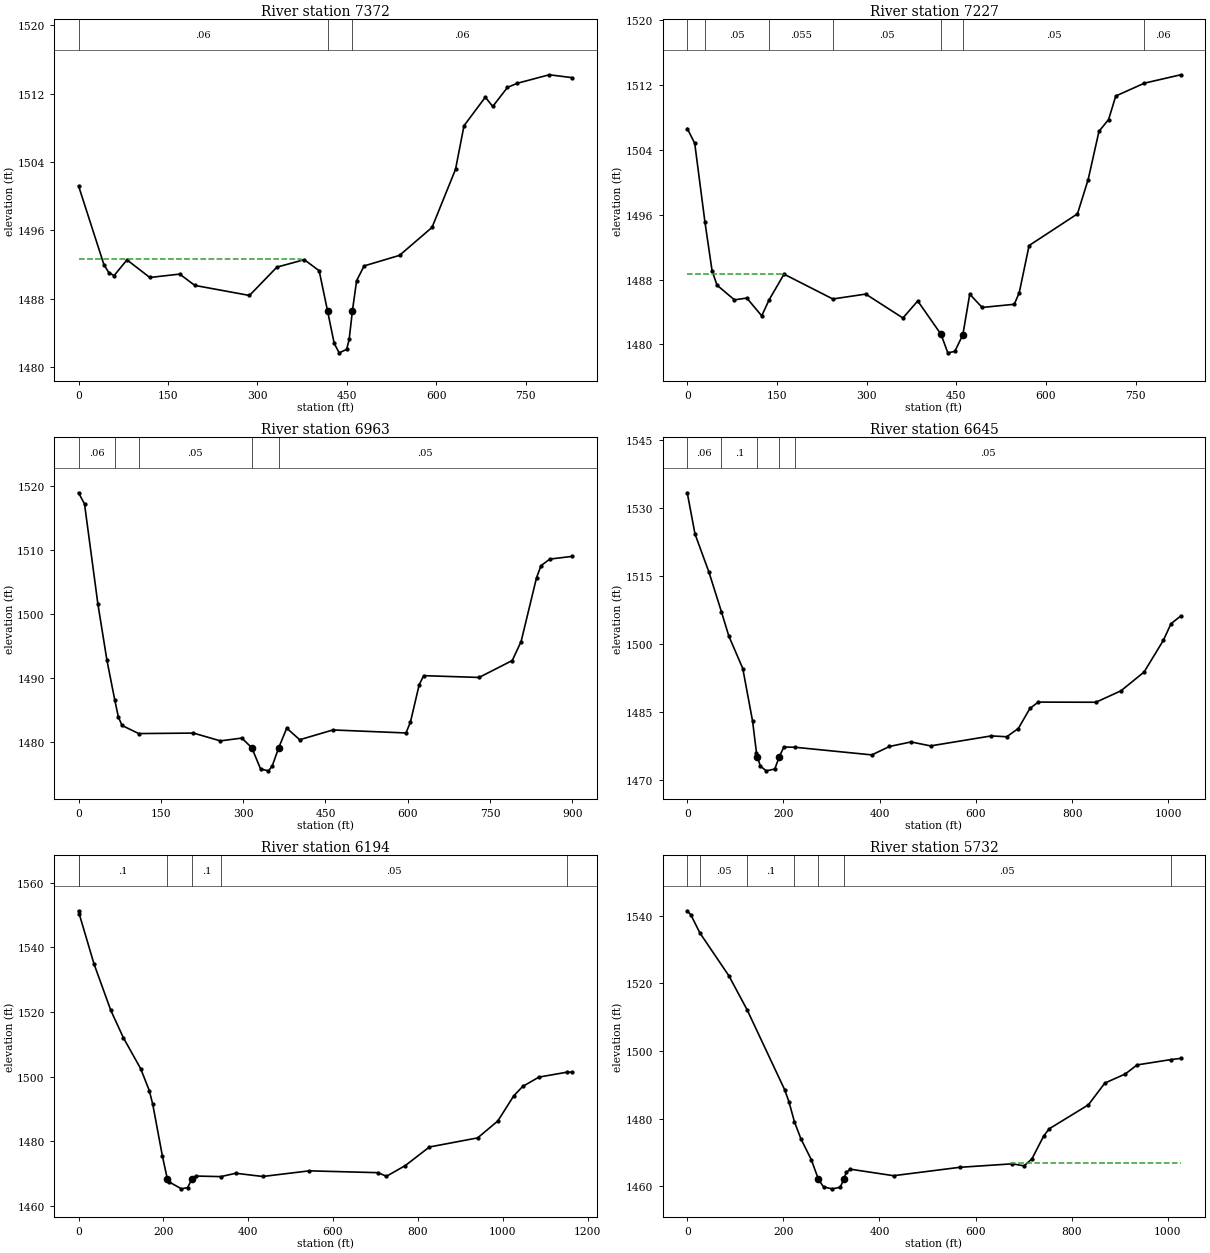
Type RM Length L Ch R = 1 ,7372    ,145,145.3,141.2
XS GIS Cut Line= 4
2457372.28111043654918.6290433632457333.29623576654817.993669214
2457478.35623453654338.3890482692457527.31398412 654125.33217507
#Sta/Elev= 30
       01501.208  42.6161491.975  51.1951491.004  59.7741490.709  81.2231492.541
 119.5221490.479  169.671490.876 194.9951489.552 286.6811488.374 332.649 1491.69
 378.6181492.563 403.5491491.268   417.61486.568 428.7651482.768 437.1231481.658
  449.661482.063 453.839 1483.22   459.31486.574 466.3761490.111 478.9131491.832
 538.3071493.068 592.8511496.343 632.2521503.145 646.4431508.243 682.1651511.583
 694.6591510.499 719.2841512.728 735.7481513.213 789.3311514.208 827.5941513.873
#Mann= 3 , 0 , 0
       0     .06       0   417.6    .045       0   459.3     .06       0
#XS Ineff= 2 , 0
          372.47 1492.66
Permanent Ineff=
       F       F
Bank Sta=417.6,459.3
XS Rating Curve= 0 ,0
Exp/Cntr(USF)=0,0
Exp/Cntr=0.5,0.3

Type RM Length L Ch R = 1 ,7227    ,263.8,263.1,229.4
XS GIS Cut Line= 4
2457432.95480839654966.9238477022457483.62226211654784.213938833
2457588.02792433654394.2280829282457601.84632079654162.386097725
#Sta/Elev= 30
       0 1506.65    12.5 1504.83   29.651495.079    41.5 1489.11    49.8 1487.32
    78.9 1485.51    99.7 1485.73   124.6 1483.53  136.691485.474   161.9 1488.68
  243.511485.617   298.6 1486.22   360.8 1483.27   385.6 1485.37   424.6 1481.25
   435.9 1478.97   447.7 1479.15   461.1 1481.21   472.6 1486.21   493.3 1484.57
   547.1 1484.96   555.4 1486.39   571.9 1492.21   652.8 1496.12   670.7 1500.35
   688.8  1506.3   704.9 1507.76   716.9 1510.66  764.881512.247   825.6 1513.28
#Mann= 7 ,-1 , 0
       0     .06       0   29.65     .05       0  136.69    .055       0
  243.51     .05       0   424.6    .045       0   461.1     .05       0
  764.88     .06       0
#XS Ineff= 2 , 0
          161.11 1488.67
Permanent Ineff=
       F       F
Bank Sta=424.6,461.1
XS Rating Curve= 0 ,0
Exp/Cntr(USF)=0,0
Exp/Cntr=0.3,0.1

Type RM Length L Ch R = 1 ,6963    ,332.9,318.8,214.7
XS GIS Cut Line= 4
2457603.38169818655072.8648872982457681.68594484654785.749316219
2457736.95953071654712.0512017172457802.98075829654206.912041903
#Sta/Elev= 30
       0 1518.94    10.9  1517.2    35.2 1501.57    51.8  1492.7   66.071486.489
    72.5 1483.86    79.3 1482.51  109.711481.244   209.4 1481.32   258.4  1480.1
   297.6 1480.54   315.7 1479.02   331.8 1475.69   346.1 1475.41   352.7 1476.12
   364.71479.013   379.4 1482.09     403 1480.28   463.5 1481.81   596.6 1481.34
   604.7 1483.02   620.8 1488.91   628.9 1490.31   729.8 1490.03   790.3 1492.68
   806.4 1495.65   834.6 1505.66   842.7 1507.53   858.8 1508.56   899.2 1508.98
#Mann= 5 ,-1 , 0
       0     .06       0   66.07      .1       0  109.71     .05       0
   315.7    .045       0   364.7     .05       0
Bank Sta=315.7,364.7
XS Rating Curve= 0 ,0
Exp/Cntr(USF)=0,0
Exp/Cntr=0.3,0.1

Type RM Length L Ch R = 1 ,6645    ,436.5,450.6,440.5
XS GIS Cut Line= 4
2457839.82981554655186.4828138212457870.53736325655069.794132527
2457979.54915761654464.8554426592457990.29679931654174.669116809
#Sta/Elev= 30
       0 1533.34    16.1 1524.24    45.1 1515.81   71.061507.051    86.4  1501.7
   115.4 1494.53   135.8  1482.9   143.9  1475.9   145.61475.021   152.1 1472.95
   164.3 1471.93   181.9 1472.33   191.21475.015   200.8  1477.2  224.64 1477.13
   383.7 1475.45   420.3 1477.31     465 1478.31   505.7 1477.44   631.7 1479.64
     664 1479.46   688.1 1481.28   712.2 1485.71   729.5 1487.11   849.4 1487.08
   901.4  1489.6   949.5 1493.75   989.5 1500.74  1005.5 1504.43  1025.7 1506.12
#Mann= 5 ,-1 , 0
       0     .06       0   71.06      .1       0   145.6    .045       0
   191.2      .1       0  224.64     .05       0
Bank Sta=145.6,191.2
XS Rating Curve= 0 ,0
Exp/Cntr(USF)=0,0
Exp/Cntr=0.3,0.1

Type RM Length L Ch R = 1 ,6194    ,485,462.2,332.1
XS GIS Cut Line= 4
2458229.81567144655310.8483820432458263.59397392655131.209227945
2458323.47369196 655045.228094362458444.76850541 654177.73987158
#Sta/Elev= 30
       0 1551.34    1.58  1550.4    36.6 1534.86    76.1 1520.53   105.8 1512.04
   146.5  1502.5   166.8 1495.72     175 1491.47   197.8 1475.42   209.21468.487
   212.4 1467.54   242.7 1465.32   257.1 1465.71   267.91468.479   275.8 1469.28
  335.611469.101   370.7 1470.14   434.3 1469.14   544.1 1470.89   705.9 1470.32
   726.1 1469.21   770.6 1472.53   827.1 1478.26     941 1481.08   988.7 1486.33
    1026 1494.07  1047.1 1496.99  1085.6 1499.89 1150.641501.385  1163.5 1501.43
#Mann= 6 ,-1 , 0
       0    .055       0    1.58      .1       0   209.2    .045       0
   267.9      .1       0  335.61     .05       0 1150.64     .05       0
Bank Sta=209.2,267.9
XS Rating Curve= 0 ,0
Exp/Cntr(USF)=0,0
Exp/Cntr=0.3,0.1

Type RM Length L Ch R = 1 ,5732    ,480.8,494.5,541.4
XS GIS Cut Line= 4
2458807.11756837655246.3625318542458750.30860511655039.086584818
2458701.17652878654911.6502618262458590.62935703 654245.29647654
#Sta/Elev= 30
       0 1541.41     7.7 1540.15   26.541534.808    86.5 1522.24  124.711512.123
   202.7 1488.56   211.5 1485.07  223.011479.099   236.6 1474.04   258.2 1467.88
   273.1 1462.06   283.7 1459.84   301.4 1459.28     318 1459.71   325.91462.056
   330.9 1464.18   339.5 1465.08   429.3 1463.16   567.2 1465.64   676.6 1466.67
     701 1466.06   717.2 1468.11   741.5  1474.8   752.9 1476.98   834.8 1484.09
     869 1490.52   911.8 1493.22   936.1 1495.88 1006.271497.452    1027 1497.81
#Mann= 7 ,-1 , 0
       0     .06       0   26.54     .05       0  124.71      .1       0
  223.01     .05       0   273.1    .045       0   325.9     .05       0
 1006.27     .05       0
#XS Ineff= 2 , 0
                          672.92         1466.83
Permanent Ineff=
       F       F
Bank Sta=273.1,325.9
XS Rating Curve= 0 ,0
Exp/Cntr(USF)=0,0
Exp/Cntr=0.3,0.1

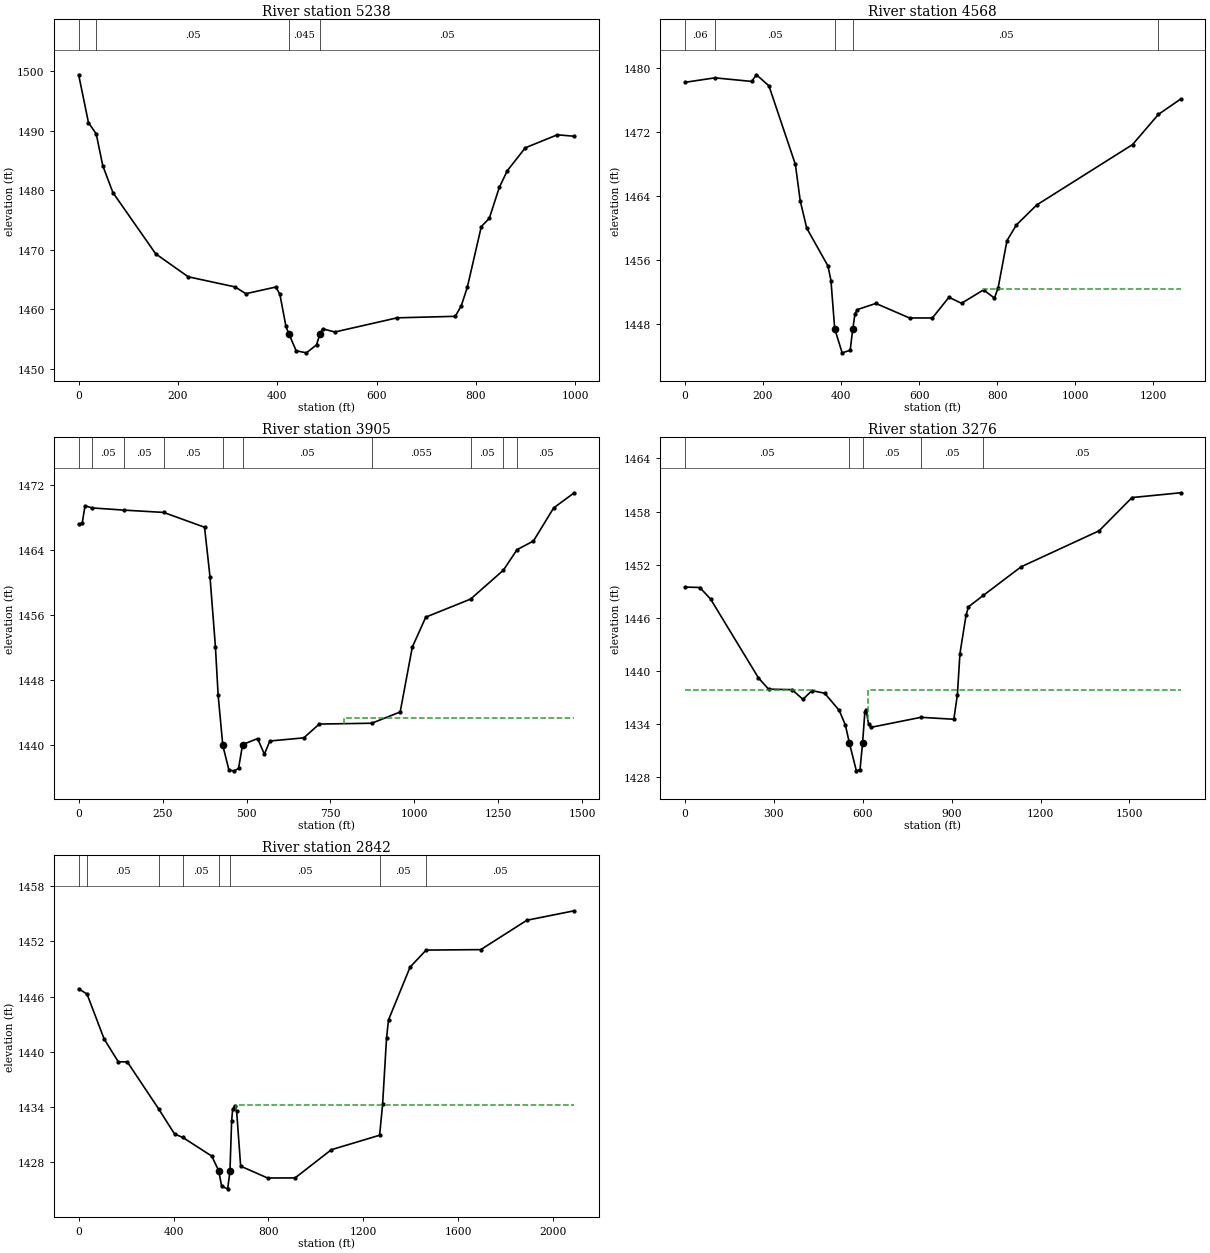
Type RM Length L Ch R = 1 ,5238    ,657.7,669.3,635.2
XS GIS Cut Line= 4
2459100.37464899655306.2422498872459181.74965042654940.822432149
2459220.13408506 654775.001674522459275.40767094654325.136100583
#Sta/Elev= 30
       0 1499.38    19.8 1491.35   35.461489.447    48.5 1484.14      69  1479.6
   155.1 1469.32   220.6 1465.46   314.9 1463.76   336.6 1462.62     397 1463.74
   405.1 1462.55   417.4 1457.13   423.51455.838   437.9 1453.04   458.5 1452.69
     479 1454.03   485.71455.853   491.3 1456.73   515.9 1456.19   641.4 1458.57
   758.3 1458.82   770.4  1460.6   782.5 1463.69   810.7 1473.89   826.8 1475.28
   846.9 1480.46   863.1 1483.28   899.3 1487.12   963.8  1489.3   997.8 1489.06
#Mann= 4 ,-1 , 0
       0     .06       0   35.46     .05       0   423.5    .045       0
   485.7     .05       0
Bank Sta=423.5,485.7
XS Rating Curve= 0 ,0
Exp/Cntr(USF)=0,0
Exp/Cntr=0.3,0.1

Type RM Length L Ch R = 1 ,4568    ,657.3,663.2,613
XS GIS Cut Line= 4
2459643.89824344 655554.973386332459739.09164134655220.261116301
2459797.43598199654974.6007346292459868.06334172654308.246949343
#Sta/Elev= 30
       0 1478.17   76.621478.728   170.7 1478.28   183.1 1479.11   215.1 1477.73
   282.9 1467.93   295.3  1463.4     312 1459.98   366.5 1455.26   374.1 1453.44
   383.71447.438   402.8 1444.43   423.4 1444.75     4301447.403   435.7 1449.29
   441.9 1449.83   489.2 1450.59   575.5 1448.78   634.1 1448.78   676.6 1451.36
   708.8 1450.61   765.2 1452.28   793.3 1451.26   802.7 1452.54   825.4 1458.43
   849.6 1460.39   901.9 1462.88  1147.2  1470.4 1213.621474.167  1270.6 1476.08
#Mann= 5 ,-1 , 0
       0     .06       0   76.62     .05       0   383.7    .045       0
     430     .05       0 1213.62     .05       0
#XS Ineff= 2 , 0
                           764.5         1452.36
Permanent Ineff=
       F       F
Bank Sta=383.7,430
XS Rating Curve= 0 ,0
Exp/Cntr(USF)=0,0
Exp/Cntr=0.3,0.1

Type RM Length L Ch R = 1 ,3905    ,627.5,629.2,609.6
XS GIS Cut Line= 4
2460230.41240469655825.1998061692460325.60580258 655470.52763013
 2460408.5161814654959.2469607752460368.59636938654369.662044761
#Sta/Elev= 30
       0 1467.21    10.7 1467.35      19 1469.49   39.921469.222  135.351468.951
  253.211468.666     375 1466.84   391.2 1460.75   407.4  1452.1   415.5 1446.12
   429.41439.924   447.9 1436.85   464.1 1436.79   476.3  1437.1   488.4 1440.03
     533 1440.77   553.3 1438.84   569.5 1440.47   670.8 1440.86   716.6 1442.56
  873.031442.663   957.7 1444.05   993.8 1452.05  1033.9 1455.75 1167.291457.973
 1265.191461.545 1305.731464.072  1354.6 1465.14  1414.8 1469.22  1476.1 1471.09
#Mann= 10 ,-1 , 0
       0     .06       0   39.92     .05       0  135.35     .05       0
  253.21     .05       0   429.4    .045       0   488.4     .05       0
  873.03    .055       0 1167.29     .05       0 1265.19    .055       0
 1305.73     .05       0
#XS Ineff= 2 , 0
                          789.25         1443.34
Permanent Ineff=
       F       F
Bank Sta=429.4,488.4
XS Rating Curve= 0 ,0
Exp/Cntr(USF)=0,0
Exp/Cntr=0.3,0.1

Type RM Length L Ch R = 1 ,3276    ,418,433.5,579.4
XS GIS Cut Line= 4
2460589.78548926655811.5330519112460917.71177035655527.203906457
2461046.60764963654990.7695853672460699.72609217654397.469435186
#Sta/Elev= 30
       0 1449.49    49.8 1449.44    86.2 1448.14   247.8 1439.24   281.9 1437.97
   361.2 1437.91   397.9 1436.82   428.4  1437.8   471.4 1437.51   520.7 1435.56
   541.3 1433.91   554.81431.893   578.3 1428.75   590.7  1428.9   599.3 1431.89
   607.1 1435.42   611.2 1435.67   619.5 1434.03   627.7 1433.66  796.44 1434.79
   907.4 1434.57   919.4 1437.35     928 1441.98   948.6 1446.31   956.8 1447.26
 1007.211448.556  1134.7 1451.78  1397.8 1455.84  1508.9 1459.59    1673 1460.13
#Mann= 5 ,-1 , 0
       0     .05       0   554.8    .045       0   599.3     .05       0
  796.44     .05       0 1007.21     .05       0
#XS Ineff= 2 , 0
          439.68 1437.84     617         1437.84
Permanent Ineff=
       F       F
Bank Sta=554.8,599.3
XS Rating Curve= 0 ,0
Exp/Cntr(USF)=0,0
Exp/Cntr=0.3,0.1

Type RM Length L Ch R = 1 ,2842    ,,,
XS GIS Cut Line= 4
2460657.01187854655844.7731031092461132.58116691655678.323852178
2461520.96275242655551.5053752792461219.76886978654414.102160591
#Sta/Elev= 30
       0 1446.84   35.391446.272   107.8 1441.36   167.1  1438.9   205.3 1438.88
  338.011433.734   404.4 1431.03  438.881430.661   560.8 1428.63   590.3 1427.05
   602.9 1425.33   628.2 1425.06  637.79 1426.97     645  1432.5   649.2  1433.7
   657.6 1434.13     666 1433.53   682.9 1427.53   796.5 1426.24   912.4 1426.25
  1065.2 1429.32 1268.651430.898  1281.3 1434.26  1297.9 1441.51  1306.2 1443.46
  1397.2 1449.21  1464.81451.061  1695.1 1451.11  1889.5 1454.312089.026 1455.34
#Mann= 8 ,-1 , 0
       0     .05       0   35.39     .05       0  338.01     .05       0
  438.88     .05       0   590.3    .045       0  637.79     .05       0
 1268.65     .05       0  1464.8     .05       0
#XS Ineff= 2 , 0
                          664.93         1434.15
Permanent Ineff=
       F       F
Bank Sta=590.3,637.79
XS Rating Curve= 0 ,0
Exp/Cntr(USF)=0,0
Exp/Cntr=0.3,0.1
LCMann Table=0

Chan Stop Cuts=-1
Use User Specified Reach Order=0
Composite Channel Slope=5